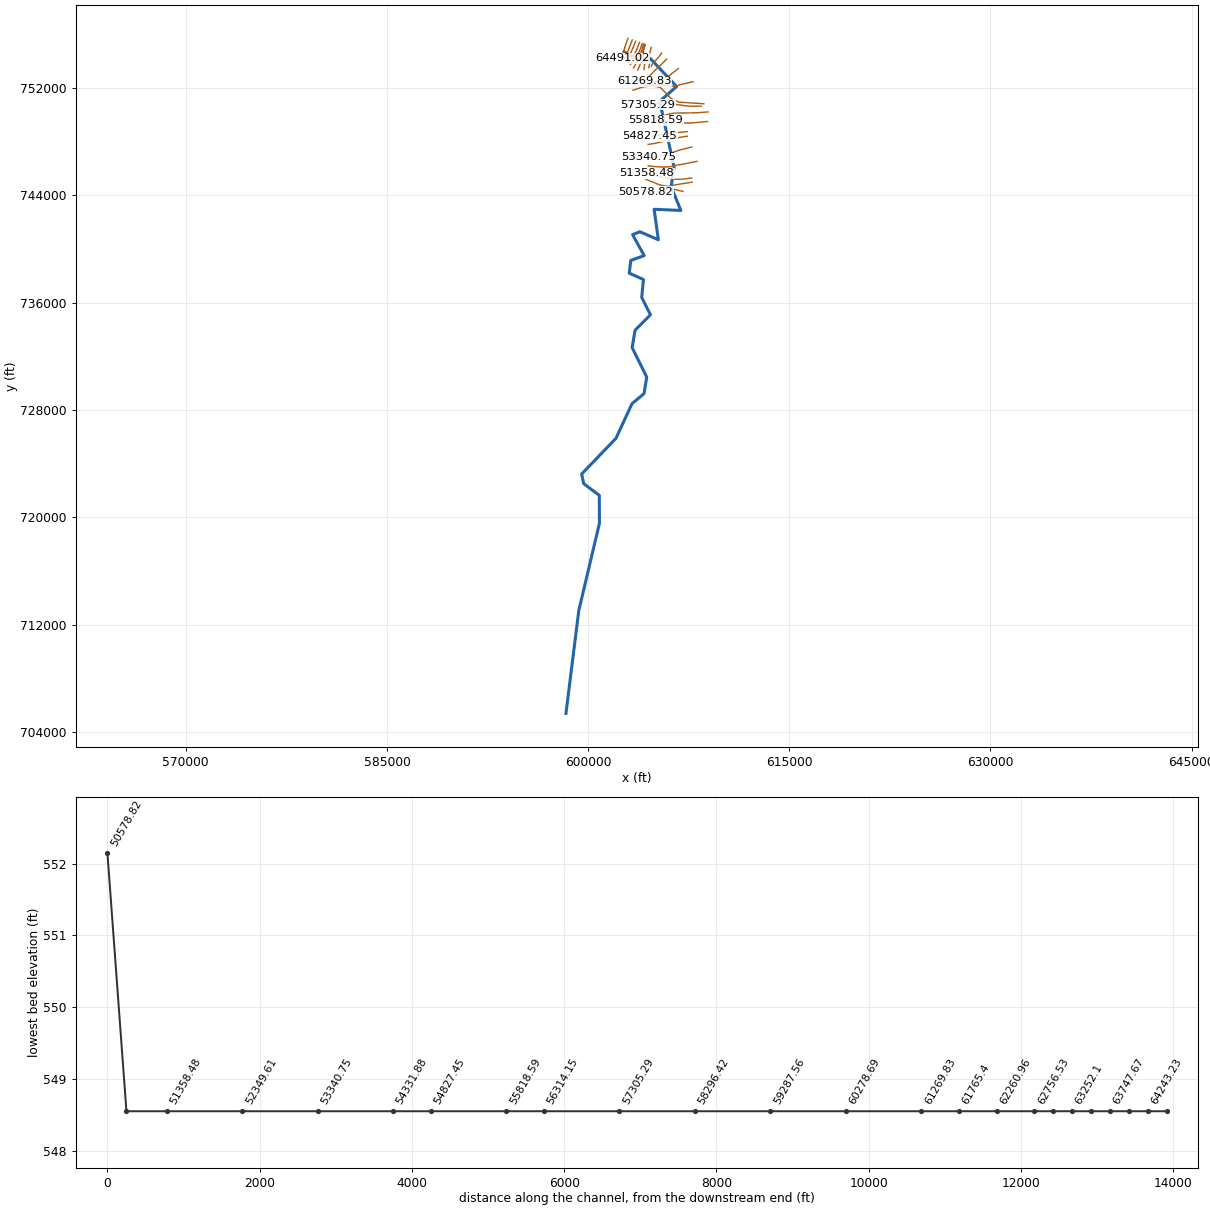
--- 2027_ras.prj (project) ---

Proj Title=2027
Current Plan=p01
Default Exp/Contr=0.3,0.1
English Units
Geom File=g01
Flow File=f01
Plan File=p01
Y Axis Title=Elevation
X Axis Title(PF)=Main Channel Distance
X Axis Title(XS)=Station
BEGIN DESCRIPTION:
RFD model 2027 exported to HEC-RAS
END DESCRIPTION:

--- 2027_ras.p01 (plan) ---

Plan Title=Plan 01
Program Version=4.10
Short Identifier=Plan 01
Geom File=g01
Flow File=f01
Subcritical Flow
Calc Critical at every XS
Secant Critical Depth

--- 2027_ras.f01 (steady flow) ---

Flow Title=Flow 01
Program Version=5.01
Number of Profiles= 6
Profile Names=10yr,25yr,50yr,100yr,100plus,500yr
River Rch & RM=2027,132,64491.02
 8488.3913902.7219122.57 23912.234911.8135343.24
River Rch & RM=2027,132,64243.23
 8495.5513915.6519141.4523937.0234948.0535378.74
River Rch & RM=2027,132,63995.45
 8500.4513924.5719154.5323954.2934973.2635403.65
River Rch & RM=2027,132,63747.67
 8503.3413929.8619162.3223964.5934988.3135418.59
River Rch & RM=2027,132,63499.88
 8505.5113933.8319168.1523972.3234999.5935429.79
River Rch & RM=2027,132, 63252.1
 8566.41 14042.619326.0124178.91 35301.235721.86
River Rch & RM=2027,132,63004.32
 8569.0514047.4519333.1324188.3335314.97 35735.5
River Rch & RM=2027,132,62756.53
 8572.1814053.1719341.5524199.4735331.2335751.63
River Rch & RM=2027,132,62260.96
 8588.5814083.2219385.7924258.0635416.7735836.56
River Rch & RM=2027,132, 61765.4
 8593.8214092.9119400.1324277.1335444.6135864.44
River Rch & RM=2027,132,61269.83
 8603.1314110.1319425.6224311.0135494.0835913.98
River Rch & RM=2027,132,60278.69
 8743.1914362.7519794.3124795.8336201.9136604.77
River Rch & RM=2027,132,59287.56
 8755.4414385.5719828.1924841.0336267.9136671.12
River Rch & RM=2027,132,58296.42
 8790.0814450.2319924.3824969.5136455.4836860.05
River Rch & RM=2027,132,57305.29
 8830.5414525.3120035.6925117.7736671.9537076.74
River Rch & RM=2027,132,56314.15
 8896.7314649.4520220.84 25365.637033.7837442.26
River Rch & RM=2027,132,55818.59
 8905.6614666.2820245.9925399.3437083.0437492.19
River Rch & RM=2027,132,54827.45
 8937.84   1472720336.8625521.2837261.0737672.81
River Rch & RM=2027,132,54331.88
 9466.6415655.8321672.6327256.4339794.3840052.73
River Rch & RM=2027,132,53340.75
 9476.6715674.6621700.7627294.1239849.4140107.88
River Rch & RM=2027,132,52349.61
 9525.2815764.1521832.97 27469.840105.9140360.11
River Rch & RM=2027,132,51358.48
 9592.29 15891.922025.2927729.24 40484.740744.37
River Rch & RM=2027,132, 50828.4
 9644.2615988.7122169.2827921.6340765.5841023.26
River Rch & RM=2027,132,50578.82
 9645.2415990.6122172.1627925.5440771.2941029.14
River Rch & RM=2027,132,49824.49
 7180.2310070.8912520.7515238.8722826.2623534.27
River Rch & RM=2027,132,49437.06
 7182.2410073.9112524.6515243.7922833.6323541.38
River Rch & RM=2027,132,48870.54
 7196.0110094.5412551.3915277.5222884.1523590.11
River Rch & RM=2027,132,   47903
 7214.73 10122.612587.7715323.3922952.8723656.38
River Rch & RM=2027,132,47307.27
 7223.7110136.0512605.2115345.38 22985.823688.14
River Rch & RM=2027,132,47137.41
 7226.8510140.7712611.32 15353.122997.3623699.28
River Rch & RM=2027,132, 47041.5
 7228.1910142.7712613.9215356.3723002.2623704.01
River Rch & RM=2027,132, 46954.1
 7228.8610143.7712615.22   1535823004.7123706.37
River Rch & RM=2027,132,46730.66
 7236.01 10154.512629.1215375.5423030.9723731.69
River Rch & RM=2027,132,46485.53
 7238.01 10157.512633.0115380.4423038.3323738.78
River Rch & RM=2027,132, 46240.4
 7278.0910217.5912710.9315478.7423185.5623880.69
River Rch & RM=2027,132,45995.27
  7279.810220.1512714.2515482.9323191.8523886.75
River Rch & RM=2027,132,45750.15
 7283.2210225.2812720.9115491.3323204.4223898.87
River Rch & RM=2027,132,45505.02
 7285.3110228.4212724.9715496.4623212.1123906.27
River Rch & RM=2027,132,45259.89
  7287.5 10231.712729.2215501.8223220.1423914.01
River Rch & RM=2027,132,45014.76
  7289.410234.5512732.9215506.4923227.1223920.74
River Rch & RM=2027,132,44598.31
 7308.3810263.0212769.8615553.0923296.94   23988
River Rch & RM=2027,132,44279.38
 7315.2110273.2712783.1515569.8623322.05 24012.2
River Rch & RM=2027,132,44034.25
 7317.5810276.8312787.7615575.6823330.77 24020.6
River Rch & RM=2027,132,43789.13
 7318.6310278.3912789.7915578.2423334.6124024.29
River Rch & RM=2027,132,   43544
 7320.2410280.8112792.93 15582.223340.54   24030
River Rch & RM=2027,132,43298.87
  7322.810284.6512797.9115588.4923349.9524039.07
River Rch & RM=2027,132,43053.75
 7325.2610288.34 12802.715594.5423359.02 24047.8
River Rch & RM=2027,132,42808.62
 7328.6710293.4612809.3415602.9223371.5624059.89
River Rch & RM=2027,132,42199.33
 7345.7210319.0412842.5215644.7923434.2824120.29
River Rch & RM=2027,132,41337.85
 7416.24 10424.912979.89 15818.223694.0424370.34
River Rch & RM=2027,132,41092.73
 7418.2210427.8712983.7515823.0623701.3224377.35
River Rch & RM=2027,132, 40847.6
 7421.0410432.1112989.2515830.0223711.7424387.37
River Rch & RM=2027,132,40602.47
 7422.9310434.9412992.9215834.6523718.6824394.05
River Rch & RM=2027,132,40357.34
 7426.3110440.0312999.5315842.9923731.1724406.07
River Rch & RM=2027,132,40112.22
 7433.5610450.9113013.6615860.8323757.8924431.78
River Rch & RM=2027,132,39621.96
 7440.61 10461.513027.4115878.19 23783.924456.81
River Rch & RM=2027,132,39376.83
 7441.5510462.9113029.2415880.5123787.3724460.14
River Rch & RM=2027,132,39131.71
 7446.9110470.9613039.69 15893.723807.1324479.15
River Rch & RM=2027,132,38886.58
 7448.2310472.9413042.2615896.9423811.9824483.82
River Rch & RM=2027,132,38641.45
 7449.3610474.6313044.4615899.7223816.1424487.82
River Rch & RM=2027,132,38396.32
  7494.4 10542.313132.3216010.6823982.3624647.69
River Rch & RM=2027,132,38136.16
 7509.0110564.2613160.83 16046.7 24036.324699.55
River Rch & RM=2027,132,37359.85
  7519.410579.87 13181.116072.3124074.6724736.44
River Rch & RM=2027,132,37076.21
 7520.2410581.1313182.7516074.3924077.7824739.43
River Rch & RM=2027,132, 36977.5
 7540.5210611.6313222.3516124.4224152.7224811.46
River Rch & RM=2027,132,36655.86
 7544.63 10617.813230.3816134.5624167.9124826.06
River Rch & RM=2027,132,36407.91
 7548.2810623.2813237.4916143.5424181.37   24839
River Rch & RM=2027,132,36159.96
 7549.7710625.5213240.4116147.2324186.89 24844.3
River Rch & RM=2027,132,35912.02
 7558.3610638.4313257.1816168.4224218.63 24874.8
River Rch & RM=2027,132,35664.07
 7626.1310740.3713389.63 16335.824469.3525115.66
River Rch & RM=2027,132,35416.12
 7627.5310742.4713392.3516339.2524474.5125120.61
River Rch & RM=2027,132,35168.18
 7628.8310744.42 13394.916342.4624479.3325125.23
River Rch & RM=2027,132,34920.23
 7631.5210748.4813400.1616349.12 24489.325134.81
River Rch & RM=2027,132,34672.28
 7632.4510749.8713401.9816351.4124492.7425138.11
River Rch & RM=2027,132,34424.34
 7638.4910758.9513413.7816366.3324515.0825159.56
River Rch & RM=2027,132,34176.39
 7651.6610778.7813439.54 16398.924563.8725206.41
River Rch & RM=2027,132,33928.44
 7654.3510782.8213444.8116405.5524573.8325215.97
River Rch & RM=2027,132, 33680.5
 7661.6710793.8413459.1316423.6624600.9625242.01
River Rch & RM=2027,132,33432.55
 7663.5310796.6313462.7616428.2524607.8225248.61
River Rch & RM=2027,132, 33184.6
 7664.9210798.7313465.4816431.6924612.9825253.55
River Rch & RM=2027,132,32688.71
 7666.9610801.7913469.4616436.7324620.53 25260.8
River Rch & RM=2027,132,32440.76
  7997.211299.5314117.1117256.2125848.0226437.25
River Rch & RM=2027,132,31944.87
 7998.6511301.7214119.9617259.8225853.4426442.43
River Rch & RM=2027,132,31696.92
 8000.9211305.1414124.4217265.4625861.8926450.52
River Rch & RM=2027,132,31201.03
 8001.9211306.6514126.3817267.9525865.6126454.08
River Rch & RM=2027,132,30953.08
 8023.2211338.8114168.27   1732125945.0826530.12
River Rch & RM=2027,132,30705.14
 9002.1912822.6416106.2719781.3829630.4730040.55
River Rch & RM=2027,132,30457.19
  9003.312824.3316108.49 19784.2 29634.730044.56
River Rch & RM=2027,132,30209.25
 9009.8912834.3616121.62 19800.929659.72 30068.3
River Rch & RM=2027,132,28686.36
 9022.0312852.8416145.82 19831.729705.8530112.04
River Rch & RM=2027,132,28537.72
 9022.4612853.4916146.6719832.7829707.4730113.58
River Rch & RM=2027,132,27681.99
 9270.6813231.57 16642.120463.5830652.3431008.78
River Rch & RM=2027,132,26695.11
 9276.08 13239.816652.8920477.3330672.9331028.27
River Rch & RM=2027,132,26164.82
 9341.7413339.9416784.2220644.6530923.5631265.42
River Rch & RM=2027,132, 25514.4
 9349.2213351.3516799.1820663.7230952.1331292.43
River Rch & RM=2027,132,25267.84
 9350.1413352.7616801.0320666.0730955.6531295.77
River Rch & RM=2027,132,25021.28
 9351.7413355.1916804.2220670.1430961.7531301.53
River Rch & RM=2027,132,24774.72
 9354.6813359.68 16810.120677.6430972.9831312.15
River Rch & RM=2027,132,24528.15
 9355.94 13361.616812.6320680.8530977.7931316.71
River Rch & RM=2027,132,24281.59
 9359.9713367.7516820.6920691.1330993.1931331.27
River Rch & RM=2027,132,24035.03
 9363.41   1337316827.5820699.9131006.33 31343.7
River Rch & RM=2027,132,23788.47
  9373.9   1338916848.5720726.6631046.4131381.61
River Rch & RM=2027,132,23541.91
 9374.5713390.0316849.9120728.3831048.9831384.03
River Rch & RM=2027,132,23295.35
 9385.3913406.5316871.5720755.9831090.3231423.13
River Rch & RM=2027,132,23048.79
  9386.913408.8416874.5920759.8331096.0931428.58
River Rch & RM=2027,132,22802.22
 9392.2613417.0216885.3320773.5231116.5931447.97
River Rch & RM=2027,132,22555.66
 9393.8613419.4516888.5220777.5831122.6831453.72
River Rch & RM=2027,132, 22309.1
 9395.2813421.6316891.3720781.2131128.1331458.88
River Rch & RM=2027,132,22062.54
 9401.0613430.4516902.9520795.9731150.2231479.77
River Rch & RM=2027,132,21815.98
 9404.3313435.4316909.49 20804.331162.7131491.58
River Rch & RM=2027,132,21569.42
 9406.5913438.8916914.0220810.0831171.3631499.75
River Rch & RM=2027,132,21322.85
 9408.9413442.4616918.7120816.0631180.3231508.23
River Rch & RM=2027,132,21076.29
 9409.8613443.8716920.5620818.4131183.8531511.56
River Rch & RM=2027,132,20829.73
 9756.6513973.7917616.4221706.0632513.4532766.91
River Rch & RM=2027,132,20090.05
 9769.9713994.1717643.2121740.2632564.67 32815.2
River Rch & RM=2027,132,18857.24
 9799.1314038.7917701.8521815.1332676.8232920.93
River Rch & RM=2027,132,18117.55
 9812.0114058.5117727.7721848.2232726.3832967.64
River Rch & RM=2027,132,17131.31
 9844.3814108.0617792.91 21931.432850.9833085.06
River Rch & RM=2027,132,16391.62
 9849.71 14116.217803.6221945.0832871.4733104.37
River Rch & RM=2027,132,15651.94
 9861.33   1413417827.0221974.9532916.2233146.53
River Rch & RM=2027,132,14665.69
 9910.1114208.7117925.2622100.4333104.1733323.57
River Rch & RM=2027,132,13934.63
  9939.814254.1817985.0722176.8333218.6133431.34
River Rch & RM=2027,132,13734.21
 9940.0514254.5517985.5622177.4533219.5533432.22
River Rch & RM=2027,132,12215.93
 9987.1814326.7718080.5522298.8233401.3433603.36
River Rch & RM=2027,132,10273.63
10022.44 14380.818151.6522389.6633537.4133731.43
River Rch & RM=2027,132,6305.592
14383.7321153.5927141.5933967.1950879.3649818.38
River Rch & RM=2027,132,5976.977
14385.2921156.0427144.8733971.4450885.7349824.22
River Rch & RM=2027,132,3518.416
14465.4421281.9727313.3334189.8951212.9450123.91
River Rch & RM=2027,132,211.9789
 14561.921433.6127516.2334453.0651607.14 50484.8
Boundary for River Rch & Prof#=2027,132,1
Up Type= 0
Dn Type= 2
Boundary for River Rch & Prof#=2027,132,2
Up Type= 0
Dn Type= 2
Boundary for River Rch & Prof#=2027,132,2
Up Type= 0
Dn Type= 2
Boundary for River Rch & Prof#=2027,132,2
Up Type= 0
Dn Type= 2
Boundary for River Rch & Prof#=2027,132,2
Up Type= 0
Dn Type= 2
Boundary for River Rch & Prof#=2027,132,2
Up Type= 0
Dn Type= 2

--- 2027_ras.g01 (geometry) ---

Geom Title=2027
Program Version=4.10

River Reach=2027,132
Reach XY= 30
602676.303115786754709.874577737604005.502733141753980.772268895
604632.530132829754218.072326091606594.761495203752122.267967369
605339.504144641 751019.71202644606411.002172022746099.620844117
606189.562122792744655.529820099606913.105111957742882.538603359
604920.238614202742967.335025425605236.219926506740695.285990015
603854.550632955741295.364626799603317.109935729741076.330326353
604177.767051697739513.656970691  603185.0225372739157.719300831
603065.134197741738207.846407656604126.056150467  737732.6677995
   603995.202896 736390.01432978 604647.41933021735103.881957744
603504.308833509733954.892811423603280.841321111 732657.06010427
604369.961639792730455.403573183604169.673416854729228.330311423
603269.065777956728466.611561443602079.156791927725894.267959573
599517.980708717723227.896283642599669.890430956722506.325103094
600831.491154881721640.813246423600843.544867428719558.792551984
 599301.32454589713034.559509477598347.129520149705381.852665541

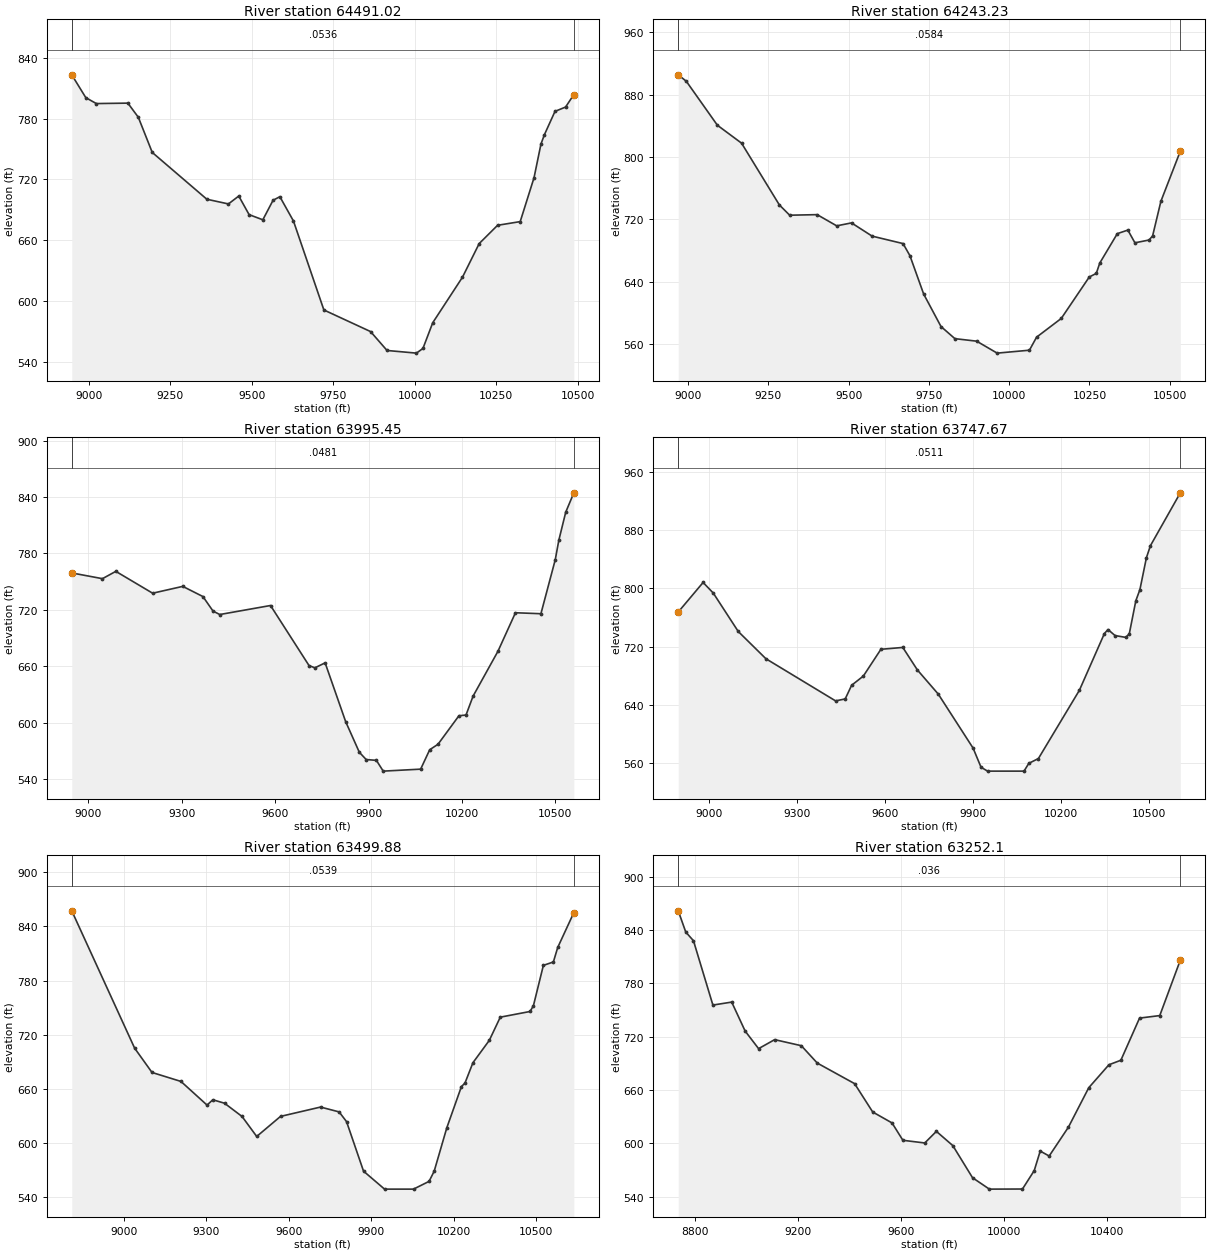
Type RM Length L Ch R = 1 ,64491.02,247.783700,247.783700,247.783700
XS GIS Cut Line= 6
602972.438183099755715.001595527602842.148563802755377.730276331
602729.528179139755030.984981969602682.711683065754815.575422615
602653.566278219754524.943339258602553.365404861754241.604475722
#Sta/Elev= 30
 8947.31823.29978990.414 800.7439022.741794.92349119.451795.3593 9151.51781.4175
9194.257746.69139361.842700.46599428.044695.83769459.753703.63539491.462 685.272
9533.627680.18719564.946699.44479585.825702.99319627.584678.9806 9720.92591.1632
9864.203 569.8339914.751551.168710004.93548.555310024.93553.189610054.99 578.585
10146.19623.4995 10197.5656.711110253.92674.755810323.37678.393210365.83721.7699
10387.05754.954810397.66764.206310430.11787.218710462.61791.495610487.96803.8118
#Mann= 3 , 0 , 0
 8947.31  0.0536       0 8947.31  0.0536       010487.96  0.0536       0
#XS Ineff= 2 , 0
       0                               0
Bank Sta=8947.31,10487.96
Exp/Cntr=0.3,0.1

Type RM Length L Ch R = 1 ,64243.23,247.783800,247.783800,247.783800
XS GIS Cut Line= 6
603293.153585434755598.377812847603018.476949751 754884.49992846
602965.689650089754755.867102429602863.942169756754546.297387362
602760.760811418754310.085022032602689.503859256754156.816490966
#Sta/Elev= 30
8969.165905.31968994.305897.05659091.087840.70189166.363817.73239284.156738.5166
9316.255725.36819401.852726.08019462.694711.72839508.849715.50729573.047 698.535
9669.343688.98619690.743673.50069733.541624.29439787.582582.62769830.819567.1114
9898.686563.87589962.424548.555310062.94   552.310085.25569.015510162.08593.0053
10249.38646.160810271.21650.758810282.12664.074510336.68701.714610369.48706.2961
10391.53 689.97510435.64693.569710446.67698.916510472.45743.246210532.89807.4213
#Mann= 3 , 0 , 0
8969.165  0.0584       08969.165  0.0584       010532.89  0.0584       0
#XS Ineff= 2 , 0
       0                               0
Bank Sta=8969.165,10532.89
Exp/Cntr=0.3,0.1

Type RM Length L Ch R = 1 ,63995.45,247.783700,247.783700,247.783700
XS GIS Cut Line= 6
603545.487169862755506.620145783603343.617557257755002.836529836
603110.989763856754481.374873057603062.449756473754382.727553114
603000.207592577754267.898897991602871.833127249754043.260543355
#Sta/Elev= 30
8946.579759.31839045.103753.21789088.117760.99539206.406737.75969303.188745.0283
9367.963734.19899400.421718.74119422.059715.09479585.114724.67979708.773660.8378
9727.547658.40099760.534663.68949826.507601.21249870.489568.5744 9892.48560.8771
9925.308559.99959947.139548.555310067.44550.661310096.55 571.30910123.16577.1135
10190.44607.433510213.19 608.22110235.94628.344510315.73675.988410372.02716.9808
10453.84715.949510499.87773.327810511.38 794.09710533.62824.010910559.62844.5084
#Mann= 3 , 0 , 0
8946.579  0.0481       08946.579  0.0481       010559.62  0.0481       0
#XS Ineff= 2 , 0
       0                               0
Bank Sta=8946.579,10559.62
Exp/Cntr=0.3,0.1

Type RM Length L Ch R = 1 ,63747.67,247.783700,247.783700,247.783700
XS GIS Cut Line= 6
603827.118720839755404.208672696603638.909710288754917.077724323
603503.311319947754640.602087602   603394.433339754472.648712024
603170.803720772754173.348886684603002.492414922753919.553906798
#Sta/Elev= 30
8896.622767.43298981.283808.0867 9015.92793.47719100.893740.65549195.049703.1691
9432.085645.19599464.889647.85999486.759666.67219526.637679.33799586.395716.1433
 9660.95718.71219710.571687.73859781.672654.51339900.156580.21989927.212553.9123
9949.468548.555310073.51548.555310089.83 559.27710122.46 565.86710261.93659.7552
10346.97737.759710359.25743.349510383.38735.037810419.59 732.56710431.66 737.209
10454.12783.055710467.87798.152310490.06842.111610503.78858.723110605.44931.4009
#Mann= 3 , 0 , 0
8896.622  0.0511       08896.622  0.0511       010605.44  0.0511       0
#XS Ineff= 2 , 0
       0                               0
Bank Sta=8896.622,10605.44
Exp/Cntr=0.3,0.1

Type RM Length L Ch R = 1 ,63499.88,247.783700,247.783700,247.783700
XS GIS Cut Line= 6
604028.044031733755331.144923281 603813.19475466754705.686272815
603718.426118642  754498.8968907603603.961674541754329.947792798
 603312.64019838753983.648400888603152.528790891753753.050123721
#Sta/Elev= 30
8810.122857.39089038.833704.99769102.059 678.0239207.434668.06549302.272641.8262
9323.442647.7195 9365.95643.88569429.713629.16569483.039606.98339569.669629.2626
9715.311639.63189782.875634.25429809.951623.44249871.735568.50359948.195548.5553
10053.53548.555310110.15557.150810128.79568.465810174.75 616.64810227.85662.3367
10240.72666.167510269.74 688.80910329.35 713.65210369.28739.387510477.56745.6847
10489.79751.998410526.09796.856610562.48800.644210578.26816.715610636.95855.4362
#Mann= 3 , 0 , 0
8810.122  0.0539       08810.122  0.0539       010636.95  0.0539       0
#XS Ineff= 2 , 0
       09766.201                       0
Bank Sta=8810.122,10636.95
Exp/Cntr=0.3,0.1

Type RM Length L Ch R = 1 , 63252.1,247.783800,247.783800,247.783800
XS GIS Cut Line= 6
604133.684487981755292.730211918604027.790132999754952.788332954
603905.288975745754498.509135172603831.607869804754300.893703073
603688.577884734754022.665889323603383.782491535753506.591937259
#Sta/Elev= 30
8736.043861.47858765.269837.62238795.203827.83738870.647755.51918943.707758.8624
8995.893726.28249048.079706.52369110.542 716.6469214.013 709.8399276.096690.2718
9420.955667.17179491.348635.27469566.357622.98569608.536603.46579693.512600.4558
 9738.59613.51319802.501597.46349878.987561.38129944.334548.555310072.96548.6777
10118.65569.434610141.85591.335510176.65585.784310251.44618.251710330.35662.5616
10408.67688.395610455.07693.473710527.63740.866110606.12743.687710685.92806.0047
#Mann= 3 , 0 , 0
8736.043   0.036       08736.043   0.036       010685.92   0.036       0
#XS Ineff= 2 , 0
       09751.252                       0
Bank Sta=8736.043,10685.92
Exp/Cntr=0.3,0.1

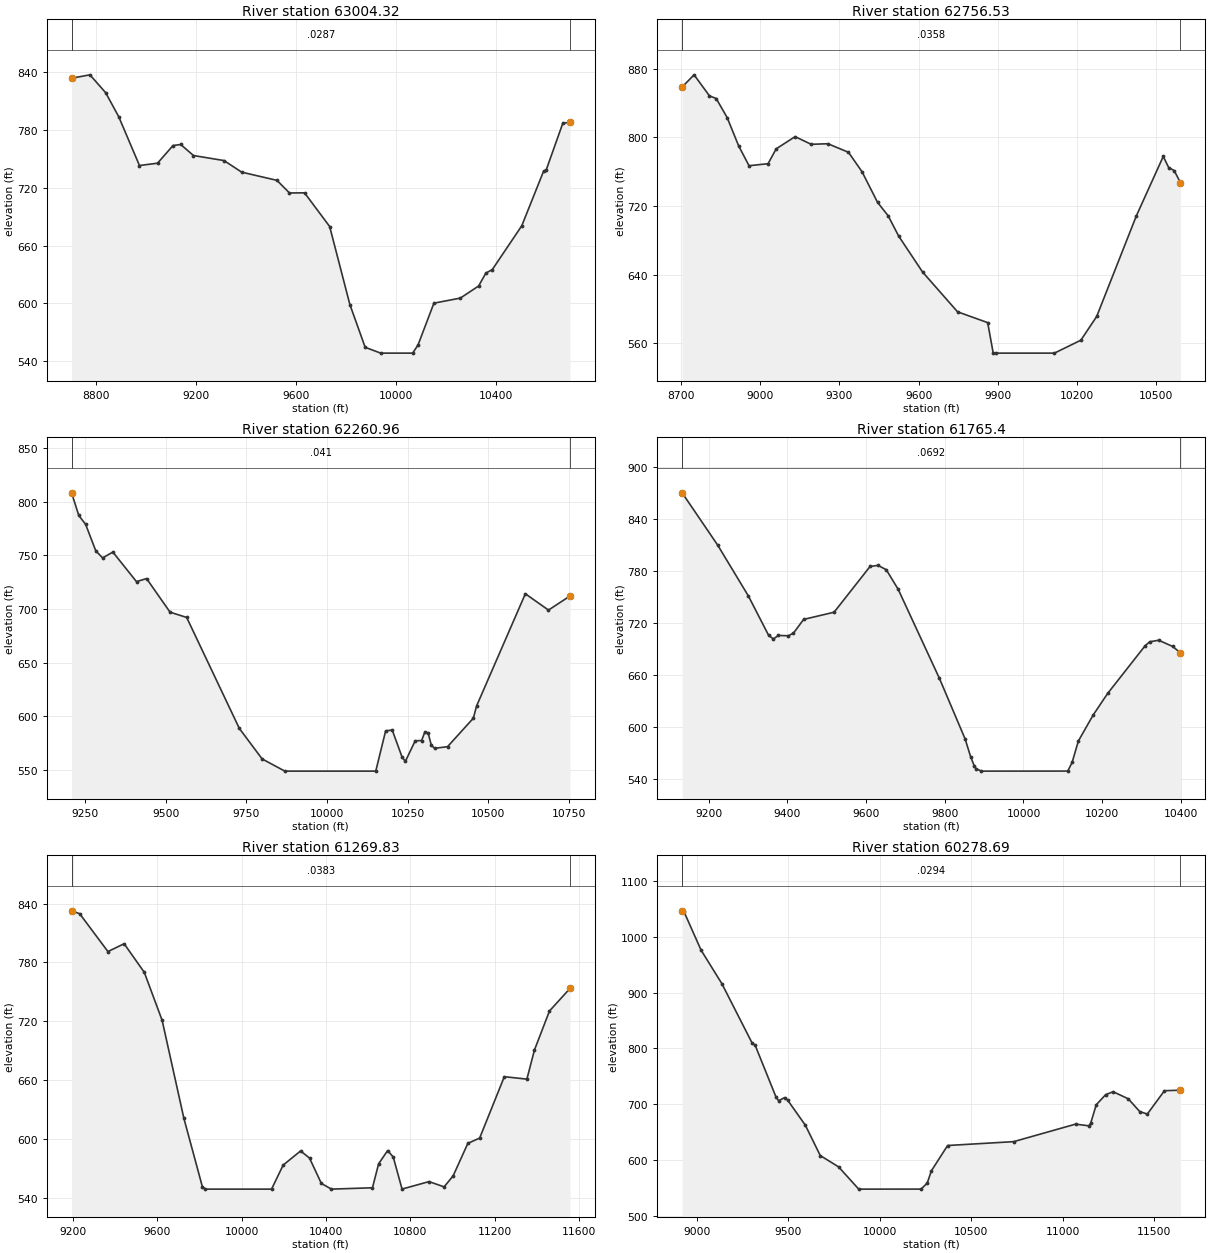
Type RM Length L Ch R = 1 ,63004.32,247.783700,247.783700,247.783700
XS GIS Cut Line= 6
604210.142424128755264.927326046 604070.24978137754736.725380957
604010.461076349754216.162304014603981.623658478754072.830265969
603841.829955727753676.796728387603703.869783133753349.447741255
#Sta/Elev= 30
8702.672833.31158776.035836.82218838.982818.28788891.071793.49658974.134742.8737
9046.424745.29489108.153763.56049138.981764.67849190.016753.24279312.085748.0228
9382.882736.00889523.835727.52129574.015714.44769634.232714.59159734.665679.7002
9815.411598.90619876.662554.5816 9938.79548.555310066.59548.555310087.93556.9638
10151.44600.300710257.29605.5684 10330.4618.124310359.11 631.42610384.85635.0662
10502.78680.440810589.82736.851510600.71738.401510666.87786.6611 10695.5787.7088
#Mann= 3 , 0 , 0
8702.672  0.0287       08702.672  0.0287       0 10695.5  0.0287       0
#XS Ineff= 2 , 0
       0                               0
Bank Sta=8702.672,10695.5
Exp/Cntr=0.3,0.1

Type RM Length L Ch R = 1 ,62756.53,495.567400,495.567400,495.567400
XS GIS Cut Line= 6
604256.763126799755247.974343257604146.260378987754840.906280711
604111.253657281754583.915969789604114.115859598754388.849351048
604212.895170927753789.407961324604168.195011407753391.641656116
#Sta/Elev= 30
 8703.79858.54738749.099872.73588807.363848.23228832.853845.15278874.432822.9577
8917.852790.04848957.287766.8444 9029.44769.21829060.182786.52229131.869800.7338
9192.853791.79919256.135792.47169334.092782.49869385.392759.87999444.355724.1314
9484.355708.58579524.389684.8445 9614.88 643.0149747.405596.68549861.562584.0866
9882.326548.86749892.708548.555310114.37548.555310214.52563.600310274.55591.2455
10425.07708.623610526.82777.701710547.31764.706210567.97761.2262 10592.1747.1242
#Mann= 3 , 0 , 0
 8703.79  0.0358       0 8703.79  0.0358       0 10592.1  0.0358       0
#XS Ineff= 2 , 0
       0                               0
Bank Sta=8703.79,10592.1
Exp/Cntr=0.3,0.1

Type RM Length L Ch R = 1 ,62260.96,495.567500,495.567500,495.567500
XS GIS Cut Line= 6
604710.535100891755035.920721651 604615.13823992754732.926187545
604560.505168527754434.613336533604538.996672511754199.156330153
604581.665338486 753849.11591357604530.319321096753520.381792217
#Sta/Elev= 30
9208.452 808.5199230.747787.38799251.979779.06159283.633754.23759304.735747.7214
9336.388753.17959409.697725.54839440.891728.43829513.678697.03379565.196692.1151
9728.363 588.4749799.087 559.9479869.555548.555310151.32548.555310181.93586.1744
10202.34586.9178 10232.9561.675110243.04557.637310273.53576.853610293.53577.1598
10303.57585.229210313.61584.200910323.66572.6366 10333.7 569.867 10373.8 571.388
10453.85598.010110463.86609.432810615.03714.224710686.68698.987210753.27712.1485
#Mann= 3 , 0 , 0
9208.452   0.041       09208.452   0.041       010753.27   0.041       0
#XS Ineff= 2 , 0
       0                10265.62       0
Bank Sta=9208.452,10753.27
Exp/Cntr=0.3,0.1

Type RM Length L Ch R = 1 , 61765.4,495.567400,495.567400,495.567400
XS GIS Cut Line= 6
605489.824535766754617.911063103 605324.69792372754406.137003675
605178.857822061754229.584332138604842.042106301753863.240726292
604756.237257272753745.950953558604696.346295387753635.970192045
#Sta/Elev= 30
9132.906869.74319222.904809.62939301.077750.81899352.472705.41289364.717701.0758
9377.445705.14759402.919 704.7799415.806707.86199441.581723.66179518.907731.9491
  9610.3784.7227 9630.46786.04229651.476781.01519681.805758.35059786.577655.5174
9851.828585.64169865.647565.35099874.763554.79769879.491 551.3769893.336548.5553
10112.51548.617910123.71558.765810139.45583.330910177.16613.412310214.09638.3661
10309.16693.340310320.65697.864110343.63699.597610379.25692.390310398.88684.9575
#Mann= 3 , 0 , 0
9132.906  0.0692       09132.906  0.0692       010398.88  0.0692       0
#XS Ineff= 2 , 0
       0                               0
Bank Sta=9132.906,10398.88
Exp/Cntr=0.3,0.1

Type RM Length L Ch R = 1 ,61269.83,991.135000,991.135000,991.135000
XS GIS Cut Line= 6
605862.174049139754166.563427374605451.702046335753767.176200658
 605079.36427328753422.401415676604929.983543545753274.300131574
604725.152141362753062.177322507604169.123349011752517.059262425
#Sta/Elev= 30
9193.447832.73419231.763829.78979365.876791.13419442.735799.13279538.315769.9459
9622.966720.94989726.007620.96359813.681551.14659828.444548.555310142.03548.5553
10197.07573.098810279.78587.528710322.03580.299510378.36554.354610426.19548.5553
10620.73549.940410649.83574.384510692.71587.960810719.34581.307710761.04548.6168
10889.11556.244410960.53550.864511003.39562.100511073.17595.297911129.18600.6949
11246.22663.370511353.25660.868511389.06690.576711460.49 730.49511557.54753.4625
#Mann= 3 , 0 , 0
9193.447  0.0383       09193.447  0.0383       011557.54  0.0383       0
#XS Ineff= 2 , 0
       0                10229.63       0
Bank Sta=9193.447,11557.54
Exp/Cntr=0.3,0.1

Type RM Length L Ch R = 1 ,60278.69,991.134900,991.134900,991.134900
XS GIS Cut Line= 6
606733.354672971753464.681062383606007.656077176 752910.23588343
605582.189732373752654.260231867605290.554136693752541.664417386
604697.201402485752400.955162212604321.499717027752293.507023007
#Sta/Elev= 30
8920.5431046.1428930.8861044.4439024.173975.80179137.383916.15149301.938810.5085
9319.583805.88599433.841713.14559448.027706.57579480.491712.16799496.723707.9058
9594.115 662.8479675.483608.59979775.764588.37089885.816548.555310226.18548.6093
10260.34559.2807 10282.8581.210910371.68 626.55310732.43633.440911071.19664.7674
11142.96661.764211153.24665.907211184.06699.367411235.43717.470211276.64722.6638
11359.24710.014711421.48687.321811463.07682.726711556.99724.536311644.58725.4356
#Mann= 3 , 0 , 0
8920.543  0.0294       08920.543  0.0294       011644.58  0.0294       0
#XS Ineff= 2 , 0
       0                               0
Bank Sta=8920.543,11644.58
Exp/Cntr=0.3,0.1

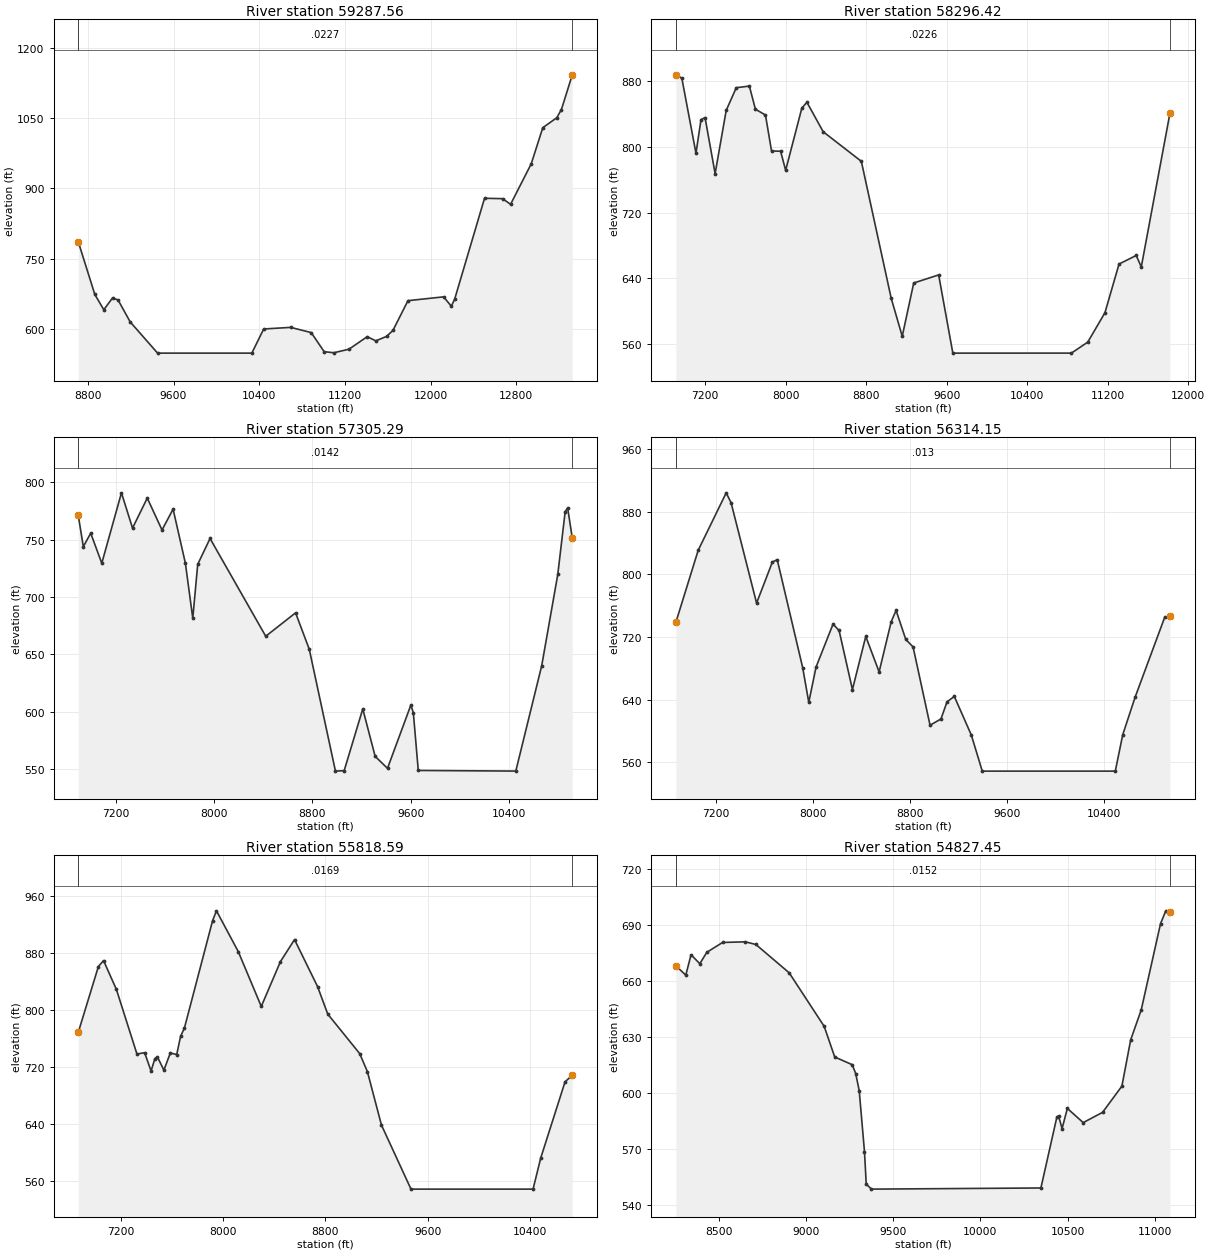
Type RM Length L Ch R = 1 ,59287.56,991.134900,991.134900,991.134900
XS GIS Cut Line= 6
607816.754978091752482.636024594606772.648435563   752235.320758
606510.889364421 752115.91259484605226.495394021752274.496017128
604548.206127882752246.474341422603341.885917574751841.199319229
#Sta/Elev= 30
8710.015786.19978864.779673.67418948.646641.10249030.809666.30579082.161661.7631
9195.007615.15049451.174548.555310331.17548.555310441.91600.013810693.78603.4558
10885.57592.372811006.69551.627611097.46549.371911238.43556.951111409.01583.6626
11489.11574.739511589.13584.121611649.14597.040711789.28660.378712122.41668.5501
12193.69648.595912224.55662.980912504.36878.664312673.21877.828312747.55865.7543
12940.42952.075913048.491029.13913178.751050.25813222.341067.82513323.821141.827
#Mann= 3 , 0 , 0
8710.015  0.0227       08710.015  0.0227       013323.82  0.0227       0
#XS Ineff= 2 , 0
       0                               0
Bank Sta=8710.015,13323.82
Exp/Cntr=0.3,0.1

Type RM Length L Ch R = 1 ,58296.42,991.134900,991.134900,991.134900
XS GIS Cut Line= 6
608624.126219988750835.954580769606772.309963405750957.282819986
606195.002622813 751227.51435177605384.918987989 752052.22463575
604847.370678782752173.376587421   604176.174658752098.799662337
#Sta/Elev= 30
6910.862888.05576970.155 883.886  7110.5792.42787160.567833.33877200.621835.9044
7300.719767.56017410.762844.67687510.772  872.347640.782874.32567700.796846.1311
7800.863838.98437860.928795.21957951.115794.81798001.245771.57628161.992847.4744
 8212.38854.59468374.003818.61488752.873782.53319049.184615.62999159.122569.0896
9273.076634.10789520.773643.94919661.657548.555310839.13548.579911001.63561.9747
11172.22597.809111312.28657.247311482.89667.684111533.28 653.70311817.49840.9724
#Mann= 3 , 0 , 0
6910.862  0.0226       06910.862  0.0226       011817.49  0.0226       0
#XS Ineff= 2 , 0
       09471.938                       0
Bank Sta=6910.862,11817.49
Exp/Cntr=0.3,0.1

Type RM Length L Ch R = 1 ,57305.29,991.134900,991.134900,991.134900
XS GIS Cut Line= 6
608446.250406086750664.158168241607846.359226435750649.014270812
607422.242034227750668.306433529 605840.76639685750874.708882704
605463.393063575750862.779071599 604447.52549535750761.057304978
#Sta/Elev= 30
6895.476771.10486936.806743.78486996.905755.53337086.977729.36447247.053790.6208
7337.067759.92037457.068786.04687577.095758.2843 7667.14776.46237767.249729.3449
 7827.36681.48087867.449728.40447967.741750.91228420.828665.86898663.718686.2454
8775.194654.4846 8988.01548.55539058.949548.95579210.379602.67849311.174561.3682
9411.609551.00039601.811606.07629621.815599.26679661.827549.141810455.34548.5878
10666.28640.341510796.86719.602210857.12 774.35910877.21777.456710914.85751.2809
#Mann= 3 , 0 , 0
6895.476  0.0142       06895.476  0.0142       010914.85  0.0142       0
#XS Ineff= 2 , 0
       09549.383                       0
Bank Sta=6895.476,10914.85
Exp/Cntr=0.3,0.1

Type RM Length L Ch R = 1 ,56314.15,495.567400,495.567400,495.567400
XS GIS Cut Line= 6
608938.386974424750227.568055838608000.271163881 750161.41012305
606386.046131104750137.165060446605989.834425271750061.285301328
 605407.53777203749880.585465193604912.925929576749782.698575139
#Sta/Elev= 30
 6869.75 738.7817054.072  830.997284.883904.35967324.982891.69817535.411 763.372
 7665.58815.8642 7705.61818.89547915.724680.6857 7965.74636.53498025.745681.6053
8165.749736.4932 8215.75728.35048325.754652.8144 8435.76720.77778545.765675.4082
 8645.77739.79118685.772753.98418765.776716.87168825.777707.37198965.777607.2248
9055.785 615.2419105.808637.12989165.851644.0686 9306.05594.72839396.438548.5553
10493.31548.555310554.88595.124910656.95643.158610901.07745.344110943.72746.4478
#Mann= 3 , 0 , 0
 6869.75   0.013       0 6869.75   0.013       010943.72   0.013       0
#XS Ineff= 2 , 0
       09602.572                       0
Bank Sta=6869.75,10943.72
Exp/Cntr=0.3,0.1

Type RM Length L Ch R = 1 ,55818.59,991.134900,991.134900,991.134900
XS GIS Cut Line= 6
608891.758892646749514.165966503607714.421738287749407.844765358
606657.193687175749380.325367065606121.985514243749432.892431055
605488.261951237749599.731930545605058.298562849749608.625243325
#Sta/Elev= 30
6866.288768.82477024.021861.5137 7064.27869.83257164.804829.27427325.555738.5052
7385.837740.33647436.071714.52247466.212732.16527486.306734.20227536.521715.7934
7586.694739.96097636.868 737.7917666.973 763.3287697.077775.0333 7917.64926.0484
7947.715939.77678118.072882.58098298.341805.39858448.486868.46748558.564899.3581
8738.622833.33028818.636 794.5819068.658739.01599128.686713.74349238.799638.5539
9469.796548.555310424.79548.555310484.85592.275610674.94699.307910731.73708.7154
#Mann= 3 , 0 , 0
6866.288  0.0169       06866.288  0.0169       010731.73  0.0169       0
#XS Ineff= 2 , 0
       0                               0
Bank Sta=6866.288,10731.73
Exp/Cntr=0.3,0.1

Type RM Length L Ch R = 1 ,54827.45,495.567500,495.567500,495.567500
XS GIS Cut Line= 6
607401.601516424748764.056481715606061.971584439748626.187468395
605834.477859497748593.236277074605466.785685509748524.787289411
605201.276061803748482.255683109604591.582632184 748403.07331036
#Sta/Elev= 30
8253.109668.08798310.041663.08678340.217673.98978390.509669.20698430.743675.3201
8521.268680.57388651.954680.91638712.243679.48448903.159664.33319104.123635.6629
9164.412619.28739264.894 615.1439284.991610.40039305.087601.14699335.232568.6404
 9345.28551.24499375.448548.555310347.32549.169410438.47586.943910448.59587.7389
10468.85580.958310499.14591.752710589.98584.1493   10701589.634210812.03 603.675
10862.44628.458910922.87644.469811033.65 690.61811063.87697.506611087.45696.9974
#Mann= 3 , 0 , 0
8253.109  0.0152       08253.109  0.0152       011087.45  0.0152       0
#XS Ineff= 2 , 0
       0                10391.63       0
Bank Sta=8253.109,11087.45
Exp/Cntr=0.3,0.1

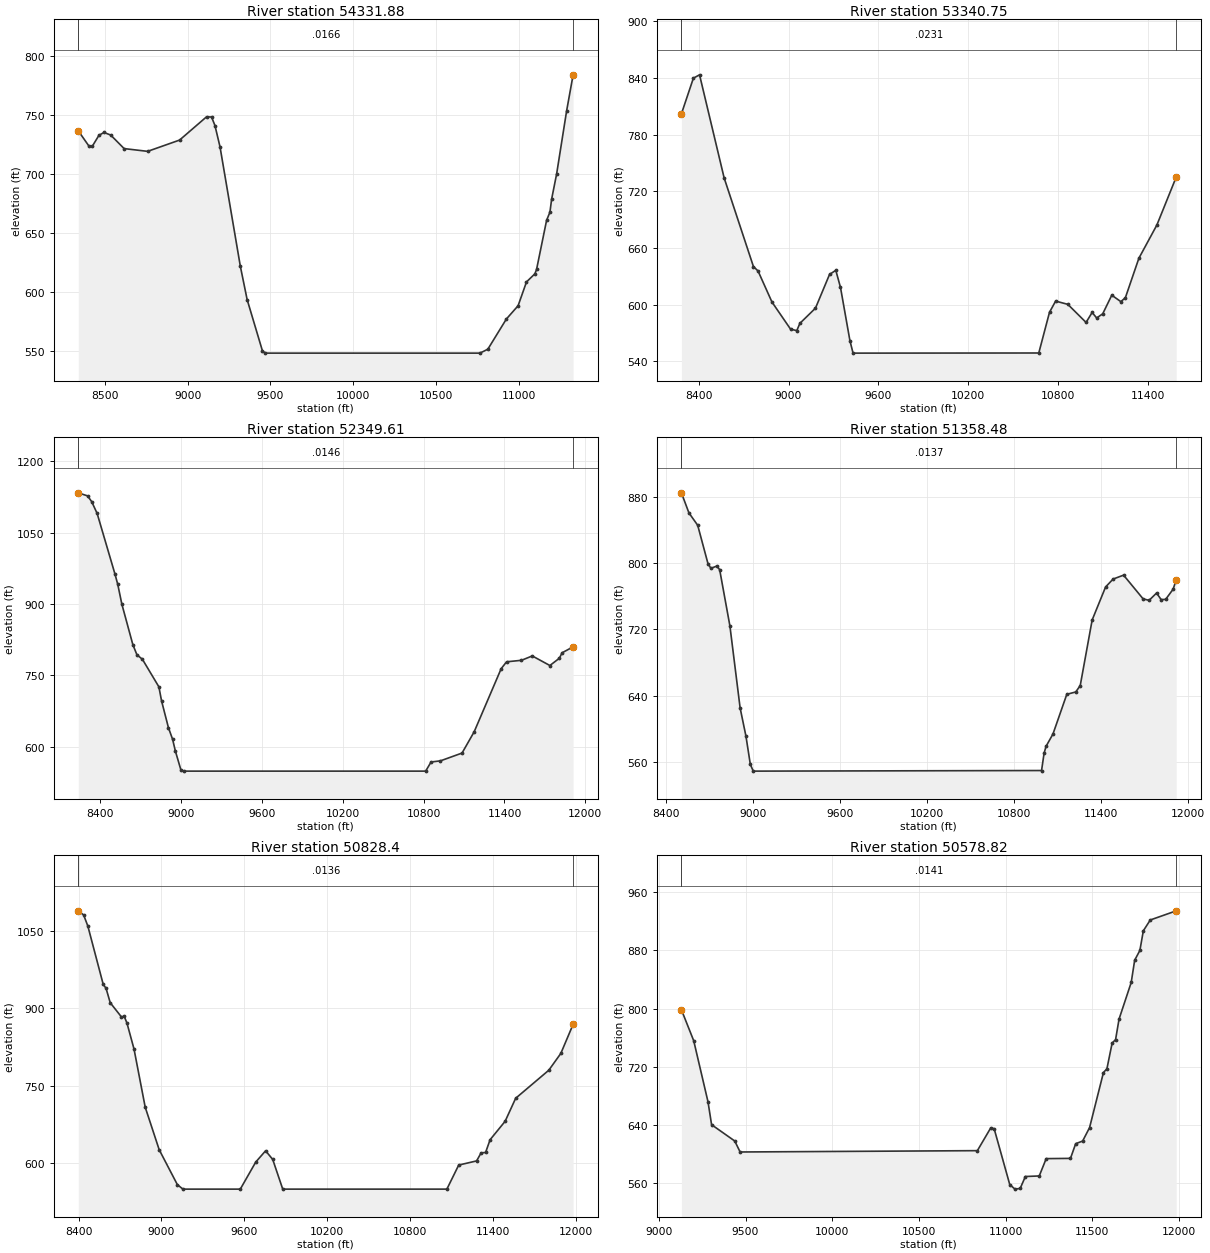
Type RM Length L Ch R = 1 ,54331.88,991.134900,991.134900,991.134900
XS GIS Cut Line= 6
607398.493743717748420.647597505606948.201859087 748347.61039865
606456.268323332748253.378153503605208.404209048747932.355442539
604858.591043353 747862.24319604604476.282693535747804.712337941
#Sta/Elev= 30
8339.644736.54998403.914723.67928424.159723.48328464.648732.78768495.015735.1671
8535.504732.97228616.559721.52858758.515719.19418951.468728.72939114.316748.3856
9144.868748.22039165.264741.00449195.902722.98819318.554622.04399359.589593.8791
9451.919550.5416 9468.67548.555310765.81548.555310813.62551.864510925.53577.3756
10996.52588.634611047.18  608.7711097.84615.614311107.97 619.28411168.68660.8917
11188.88667.788611198.99678.725511229.29700.108111289.83753.600111328.87783.9114
#Mann= 3 , 0 , 0
8339.644  0.0166       08339.644  0.0166       011328.87  0.0166       0
#XS Ineff= 2 , 0
       0                               0
Bank Sta=8339.644,11328.87
Exp/Cntr=0.3,0.1

Type RM Length L Ch R = 1 ,53340.75,991.134900,991.134900,991.134900
XS GIS Cut Line= 6
607733.212540059747612.355882607606860.273097485747395.378964931
605909.920035392747077.028169155605527.759848684746965.471948028
605085.268409938746879.648116589604536.034691036746832.343373552
#Sta/Elev= 30
8285.084802.07768365.085839.93618406.096843.45948570.215734.26328765.695640.3426
8796.596635.59738889.513  602.699013.663573.94949055.171572.41079075.953580.1172
9179.866 596.2059273.826631.95239315.597636.31149346.925618.14929409.747561.8434
9430.739548.555310670.39548.694210742.03 591.88110782.82603.693910864.37600.2376
10985.94581.070611026.46591.647411056.76585.811911097.11590.224611157.57609.9537
11217.93603.1343 11248.1607.173611338.44649.091711458.73684.348511587.85  735.23
#Mann= 3 , 0 , 0
8285.084  0.0231       08285.084  0.0231       011587.85  0.0231       0
#XS Ineff= 2 , 0
       0                10421.81       0
Bank Sta=8285.084,11587.85
Exp/Cntr=0.3,0.1

Type RM Length L Ch R = 1 ,52349.61,991.134800,991.134800,991.134800
XS GIS Cut Line= 6
608112.539913744746540.109495401606679.777193695746265.007103309
606088.535109192 746136.87193723605804.570050538746120.273597777
605353.733146042746124.959059268604483.596956394 746196.21296434
#Sta/Elev= 30
8236.2551133.7518305.0281127.3158335.5761115.3518376.3071090.3258508.682  962.84
8529.047941.55128559.595899.74028641.056814.73548671.604793.17398712.335783.7286
8834.527 725.8248854.892695.64888905.806639.58128936.354615.57288956.719591.0654
 8997.45551.65679017.815548.555310814.97548.555310854.97 567.73610924.99570.1932
 11085.1586.5576 11175.2631.334411375.57764.043611415.71778.434711526.13781.5862
11606.43790.773411737.07770.631911807.48785.900111827.59797.376411909.61809.8596
#Mann= 3 , 0 , 0
8236.255  0.0146       08236.255  0.0146       011909.61  0.0146       0
#XS Ineff= 2 , 0
       0                               0
Bank Sta=8236.255,11909.61
Exp/Cntr=0.3,0.1

Type RM Length L Ch R = 1 ,51358.48,530.077700,530.077700,530.077700
XS GIS Cut Line= 6
607726.237021166745300.231268361606922.353289708745205.543337275
606668.585364101745198.543352031606396.784321315745215.281879285
605381.207746266745386.508606654604364.483326244745639.991408166
#Sta/Elev= 30
8503.124885.16638554.946860.94178615.531845.90838686.212 799.6668706.407793.8201
8746.796796.57218766.991792.2853 8837.67724.27388908.195624.99848948.495590.8031
 8978.72556.67858998.864548.555310988.06549.278411005.42570.073811018.74578.4705
11066.88593.500111162.21641.477511223.93644.297511254.82652.0302 11337.2731.3933
11429.88771.304711481.55780.853811553.99785.599711688.51756.9376 11729.9755.1201
11781.72763.972611812.89 756.04611844.05756.2728   11896768.666711917.32780.0647
#Mann= 3 , 0 , 0
8503.124  0.0137       08503.124  0.0137       011917.32  0.0137       0
#XS Ineff= 2 , 0
       09439.586                       0
Bank Sta=8503.124,11917.32
Exp/Cntr=0.3,0.1

Type RM Length L Ch R = 1 , 50828.4,249.587000,249.587000,249.587000
XS GIS Cut Line= 6
 607763.22234432744990.479186926606561.121933595744802.476028939
606113.595723515744699.587471569605804.052721864744692.138990403
605271.597320525744807.377209067604303.394956293745207.529594169
#Sta/Elev= 30
8397.8931089.7628436.5981081.7218466.977 1060.218578.366 946.6818598.619939.2177
8628.997911.08228710.008 883.476 8730.26 884.7058750.306871.29068801.144821.0392
8882.154707.92998983.361625.12429114.897557.2301 9155.37548.55539570.214548.5553
 9681.99601.18269753.321623.10549804.721606.34749877.348548.555311065.05548.5553
11150.65 595.33911280.07603.425311312.62619.005911345.16619.8483 11377.7644.6229
11486.52680.493111562.78725.240311802.45779.7697 11889.6812.4934 11978.5869.0567
#Mann= 3 , 0 , 0
8397.893  0.0136       08397.893  0.0136       0 11978.5  0.0136       0
#XS Ineff= 2 , 0
       09783.722                       0
Bank Sta=8397.893,11978.5
Exp/Cntr=0.3,0.1

Type RM Length L Ch R = 1 ,50578.82,754.321800,754.321800,754.321800
XS GIS Cut Line= 6
607084.001427143744299.301099808  606438.1680938744452.078877584
606170.806982755744472.912210912605889.556982696744434.717766464
605413.862538248744257.634433136604285.390316009744278.467766464
#Sta/Elev= 30
9130.499798.61619201.512755.96239283.845672.07379304.428640.68549438.111618.2303
9468.909603.171710836.69 604.99310913.42636.127210933.42635.180811023.44558.4048
11053.45552.141711083.45553.074411113.46569.471111193.47570.241111233.48 594.048
 11373.5594.3793 11403.5614.578511443.51618.189811483.52636.637511563.53712.3198
11583.54717.502511613.54752.686211633.54757.640911653.55785.773611723.56836.0488
11743.56866.637311773.57880.065111793.57907.114711833.58921.925611983.21934.4914
#Mann= 3 , 0 , 0
9130.499  0.0141       09130.499  0.0141       011983.21  0.0141       0
#XS Ineff= 2 , 0
       09808.761        10850.67       0
Bank Sta=9130.499,11983.21
Exp/Cntr=0.3,0.1