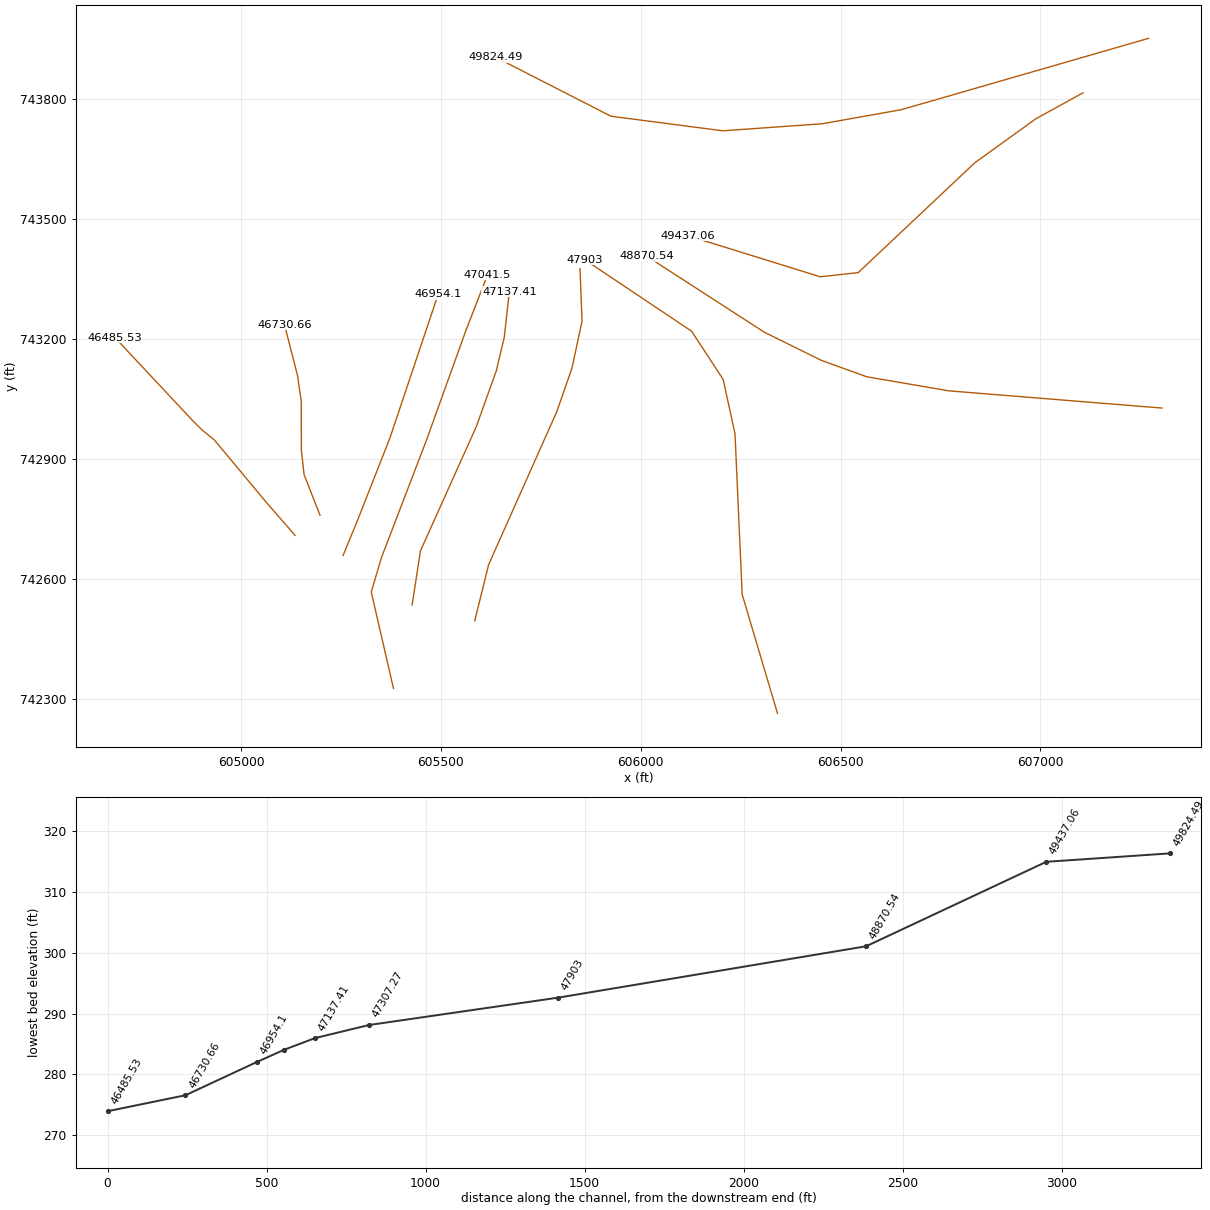
HEC-RAS study 2027_ras.prj: 2027

--- 2027_ras.g01 (geometry) --- (continued)

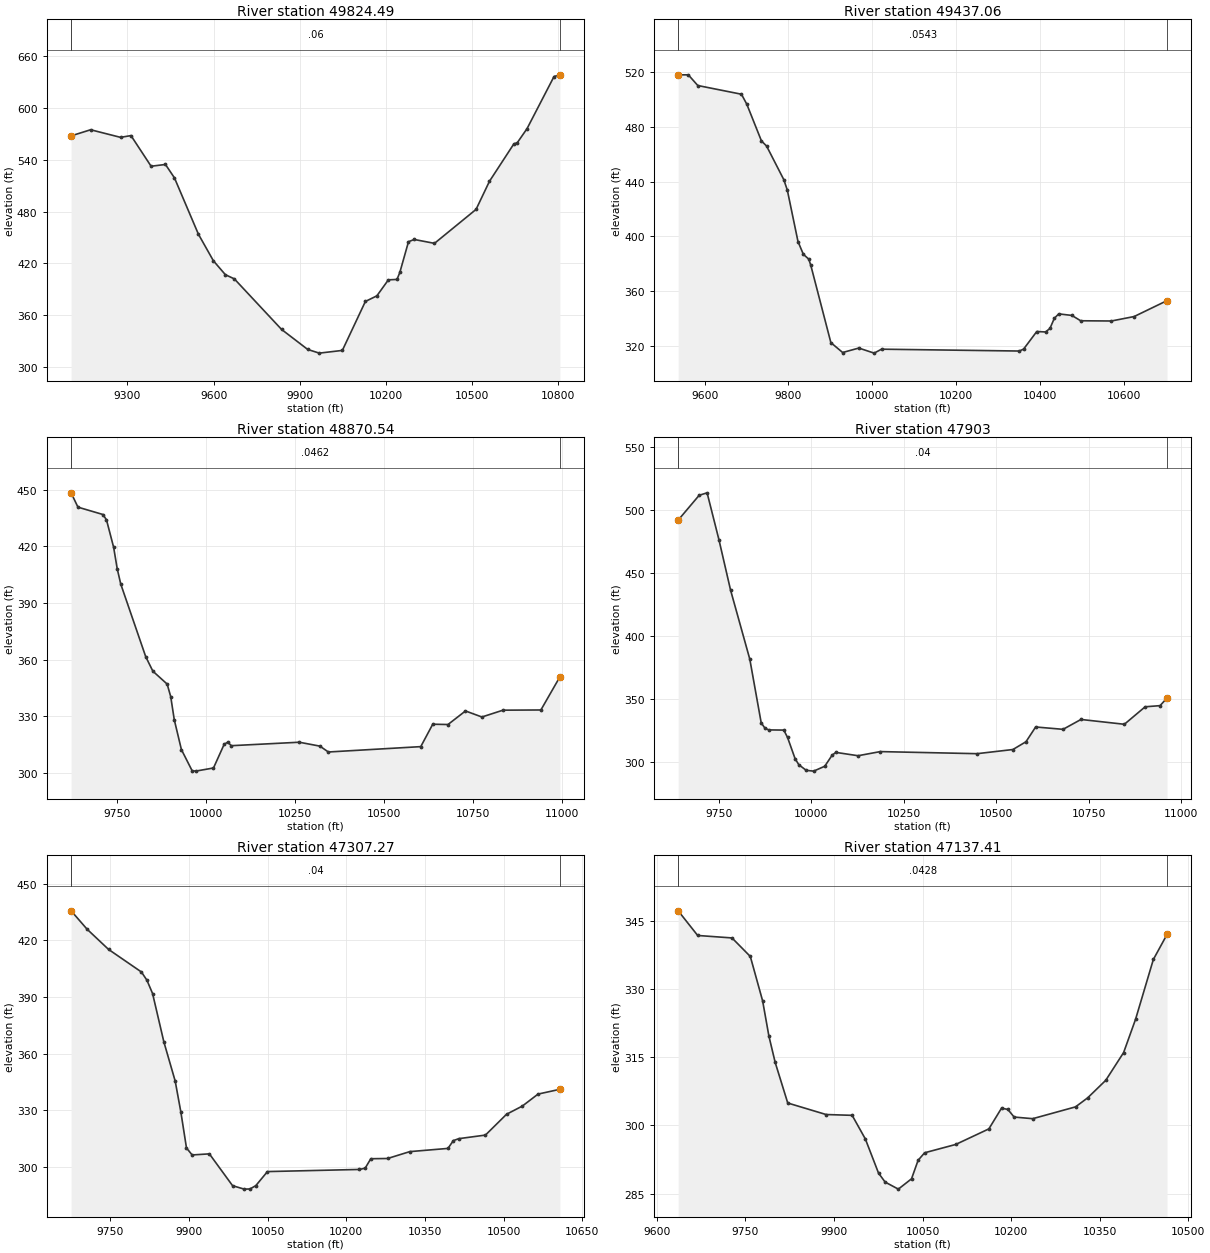
Type RM Length L Ch R = 1 ,49824.49,387.434000,387.434000,387.434000
XS GIS Cut Line= 6
607270.610931013743952.083787223606651.950358234743773.550239187
606454.522269507743738.434404857606205.394055554743720.723072025
605925.533076412743757.220278824 605637.68437339743904.364002112
#Sta/Elev= 30
9103.678567.43969171.699574.52519275.756565.73489312.167567.76579382.253532.3512
9432.263534.40879463.565518.92329547.036453.79629599.205423.0879 9640.94 407.009
9672.151402.18849836.541343.79039927.624320.63979967.925316.381310048.28 319.514
10128.47376.0918 10168.5382.580510208.52401.071310238.52401.536110248.52409.7138
10278.57445.1308 10298.6447.721410369.09443.236910513.92482.496510560.52 514.946
10645.47558.170210657.42559.542410691.32575.735810785.35636.029610805.93637.9936
#Mann= 3 , 0 , 0
9103.678    0.06       09103.678    0.06       010805.93    0.06       0
#XS Ineff= 2 , 0
       0                               0
Bank Sta=9103.678,10805.93
Exp/Cntr=0.3,0.1

Type RM Length L Ch R = 1 ,49437.06,566.516500,566.516500,566.516500
XS GIS Cut Line= 6
607106.503564836743815.832849097606988.598499215743750.834367062
 606835.79658123743640.776558617606544.192605809743366.074412546
606449.218539208743355.470846593606118.322791874 743458.27340889
#Sta/Elev= 30
9536.992 517.783 9561.12517.80859583.758510.01969687.901503.67279700.694496.3852
9735.633469.60789747.819465.93659788.807441.4897 9797.25433.89929822.812396.2793
9835.594387.00559848.375383.53059853.356378.97329901.209322.65869929.325315.4488
9967.892318.692510004.48314.999710022.07317.873710350.73316.527910360.97317.9426
10392.38330.749410413.32330.4277 10423.8332.980710434.27340.370110444.74343.6017
10476.15342.4754 10497.1338.5788 10570.4338.4174 10624.6341.659310703.05353.2473
#Mann= 3 , 0 , 0
9536.992  0.0543       09536.992  0.0543       010703.05  0.0543       0
#XS Ineff= 2 , 0
       0                10188.99       0
Bank Sta=9536.992,10703.05
Exp/Cntr=0.3,0.1

Type RM Length L Ch R = 1 ,48870.54,967.547000,967.547000,967.547000
XS GIS Cut Line= 6
607304.160240145743027.085877601606770.907133937743070.142865881
606565.208219767743105.404380783606452.322164178743146.208628088
606308.999082893743216.954960823606014.565847337743407.319013894
#Sta/Elev= 30
9619.899448.31249639.131 440.7319709.394436.84649719.432434.00399739.507419.5072
9749.545408.18929759.583400.02159829.846361.59099849.914353.95339890.027347.1442
9900.055340.52489910.083328.26859930.139312.49149960.223301.32639970.251  301.09
 10020.4302.754210050.49315.310810060.52316.402810070.55314.547110261.75316.3801
10319.75314.310510343.49311.2109 10603.4314.049610637.08325.902310679.99325.7472
10729.19332.918210775.34329.728110834.67333.331410941.29333.442510994.82350.9912
#Mann= 3 , 0 , 0
9619.899  0.0462       09619.899  0.0462       010994.82  0.0462       0
#XS Ineff= 2 , 0
       0                10230.38       0
Bank Sta=9619.899,10994.82
Exp/Cntr=0.3,0.1

Type RM Length L Ch R = 1 ,   47903,595.730700,595.730700,595.730700
XS GIS Cut Line= 6
606342.084070601742263.240152364606253.749469359742560.911098735
606235.796751578742963.007292317606206.180387934743098.662753688
 606127.31699713743219.295125471605859.630953361743398.486072035
#Sta/Elev= 30
9640.623   491.89697.342511.49069718.782513.44349750.784476.24099782.225436.2667
9834.222 381.4479865.063330.91429875.344326.66019885.588325.34859926.145325.1979
9936.284319.34599956.529302.59639966.587297.75969986.701293.272610006.81292.6386
10036.86296.5157 10056.9305.3495 10066.9307.500310126.91304.853810186.93308.1349
10448.59306.481510545.48309.785710580.85315.959410606.96327.666310680.99325.7994
10729.45333.629210846.81329.809710903.02343.693210943.29344.593310962.04350.6223
#Mann= 3 , 0 , 0
9640.623    0.04       09640.623    0.04       010962.04    0.04       0
#XS Ineff= 2 , 0
       0                10360.07       0
Bank Sta=9640.623,10962.04
Exp/Cntr=0.3,0.1

Type RM Length L Ch R = 1 ,47307.27,169.854500,169.854500,169.854500
XS GIS Cut Line= 6
605584.678826428742494.946361938605619.474359112742635.502442876
605790.023197102 743018.17933167605827.831105697743126.780147681
605853.092436152743244.089815686605848.063913094743376.055029596
#Sta/Elev= 30
9675.077435.72329705.482425.99819746.477415.26569809.146403.28889819.648398.9284
9830.416391.86779851.981366.18079873.545345.45089884.327329.06289895.109309.9209
9905.892306.25269938.754306.82639982.962289.954410005.13288.123810016.21288.2112
 10027.3289.981110049.48297.428710224.93298.561710235.81299.234610246.56304.2466
10278.61304.372310320.87308.012910393.67309.717210403.97313.847610414.27314.8882
10465.19  316.7910505.39327.826910535.45 332.16310565.48338.527610607.19341.0723
#Mann= 3 , 0 , 0
9675.077    0.04       09675.077    0.04       010607.19    0.04       0
#XS Ineff= 2 , 0
       09923.502        10324.61       0
Bank Sta=9675.077,10607.19
Exp/Cntr=0.3,0.1

Type RM Length L Ch R = 1 ,47137.41,95.914000,95.914000,95.914000
XS GIS Cut Line= 6
605428.002298953742534.517352305605448.883829372742669.862625996
605588.464382231742980.405039912605638.431482479743119.711857023
605658.466574268743203.707205819 605671.24259883743318.069727111
#Sta/Elev= 30
9636.158347.30929669.147341.87799727.308341.33389758.337337.24439779.173327.4592
9789.808319.69589800.443313.89039821.714304.94729886.668 302.4099930.802302.2312
 9953.14297.02379975.477289.49699986.646287.5229   10009 285.96610031.36288.2396
10042.53292.330610053.58293.979510106.15295.809910162.35 299.24410183.81303.8163
10194.54303.527510205.13301.852410236.62301.493410309.11304.094810329.68306.0853
10360.31309.950610390.61316.077510410.81 323.40510440.95336.591910464.06342.0963
#Mann= 3 , 0 , 0
9636.158  0.0428       09636.158  0.0428       010464.06  0.0428       0
#XS Ineff= 2 , 0
       09904.086        10214.18       0
Bank Sta=9636.158,10464.06
Exp/Cntr=0.3,0.1

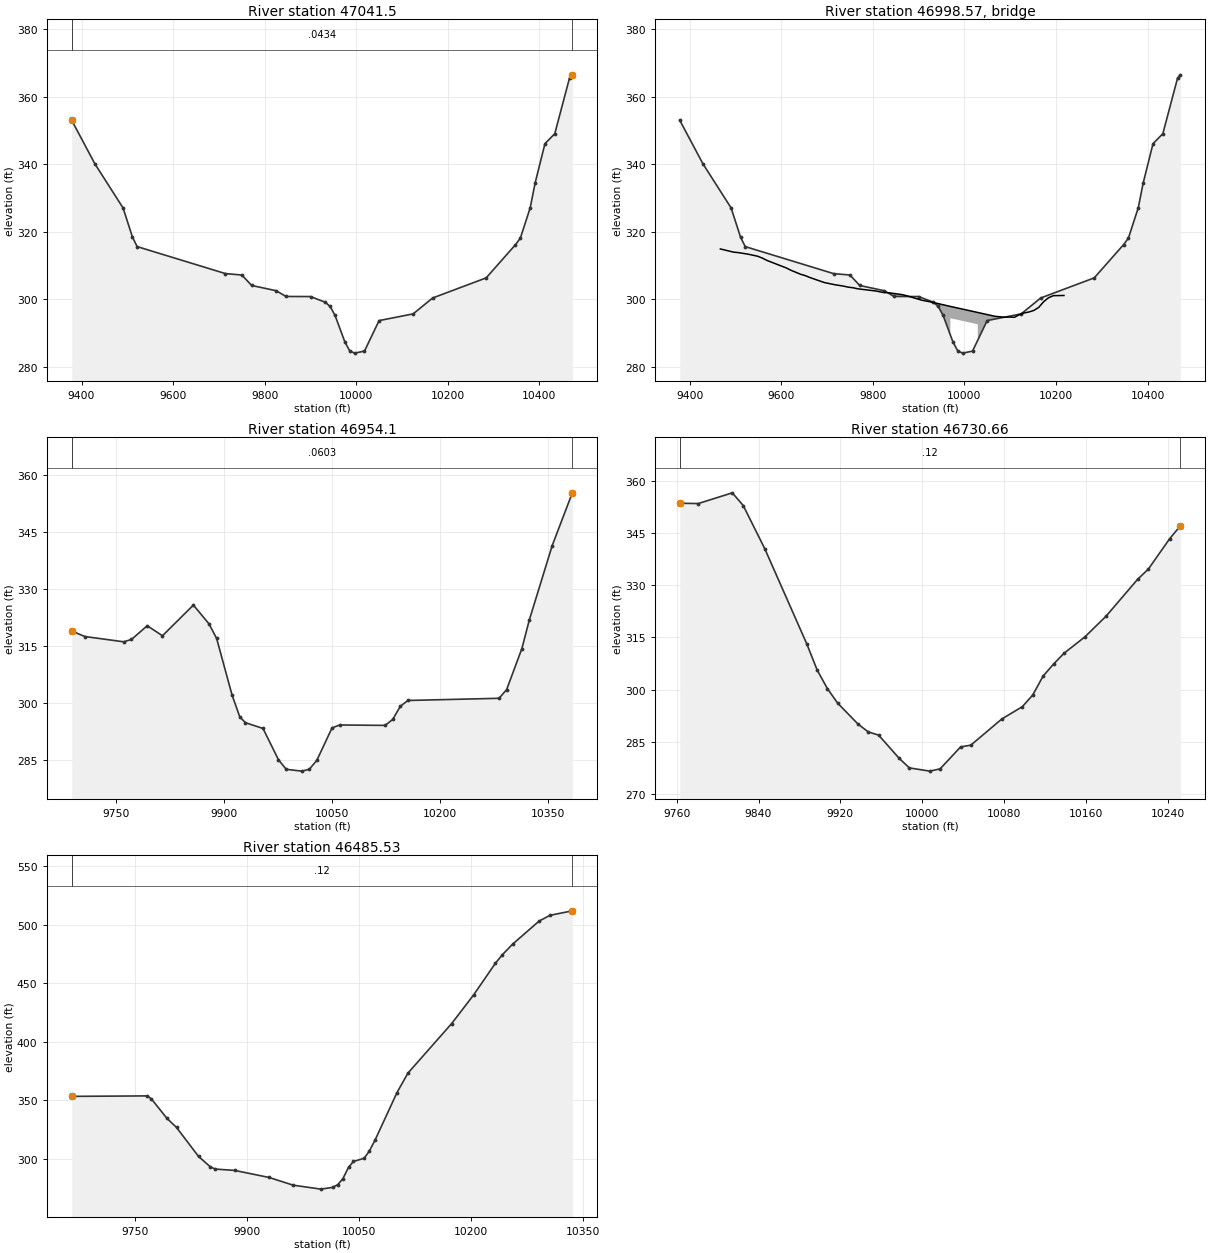
Type RM Length L Ch R = 1 , 47041.5,87.392200,87.392200,87.392200
XS GIS Cut Line= 6
 605381.33461532742325.660615236605325.802943766742566.754442945
605350.735151142742651.611429468605462.489716023742942.971545056
605563.240944684743222.966238424605616.817448467743360.720751867
#Sta/Elev= 30
9378.526353.07979429.157340.17069490.728327.08399511.252318.43519521.514315.6349
9714.376307.63279750.137307.21539771.558304.11739825.109302.5598 9846.53300.8541
9900.082300.83089932.213299.15199942.923297.90579953.634295.23269975.055287.3997
9985.765284.69319996.475284.0664 10017.9284.667410049.85293.712710124.24295.7001
10166.75300.407110283.65306.365310347.65316.195510358.38318.174610379.83327.1454
10390.56334.476810412.02346.131910433.48349.093910465.67365.588410471.81366.5433
#Mann= 3 , 0 , 0
9378.526  0.0434       09378.526  0.0434       010471.81  0.0434       0
#XS Ineff= 2 , 0
       09896.082        10179.18       0
Bank Sta=9378.526,10471.81
Exp/Cntr=0.3,0.1

Type RM Length L Ch R = 3 ,46998.57,,,
BEGIN DESCRIPTION:
END DESCRIPTION:
Bridge Culvert--1,0,-1,-1, 0
Deck Dist Width WeirC Skew NumUp NumDn MinLoCord MaxHiCord MaxSubmerge Is_Ogee
28.696100,30.000000,2.6,0, 42, 42, , , 0.95, 0, 0,0,,
 9467.21 9495.88 9507.12 9527.90 9548.68 9559.06 9569.45 9611.00 9621.39 9642.17
 9652.55 9662.94 9694.11 9717.49 9735.66 9746.30 9756.98 9767.66 9807.44 9821.05
 9835.94 9863.77 9874.45 9906.48 9927.84 9969.45 9969.4510029.4510029.4510066.66
10088.0210098.6810109.3010119.9210130.5410141.1610151.7910162.4010173.0110183.63
10194.2510217.57
  314.94  314.00  313.84  313.39  312.78  312.22  311.51  309.32  308.62  307.45
  307.04  306.46  304.99  304.33  303.94  303.62  303.44  303.12  302.47  302.09
  301.94  301.41  301.07  299.77  299.21  297.91  297.91  296.11  296.11  294.98
  294.70  294.77  294.68  295.45  295.97  296.26  296.72  297.61  299.28  300.46
  301.09  301.15
 -685.06 -686.00 -686.16 -686.61 -687.22 -687.78 -688.49 -690.68 -691.38 -692.55
 -692.96 -693.54 -695.01 -695.67 -696.06 -696.38 -696.56 -696.88 -697.53 -697.91
 -698.06 -698.59 -698.93 -700.23 -700.79 -702.09  294.41  292.61 -703.89 -705.02
 -705.30 -705.23 -705.32 -704.55 -704.03 -703.74 -703.28 -702.39 -700.72 -699.54
 -698.91 -698.85
 9467.21 9495.88 9507.12 9527.90 9548.68 9559.06 9569.45 9611.00 9621.39 9642.17
 9652.55 9662.94 9694.11 9717.49 9735.66 9746.30 9756.98 9767.66 9807.44 9821.05
 9835.94 9863.77 9874.45 9906.48 9927.84 9972.71 9972.7110032.7110032.7110066.66
10088.0210098.6810109.3010119.9210130.5410141.1610151.7910162.4010173.0110183.63
10194.2510217.57
  314.94  314.00  313.84  313.39  312.78  312.22  311.51  309.32  308.62  307.45
  307.04  306.46  304.99  304.33  303.94  303.62  303.44  303.12  302.47  302.09
  301.94  301.41  301.07  299.77  299.21  297.81  297.81  296.01  296.01  294.98
  294.70  294.77  294.68  295.45  295.97  296.26  296.72  297.61  299.28  300.46
  301.09  301.15
 -685.06 -686.00 -686.16 -686.61 -687.22 -687.78 -688.49 -690.68 -691.38 -692.55
 -692.96 -693.54 -695.01 -695.67 -696.06 -696.38 -696.56 -696.88 -697.53 -697.91
 -698.06 -698.59 -698.93 -700.23 -700.79 -702.19  294.31  292.51 -703.99 -705.02
 -705.30 -705.23 -705.32 -704.55 -704.03 -703.74 -703.28 -702.39 -700.72 -699.54
 -698.91 -698.85
BR Coef=-1 , 0 , 0 ,, 0 ,,,0.8,0,1,0,
WSPro=,,,, 1 ,,,, 0 ,,,, 0 ,,,,-1 ,-1 ,-1 , 0 , 0 , 0 , 0 , 0
BC Design=,, 0 ,, 0 ,,,,,,

Type RM Length L Ch R = 1 , 46954.1,223.447800,223.447800,223.447800
XS GIS Cut Line= 4
605255.228523701742658.209857285605288.205811352742738.088176087
605372.021734953742950.954013973605493.089180291743311.495526835
#Sta/Elev= 30
9688.654318.87499706.819317.43049760.912316.03539771.731316.65769793.616320.2639
9814.742317.62599857.731   325.79879.226320.79719889.973316.94579911.467302.0155
9922.215296.2637 9930.09294.75729954.457 293.2419975.951284.99539986.698282.4977
10008.11282.016510018.66282.488110029.21284.856810050.31293.376610060.86 294.156
10124.15294.0482 10134.7 295.63210145.25299.084310155.79300.604110282.38301.1752
10292.93 303.46610314.03314.220310324.57321.882210356.22341.343810384.17355.2247
#Mann= 3 , 0 , 0
9688.654  0.0603       09688.654  0.0603       010384.17  0.0603       0
#XS Ineff= 2 , 0
       09898.405         10165.2       0
Bank Sta=9688.654,10384.17
Exp/Cntr=0.3,0.1

Type RM Length L Ch R = 1 ,46730.66,245.127500,245.127500,245.127500
XS GIS Cut Line= 6
 605197.55424674742758.927518217605157.708888591742860.595017078
605150.865926329742921.833846168605150.603582614 743044.21756584
605141.079827089743109.555135298605108.847374209743235.092272844
#Sta/Elev= 30
    9763353.54559781.112353.45779814.386 356.5419825.094 352.876 9846.15340.4712
9887.231313.12239897.352305.63139907.416300.25319917.443 296.0999937.488290.0392
9947.489287.81239957.489286.91589977.503280.26829987.531277.492410007.57276.5684
10017.59277.219610037.62 283.52810047.63  284.0310077.87291.540710098.08295.1069
10108.18298.444610118.29303.862110128.48307.313110138.73310.431610159.24315.1597
10179.76 321.057 10210.8 331.70810221.21334.615110242.05343.344810252.56 347.059
#Mann= 3 , 0 , 0
    9763    0.12       0    9763    0.12       010252.56    0.12       0
#XS Ineff= 2 , 0
       0                               0
Bank Sta=9763,10252.56
Exp/Cntr=0.3,0.1

Type RM Length L Ch R = 1 ,46485.53,245.127400,245.127400,245.127400
XS GIS Cut Line= 6
605135.145171432742708.653114174605064.004520029742790.236797839
604933.148596078742947.394100696 604903.74572736742971.259849221
 604882.64793849742991.738143116604684.693828344743203.263503537
#Sta/Elev= 30
9665.456353.28399766.752353.68789772.186351.04599792.802334.5622 9805.74326.6976
9835.171301.90119850.931 293.0389857.493291.08899883.369289.95439929.649283.8994
9961.802277.3062    9999273.931310014.61275.425910021.56277.819510028.37282.9743
10035.91292.629810042.31297.569310056.78300.341410063.75306.572410071.42315.9692
10100.68 356.50910115.32373.157710173.86415.584410203.13439.9844 10232.4467.1957
 10241.8474.535310255.49483.554110290.94503.289210305.57508.188510335.29512.0104
#Mann= 3 , 0 , 0
9665.456    0.12       09665.456    0.12       010335.29    0.12       0
#XS Ineff= 2 , 0
       0                               0
Bank Sta=9665.456,10335.29
Exp/Cntr=0.3,0.1