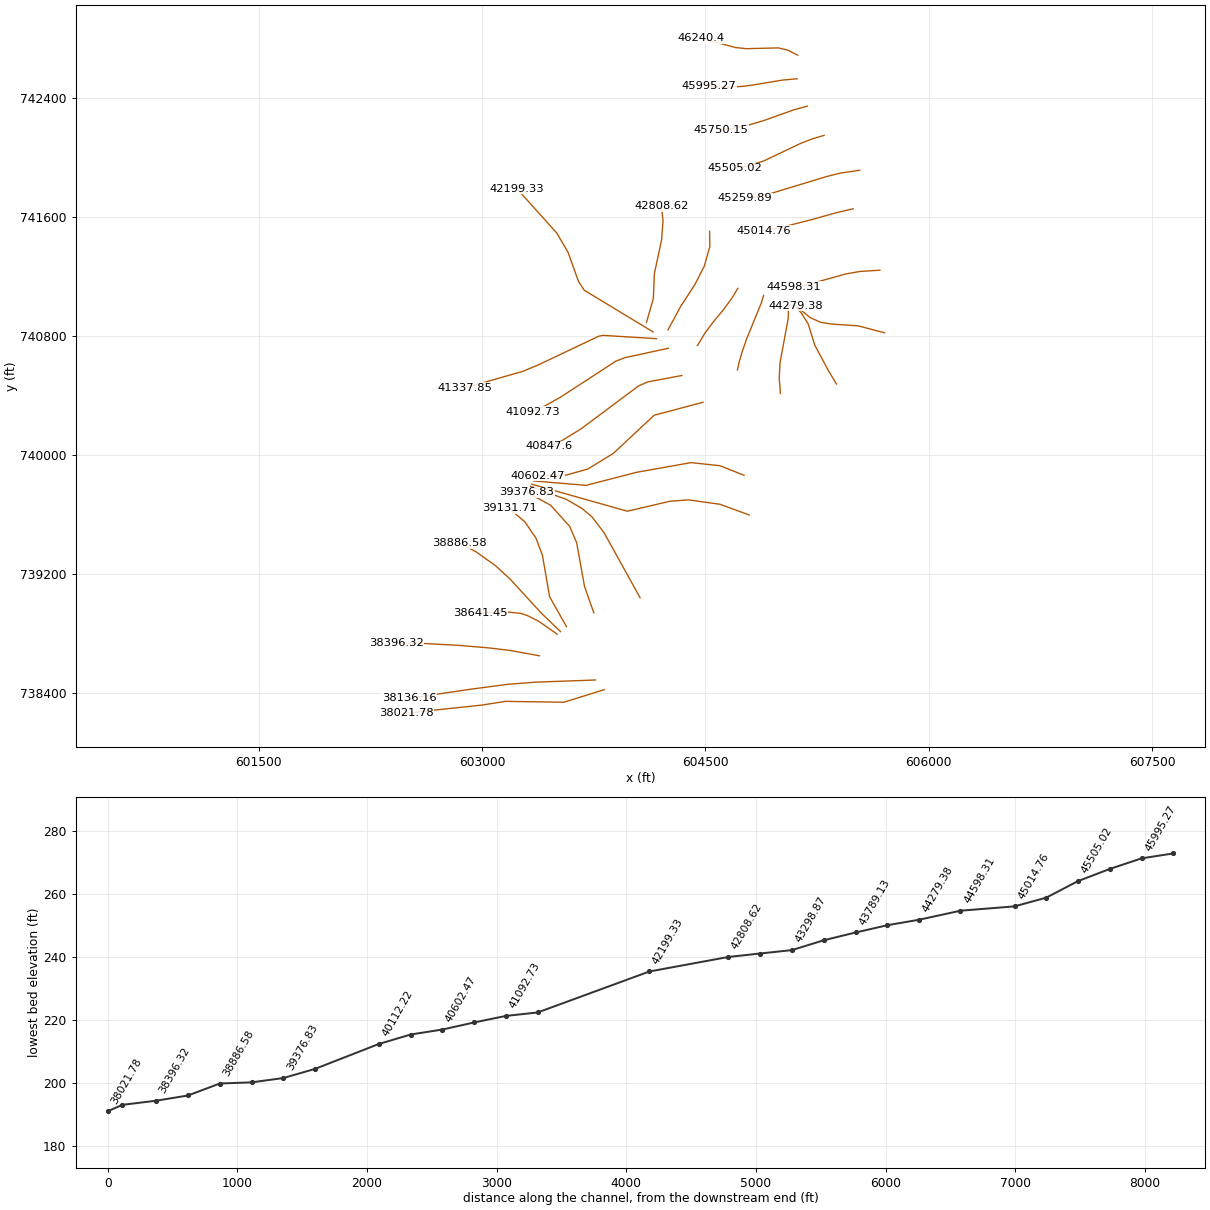
HEC-RAS study 2027_ras.prj: 2027

--- 2027_ras.g01 (geometry) --- (continued)

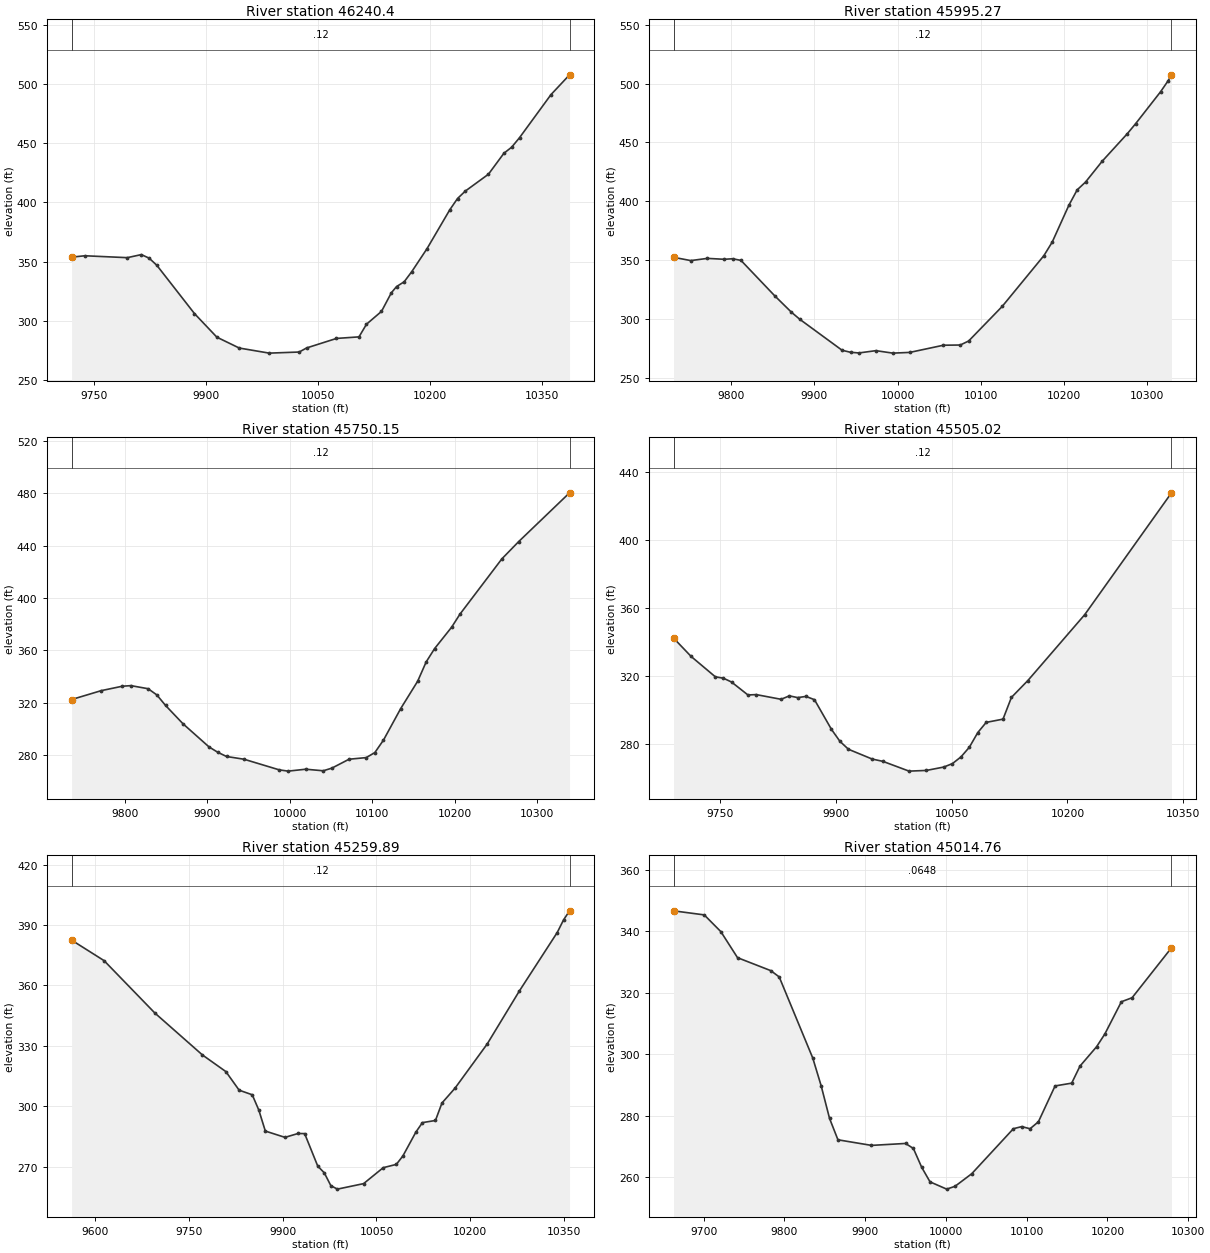
Type RM Length L Ch R = 1 , 46240.4,245.127500,245.127500,245.127500
XS GIS Cut Line= 6
605119.467238156 742685.44977293  605053.1579234742719.364490062
604990.100306958742734.352810055604774.148661345742729.126988381
604701.856971085742736.872329488604471.443791032742798.570780441
#Sta/Elev= 30
9719.544353.85439737.415355.01359794.204353.41059813.109355.9971 9823.52353.0082
9833.828346.97719884.325306.17769914.332286.26089944.362277.08619984.518272.7932
10024.68273.721410034.68277.178710074.68285.204710104.85286.521810114.91297.2125
10135.02308.046510148.24323.757310155.23329.007410165.42333.043210175.61341.6134
10195.99360.952510226.62 393.89710236.97403.373510247.33409.6187 10278.4423.8902
10299.11441.573510309.48446.695810320.04454.717710362.25491.1215 10387.1507.8167
#Mann= 3 , 0 , 0
9719.544    0.12       09719.544    0.12       0 10387.1    0.12       0
#XS Ineff= 2 , 0
       0                               0
Bank Sta=9719.544,10387.1
Exp/Cntr=0.3,0.1

Type RM Length L Ch R = 1 ,45995.27,245.127400,245.127400,245.127400
XS GIS Cut Line= 6
605115.685952315742527.182253785605017.484805435742518.249386385
604809.181410611742483.782095298604743.693440586 742475.58096911
604636.474728942742469.838470012604521.999605894742475.464304402
#Sta/Elev= 30
9731.064352.55189751.783349.76729771.815351.63569791.943350.86399802.011351.3215
 9812.08349.90979852.464319.95099872.698305.89579882.816299.86999933.402273.6922
9943.562271.94449953.722271.39949974.044  273.339994.365271.234910014.67271.8463
10055.16277.948210075.31278.118710085.39281.519310125.61310.818610175.72353.9519
10185.73365.465610205.73396.731610215.74409.832610225.74416.401210245.75434.1002
10275.77457.331810285.77465.851610315.86493.063410324.83502.290710328.94507.3985
#Mann= 3 , 0 , 0
9731.064    0.12       09731.064    0.12       010328.94    0.12       0
#XS Ineff= 2 , 0
       0                               0
Bank Sta=9731.064,10328.94
Exp/Cntr=0.3,0.1

Type RM Length L Ch R = 1 ,45750.15,245.127500,245.127500,245.127500
XS GIS Cut Line= 6
605184.617145302 742343.28836607605093.650455862742318.676339746
604897.792216212742248.378398031604803.025048196742220.015505463
 604687.96136862742194.973302692604603.530071586742185.738031313
#Sta/Elev= 30
9735.451322.49359771.439329.28289797.045332.65589807.468333.10589828.315330.7473
9838.864326.03599849.433318.01639870.571304.03179902.278286.30979912.848282.2439
9923.417 279.0529944.679276.95549987.442268.83919998.133267.881110019.48269.3336
10040.75268.148110051.19270.165410072.07276.956310092.94278.208310103.38282.0593
10113.82291.5524 10134.7315.579810155.31336.492610165.61351.1878 10175.9361.4153
10196.47377.660510206.65387.682910257.54429.891610277.72442.911810339.53480.1954
#Mann= 3 , 0 , 0
9735.451    0.12       09735.451    0.12       010339.53    0.12       0
#XS Ineff= 2 , 0
       0                               0
Bank Sta=9735.451,10339.53
Exp/Cntr=0.3,0.1

Type RM Length L Ch R = 1 ,45505.02,245.127400,245.127400,245.127400
XS GIS Cut Line= 6
605296.993189033742147.106459204605216.749078989742123.214448303
605137.152118027742092.270230934604894.370375365741976.554954782
604801.180879295741945.945847243604694.683516592741926.013146907
#Sta/Elev= 30
9689.949 342.2259712.755331.40959744.145319.43029754.608318.62239765.071316.3838
 9786.31308.78299797.039308.99769829.226306.24369839.956308.25789850.685307.2294
9861.472307.93619872.473305.99629894.475288.55269905.476 281.5159916.477276.8755
9947.142271.14049961.116 269.7689994.903264.037710017.39264.447910039.85 266.429
10051.08268.460810062.09272.373910072.99278.069310083.89286.666210094.79292.6753
10116.58294.580210127.48307.359810148.77 317.265 10222.3355.913510334.74427.5417
#Mann= 3 , 0 , 0
9689.949    0.12       09689.949    0.12       010334.74    0.12       0
#XS Ineff= 2 , 0
       0                               0
Bank Sta=9689.949,10334.74
Exp/Cntr=0.3,0.1

Type RM Length L Ch R = 1 ,45259.89,245.127400,245.127400,245.127400
XS GIS Cut Line= 6
605536.612694979741913.065258846605401.612634003741892.971865341
605309.578469008741869.443962783604933.683903575741755.083836824
604849.504232764741735.594556674604765.401102947741724.516462469
#Sta/Elev= 30
9562.717382.53929614.662372.34269695.852346.29689771.861325.46519809.317317.1957
9830.492307.96449851.429305.68079861.898298.11239872.366287.63679903.772284.5124
9924.709286.43759935.177 286.3789956.114270.23519966.583266.87299977.051260.5149
9987.519 258.78510029.37261.514210060.76 269.44810081.69 271.07910092.15 275.254
10112.99287.1548 10123.4 291.84110144.21292.902610154.62301.585510175.44308.9421
10226.92330.926410278.18357.199810338.82386.322310348.85392.544710358.49397.0966
#Mann= 3 , 0 , 0
9562.717    0.12       09562.717    0.12       010358.49    0.12       0
#XS Ineff= 2 , 0
       0                               0
Bank Sta=9562.717,10358.49
Exp/Cntr=0.3,0.1

Type RM Length L Ch R = 1 ,45014.76,416.456400,416.456400,416.456400
XS GIS Cut Line= 6
605492.286618908741654.317660834605372.958517759741626.275221868
605214.418034757741581.677139656605029.409022016741534.447462271
604966.221803691741519.517297481604893.676930807741508.225464577
#Sta/Elev= 30
9662.655346.66329700.687345.33919721.307339.87239741.926331.40189783.165327.1743
9793.537325.1322 9835.09298.70969845.478289.67969855.866279.04649866.254272.0898
9907.807270.26749949.964270.89819959.678 269.2649969.992263.12049980.307 258.383
10000.93256.022110011.26256.9433 10031.9261.028110083.52275.701710093.84276.3837
10104.17275.688910114.49277.954510135.13289.632210155.71290.539610165.99296.0987
10186.54302.398210196.81306.573310217.25317.053610230.53318.3615 10279.3334.6281
#Mann= 3 , 0 , 0
9662.655  0.0648       09662.655  0.0648       0 10279.3  0.0648       0
#XS Ineff= 2 , 0
       0                               0
Bank Sta=9662.655,10279.3
Exp/Cntr=0.3,0.1

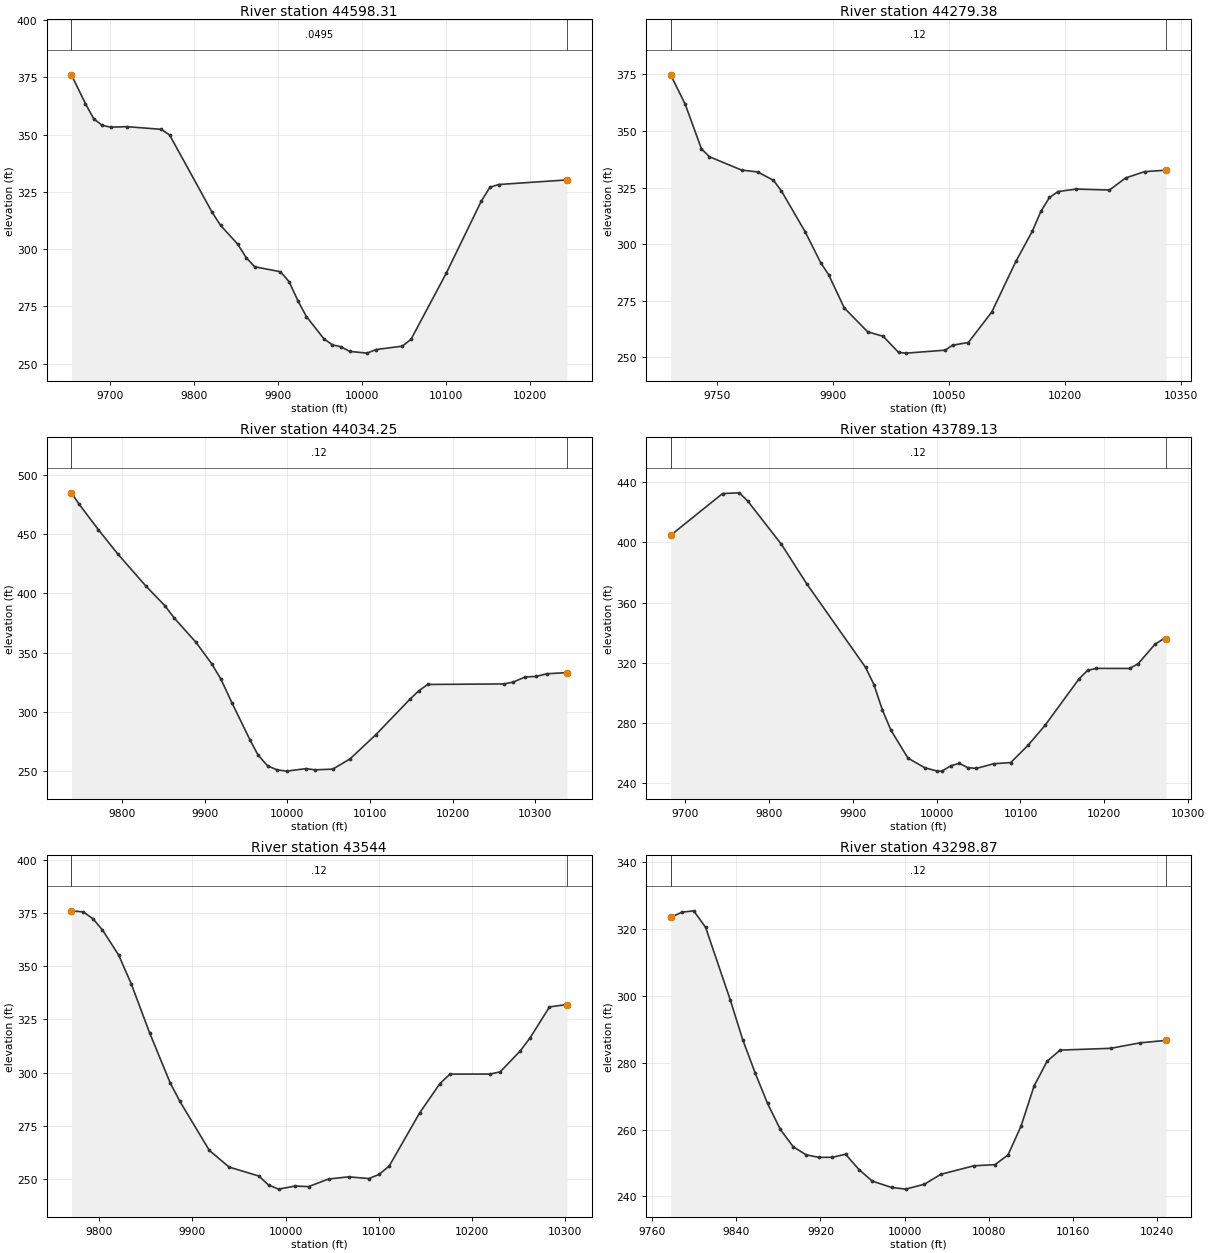
Type RM Length L Ch R = 1 ,44598.31,318.925900,318.925900,318.925900
XS GIS Cut Line= 6
605671.583238882741241.883422418605539.027757679 741233.45080849
605446.328292135741217.810420821605184.479905907741144.597822527
605134.619215314741134.286650131605094.564831172741131.987618829
#Sta/Elev= 30
9654.075376.06719670.659363.5574 9680.66356.83889690.674354.03749700.689353.2388
9720.718353.44599760.894352.28699770.944349.82799821.505316.14379831.647310.3952
9851.929302.24359862.071 296.3659872.212292.32259902.991290.16469913.299285.7782
9923.607277.56979933.915270.57769954.531 260.9819964.839258.23999975.147257.3968
9985.455255.402310006.22 254.65110016.66256.207610047.99257.694310058.44260.7113
10100.21289.425910141.99320.902310152.43327.027210162.66 328.20710244.01330.2213
#Mann= 3 , 0 , 0
9654.075  0.0495       09654.075  0.0495       010244.01  0.0495       0
#XS Ineff= 2 , 0
       0                               0
Bank Sta=9654.075,10244.01
Exp/Cntr=0.3,0.1

Type RM Length L Ch R = 1 ,44279.38,245.127500,245.127500,245.127500
XS GIS Cut Line= 6
605702.980202058740821.766540637605524.504564047740868.408941418
605345.001418352740880.421436921605272.897369087740892.288265869
605202.414101064740924.313915864605105.747074217741003.349052578
#Sta/Elev= 30
9690.108374.83329708.944361.82919729.896342.17079740.356338.60139781.772332.7436
9802.481331.90489823.048328.22729833.276323.5422 9863.96305.5105  9884.3291.6766
9894.407 286.4999914.619271.78059944.856261.2346  9964.9259.2488 9984.93252.0962
9994.931251.798210044.93253.102210054.93255.332610075.05256.491110105.42  269.99
 10136.5292.320910157.81305.720110168.88314.446510179.94320.612310191.19323.2397
10214.86 324.32910257.56323.894210278.52329.2601   10303332.037710330.78332.6751
#Mann= 3 , 0 , 0
9690.108    0.12       09690.108    0.12       010330.78    0.12       0
#XS Ineff= 2 , 0
       0                               0
Bank Sta=9690.108,10330.78
Exp/Cntr=0.3,0.1

Type RM Length L Ch R = 1 ,44034.25,245.127400,245.127400,245.127400
XS GIS Cut Line= 6
605379.958314292740477.554130094605325.857688725 740567.56464304
605234.274977177 740738.82326515 605190.09348011740881.277519539
605143.998276889740954.142706126605101.323028743 741002.89965339
#Sta/Elev= 30
9738.481484.60889747.318475.48579771.053453.58179794.442433.20429829.038405.7337
9851.885389.26719863.124378.94239889.213358.64449908.083340.74619919.323327.8111
9933.021307.30489954.924276.01689964.387263.69929975.981 254.4659987.575251.1161
    9999250.054310022.42252.151810033.57251.150410054.93251.745410075.85260.4225
10106.85280.656910148.42310.790110159.09317.806710169.77 323.098 10262.3323.5583
10273.53325.138210287.88329.4455 10301.1329.839310314.32  332.1310338.34333.0894
#Mann= 3 , 0 , 0
9738.481    0.12       09738.481    0.12       010338.34    0.12       0
#XS Ineff= 2 , 0
       0                               0
Bank Sta=9738.481,10338.34
Exp/Cntr=0.3,0.1

Type RM Length L Ch R = 1 ,43789.13,245.127500,245.127500,245.127500
XS GIS Cut Line= 6
605003.848303109740413.458525464604995.581725508 740515.19379811
605000.991030157740621.144486383605054.910282135740911.995758221
605057.747337818740950.983117878605053.556049377740998.047433406
#Sta/Elev= 30
9682.987 404.7549744.881 432.5579764.908433.03419774.921427.55939814.939398.8476
9844.978372.66679915.348  316.849925.443305.21549935.539288.28449945.634274.9878
9965.875256.4223 9986.21249.9375   10001247.751410006.58247.812710016.81251.2649
10027.04252.958310037.27250.0507 10047.5249.550710067.95252.659410088.41253.4604
10108.87264.847110129.32278.233510169.98309.281910180.11314.832710190.22 316.146
10230.32316.119510240.32319.275610260.44 332.27610270.54335.766310273.62335.4354
#Mann= 3 , 0 , 0
9682.987    0.12       09682.987    0.12       010273.62    0.12       0
#XS Ineff= 2 , 0
       0                               0
Bank Sta=9682.987,10273.62
Exp/Cntr=0.3,0.1

Type RM Length L Ch R = 1 ,   43544,245.127400,245.127400,245.127400
XS GIS Cut Line= 6
604715.269034088740572.421682149604725.680927873740622.045038313
604747.070741266 740694.87492919604777.694995284740782.857759133
604875.502277017741022.285706267604890.907939189741072.896058397
#Sta/Elev= 30
 9770.41376.00049783.262375.4734 9793.48372.27029803.698366.99979821.114355.1746
9834.616341.64389854.185318.76469876.306295.19689886.728286.46639918.329263.4731
9939.506 255.6449971.272251.4729 9981.86247.20099992.471245.289910010.51246.7504
10024.65246.475510046.12250.033110067.68251.067110089.43250.2496 10100.3252.1993
10111.17256.132710143.79 281.07410165.53294.855610176.41299.304110219.52 299.344
10230.27300.401310251.68310.193810262.14316.248910283.06330.866410301.75331.9969
#Mann= 3 , 0 , 0
 9770.41    0.12       0 9770.41    0.12       010301.75    0.12       0
#XS Ineff= 2 , 0
       0                               0
Bank Sta=9770.41,10301.75
Exp/Cntr=0.3,0.1

Type RM Length L Ch R = 1 ,43298.87,245.127400,245.127400,245.127400
XS GIS Cut Line= 6
604447.089420319740735.589578718604494.956897259740816.884154394
604552.737348288740894.431345552604623.944277704 740980.12282975
604677.228331476741053.016386718604717.844864905741120.235509247
#Sta/Elev= 30
9777.421  323.549788.067325.10499799.381325.51569810.694320.57019834.201 298.802
9845.999 286.9349857.798277.00149869.597267.8587 9881.77260.0541 9894.03 254.878
 9906.29252.4583 9918.55251.69229931.192251.71429943.886252.6286 9956.58248.0456
9969.294244.57919987.643 242.679   10001242.180610018.89243.649410034.38246.6109
10065.94249.166310086.01249.5154 10098.4252.410310110.78261.037610123.17273.0311
10135.56280.482210147.94283.812610195.95284.340810223.96285.9837 10248.8 286.724
#Mann= 3 , 0 , 0
9777.421    0.12       09777.421    0.12       0 10248.8    0.12       0
#XS Ineff= 2 , 0
       0                               0
Bank Sta=9777.421,10248.8
Exp/Cntr=0.3,0.1

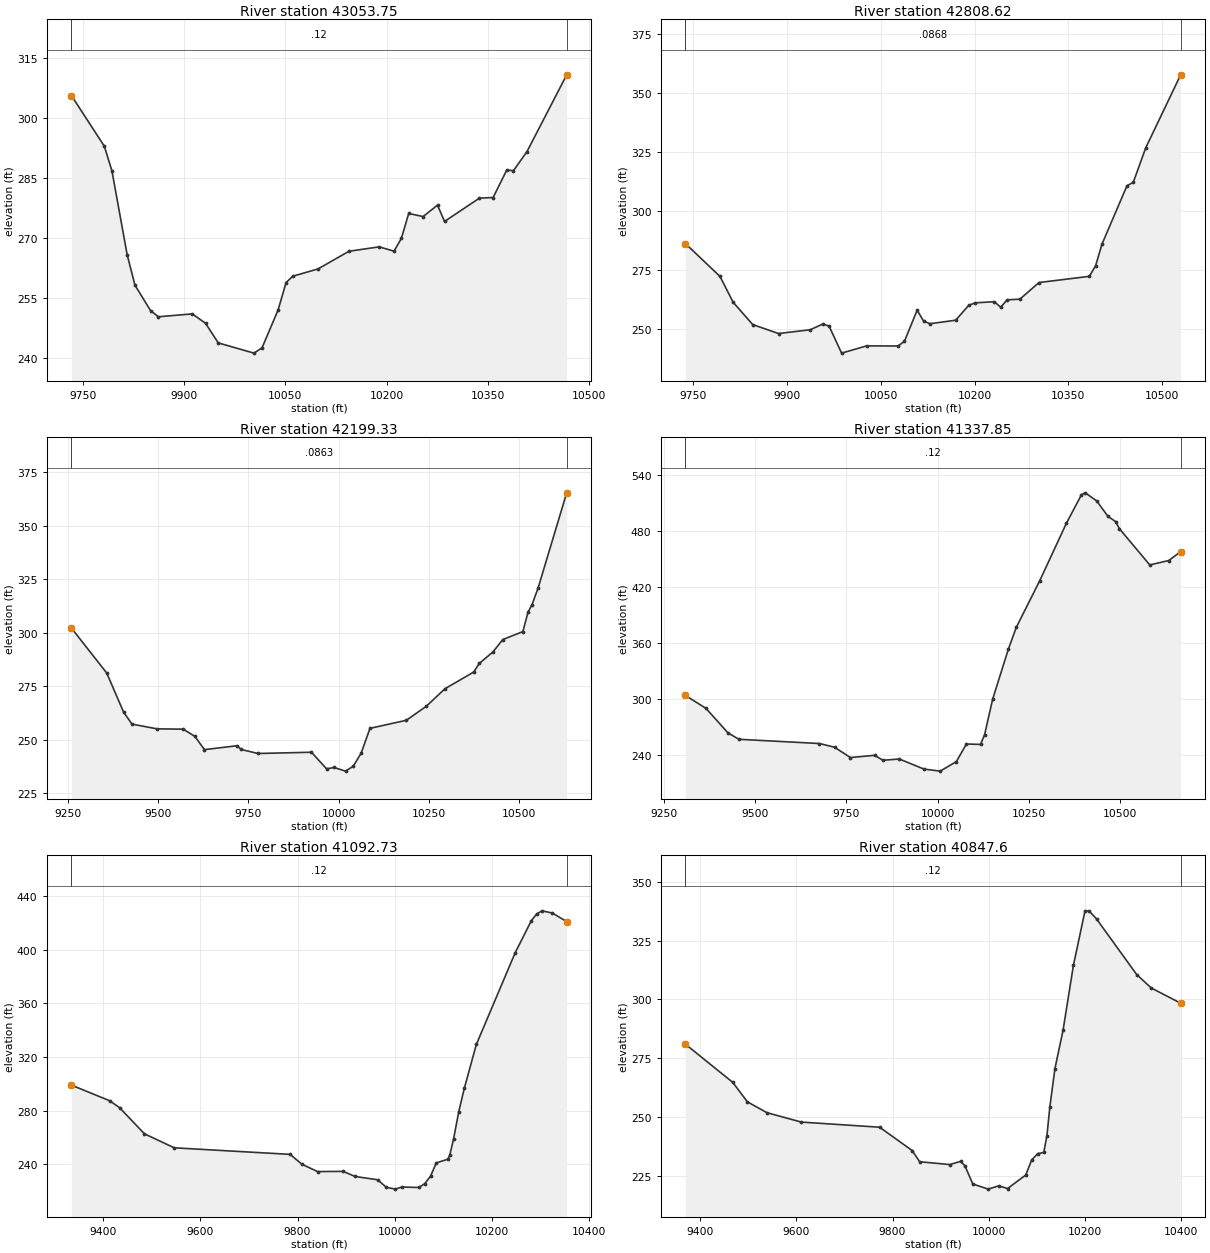
Type RM Length L Ch R = 1 ,43053.75,245.127500,245.127500,245.127500
XS GIS Cut Line= 6
 604248.77536723740841.236289605604333.931102246740998.495308936
604429.459812313741145.921683937604492.493627608741268.975171342
604529.788685769741400.917361096604528.091473585741503.430695388
#Sta/Elev= 30
9733.202305.57719781.941292.89049793.163286.73989815.689265.7822 9827.24258.1162
9850.343251.76439861.894250.20189912.136250.9232 9931.86248.56679950.615243.6569
10003.58241.099810015.46242.436510039.21 251.89310051.09 258.778   10061260.3545
10098.25262.168210144.17266.599710188.97267.707310210.87  266.6210221.82269.8351
10232.61276.067410253.97275.287410275.27278.154410285.64274.063610337.33 279.899
10357.63280.057910377.77286.9202 10387.8286.794710407.85291.574610466.56310.7714
#Mann= 3 , 0 , 0
9733.202    0.12       09733.202    0.12       010466.56    0.12       0
#XS Ineff= 2 , 0
       0                               0
Bank Sta=9733.202,10466.56
Exp/Cntr=0.3,0.1

Type RM Length L Ch R = 1 ,42808.62,609.291000,609.291000,609.291000
XS GIS Cut Line= 6
604104.806683391740892.383058861604150.393449455741051.139681622
604157.571337879741219.965045914604205.611682594741444.102999732
604215.457973629741573.154795408604205.017132911741670.047650949
#Sta/Elev= 30
9738.197286.31549793.456272.4297 9814.46261.51029845.754252.05769886.998 248.291
9937.575  249.889957.683252.31279967.684 251.4339987.686240.0063 10027.7243.0689
10077.88243.023610088.03 244.99910108.34258.145510118.53253.604110128.81252.4283
10169.94253.9312 10190.5260.142810200.78261.248710231.62261.752810241.83259.3981
10252.02262.5347 10272.4 262.82110302.97269.841710383.44272.468210393.44 276.978
10403.45286.013310443.49310.7654 10453.5312.175810473.53326.834710529.21357.6385
#Mann= 3 , 0 , 0
9738.197  0.0868       09738.197  0.0868       010529.21  0.0868       0
#XS Ineff= 2 , 0
       0                               0
Bank Sta=9738.197,10529.21
Exp/Cntr=0.3,0.1

Type RM Length L Ch R = 1 ,42199.33,861.473600,861.473600,861.473600
XS GIS Cut Line= 6
604149.011208296740827.170330659603686.403022325741107.443498694
603648.019972293741166.406344456603577.240077537741363.072641092
603501.880885284741491.614424402603235.135678748741788.549256491
#Sta/Elev= 30
9260.197302.17859357.892281.19469404.408263.00719427.665257.35759497.438255.1278
9569.416254.99919602.098251.59739628.192245.43659718.387247.24259730.016245.5044
9776.531243.63459924.541244.21699966.284236.48269987.156237.101810018.73235.4039
10040.01237.677710061.82243.728710086.41  255.3810186.91259.1225 10242.4265.6883
10293.66273.838910373.33281.640410388.77285.654210426.82291.067310454.02296.8235
10509.52300.527910523.68309.543510534.85  313.1110552.01321.059810630.75365.3007
#Mann= 3 , 0 , 0
9260.197  0.0863       09260.197  0.0863       010630.75  0.0863       0
#XS Ineff= 2 , 0
       0                               0
Bank Sta=9260.197,10630.75
Exp/Cntr=0.3,0.1

Type RM Length L Ch R = 1 ,41337.85,245.127400,245.127400,245.127400
XS GIS Cut Line= 6
  604171.4992688 740782.19420965603812.204883307740804.267638817
603782.828862995740798.227177575603375.357146263740604.702114969
603269.568860739  740561.2202622602883.611613631740451.655415669
#Sta/Elev= 30
9309.164303.6114 9365.77289.65069425.883263.42129455.939256.55299676.491252.0366
9717.879248.05019761.272236.95969827.819239.39489850.322234.05939895.327 235.448
9962.835224.616410007.42222.430910051.59232.653510079.11251.512310117.84251.0815
10128.88261.397810150.96299.4646 10194.2353.340910215.83376.597210280.09426.5921
10352.86488.001210394.44518.805810404.83520.814910436.02512.1667 10467.2495.4778
10487.99489.979910498.39482.318210581.55443.501710633.52448.239210666.15457.7501
#Mann= 3 , 0 , 0
9309.164    0.12       09309.164    0.12       010666.15    0.12       0
#XS Ineff= 2 , 0
       0                               0
Bank Sta=9309.164,10666.15
Exp/Cntr=0.3,0.1

Type RM Length L Ch R = 1 ,41092.73,245.127500,245.127500,245.127500
XS GIS Cut Line= 6
604251.813770562740717.942608222 603957.08230871740653.992067277
603898.553313017740630.959185407603526.377913743740388.890368149
603427.653912961740333.615733355603339.003161639740292.748349339
#Sta/Elev= 30
9334.567298.95219413.169287.29979433.634 282.1319484.797262.62649546.194252.1653
9784.746247.27149809.035239.8918 9841.51234.40899894.048234.58789918.337230.7802
 9964.87 228.3199983.014222.647310001.51221.334710014.53222.884710050.09222.5839
10061.94225.4507 10073.8231.005210085.65240.902210109.36243.651510113.27246.5675
10121.21258.7427 10131.9 279.10910143.28296.479610168.04329.263210248.11397.7675
10281.39421.7019 10292.4426.702210303.41429.0044 10324.8427.330110354.06420.9766
#Mann= 3 , 0 , 0
9334.567    0.12       09334.567    0.12       010354.06    0.12       0
#XS Ineff= 2 , 0
       0                               0
Bank Sta=9334.567,10354.06
Exp/Cntr=0.3,0.1

Type RM Length L Ch R = 1 , 40847.6,245.127400,245.127400,245.127400
XS GIS Cut Line= 6
604341.766012579740534.825544178604115.042744845740492.333967134
 604051.39972651740465.209170356  603666.0224033740177.101722494
603526.401694477740091.634786308603448.664216369740058.520853817
#Sta/Elev= 30
9369.201 280.9459467.652264.69779498.174256.40979538.871251.78139610.573247.7888
9773.125245.6105  9840.8235.68159856.455230.91599919.077229.71269941.375231.0731
9950.388229.25549967.008221.4428    9999219.262910020.43220.646410039.39219.5283
10076.98225.246710089.51231.708310102.04234.364110114.57234.864810121.18242.0601
 10127.1254.093210137.78270.557910154.67286.860910176.17314.437310200.22337.5845
10208.67337.692910224.27334.254710307.76310.594210338.16304.852710399.26298.3944
#Mann= 3 , 0 , 0
9369.201    0.12       09369.201    0.12       010399.26    0.12       0
#XS Ineff= 2 , 0
       0                               0
Bank Sta=9369.201,10399.26
Exp/Cntr=0.3,0.1

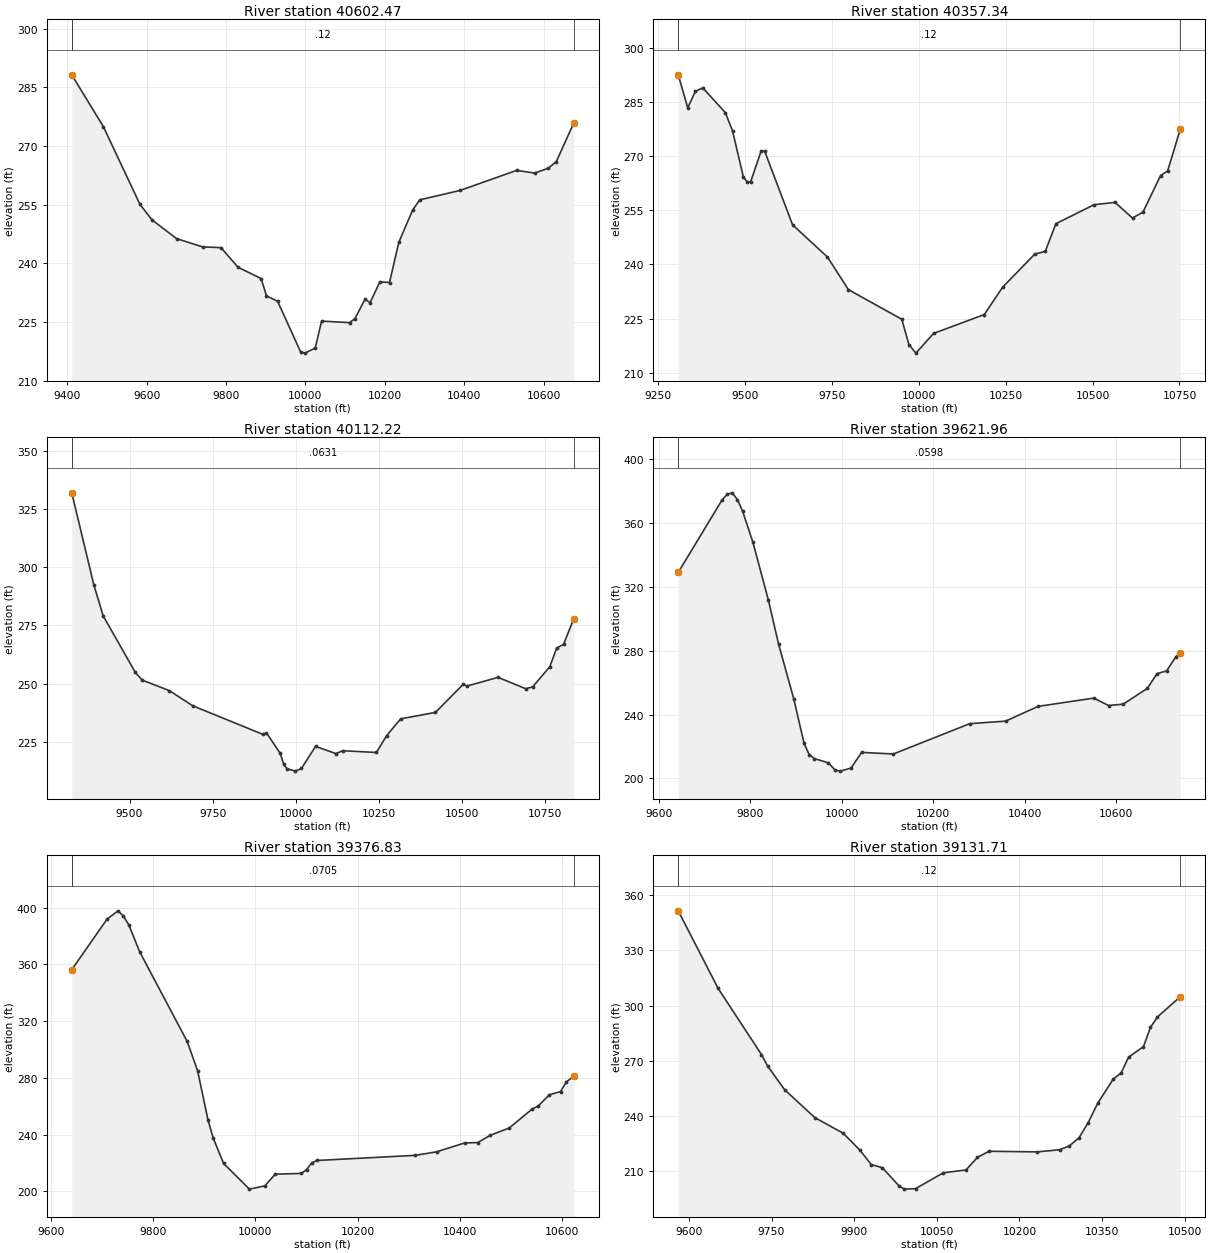
Type RM Length L Ch R = 1 ,40602.47,245.127500,245.127500,245.127500
XS GIS Cut Line= 6
604483.119535714 740354.92106019604155.854521185 740268.04341203
 603882.40675804740012.332883045 603710.24084729739906.699278638
 603563.52893278 739866.06661588603370.939347625739861.419694111
#Sta/Elev= 30
9411.098288.23579490.847274.95419582.725255.1292 9613.35251.10749675.312246.3117
9740.858244.2079 9787.31244.01329830.055238.99429888.292236.11069901.814231.6771
9929.927230.27449987.899217.3172    9999217.021810024.72218.330110040.74225.2212
10111.31224.824610124.68225.858110150.27230.832510162.97229.935910187.67235.2729
10211.86235.0876 10235.4245.402910269.85253.547310287.96256.247210389.56258.6425
10532.27263.783910577.39263.093710612.32264.327810632.33266.056510676.44 275.954
#Mann= 3 , 0 , 0
9411.098    0.12       09411.098    0.12       010676.44    0.12       0
#XS Ineff= 2 , 0
       0                               0
Bank Sta=9411.098,10676.44
Exp/Cntr=0.3,0.1

Type RM Length L Ch R = 1 ,40357.34,245.127400,245.127400,245.127400
XS GIS Cut Line= 6
 604759.62746641739865.017444581604597.975927204739929.202567756
604403.591301471 739950.01588656604037.228614122739884.856810942
603699.018636167739797.280418471603349.059631964739826.849743454
#Sta/Elev= 30
9307.057292.47169334.461283.35399356.515287.9102 9377.57288.88219442.532282.0289
 9463.47276.91319494.609264.14179504.872262.94199515.135262.7458 9545.68271.3833
9555.801271.34879636.135250.95959736.375 242.057 9797.11232.99919950.626224.8167
9970.935 217.8239991.244 215.43910042.11220.896810188.21226.122710240.72233.6756
10333.48242.853410363.76243.605910394.05251.2608 10504.2256.526710564.36257.1659
10614.74252.819310645.02254.512610695.55264.596410715.85265.875410752.34277.4379
#Mann= 3 , 0 , 0
9307.057    0.12       09307.057    0.12       010752.34    0.12       0
#XS Ineff= 2 , 0
       0                               0
Bank Sta=9307.057,10752.34
Exp/Cntr=0.3,0.1

Type RM Length L Ch R = 1 ,40112.22,490.254900,490.254900,490.254900
XS GIS Cut Line= 6
604793.909826189739598.669880167604597.834998637739670.291709766
604388.051458806739699.815005407604264.072622269739691.236073524
603975.978126585 739623.72184132603334.991095376739804.621455642
#Sta/Elev= 30
9326.175331.98269392.535292.45499420.585279.15969517.193254.87899538.062251.5426
9619.858247.00599690.418240.48319901.585228.20669911.809228.92899953.276  220.08
9963.755215.39949973.838213.4623    9999212.443110017.09213.583110059.64223.0664
10121.07219.967310141.15221.2177 10242.7 220.44910273.65 227.72310315.58234.8984
 10420.4237.666610504.25249.798410514.73248.9672 10608.8252.7143 10691.9247.8421
10712.67248.6259 10764.4257.293710785.05265.315810805.69266.878110836.66277.9677
#Mann= 3 , 0 , 0
9326.175  0.0631       09326.175  0.0631       010836.66  0.0631       0
#XS Ineff= 2 , 0
       0                               0
Bank Sta=9326.175,10836.66
Exp/Cntr=0.3,0.1

Type RM Length L Ch R = 1 ,39621.96,245.127400,245.127400,245.127400
XS GIS Cut Line= 6
604061.227939308739043.480545253603819.563678175739479.371020749
 603739.53073281739584.851643592603670.523024291739642.845080316
603566.695138961739702.998886064603326.064828481739790.517953946
#Sta/Elev= 30
9642.195329.12979737.757374.4364 9749.09378.12439760.424379.02919771.758374.7087
9783.091367.43929805.615347.94339839.135312.05729861.482284.40459895.002249.7168
9917.349222.05629928.522214.98979939.696212.44169970.727209.77579985.489205.1545
9997.021204.576910020.17206.506510043.31216.327610112.71 215.32210279.68234.3279
10358.22235.925610429.33245.167210551.18250.351310583.29245.714310615.39246.5469
10668.32256.476810689.33265.694910710.16  267.3710730.98  276.4210740.29278.8133
#Mann= 3 , 0 , 0
9642.195  0.0598       09642.195  0.0598       010740.29  0.0598       0
#XS Ineff= 2 , 0
       0                               0
Bank Sta=9642.195,10740.29
Exp/Cntr=0.3,0.1

Type RM Length L Ch R = 1 ,39376.83,245.127400,245.127400,245.127400
XS GIS Cut Line= 6
603750.936034948738941.399864882603688.256591707739119.254714444
 603635.64577651739412.388126254603588.099376768 739523.00307408
603460.788988471 739663.94539769603301.265147246739751.334457589
#Sta/Elev= 30
9641.122356.32419710.225392.01819731.638397.78899742.169394.0013  9752.7387.8027
9773.761368.95719866.639305.76749887.096 285.0619907.413250.27539917.571237.5971
9937.807219.79629988.216201.669110018.48203.964510038.67212.220410089.69212.7246
10099.97215.365110110.26220.271910120.54 221.86210312.21225.461610354.03227.9562
10408.94234.194110434.59 234.48610459.13239.629410496.25244.790610540.97258.1606
10552.15260.069110574.51268.170610596.47270.421110607.37277.119510622.33281.2808
#Mann= 3 , 0 , 0
9641.122  0.0705       09641.122  0.0705       010622.33  0.0705       0
#XS Ineff= 2 , 0
       0                               0
Bank Sta=9641.122,10622.33
Exp/Cntr=0.3,0.1

Type RM Length L Ch R = 1 ,39131.71,245.127500,245.127500,245.127500
XS GIS Cut Line= 6
603567.554435134 738848.88259992603453.921715438 739049.89189297
603405.741987139 739328.30131042603362.092339098739444.071084097
603287.787364542739552.365312636603181.339949983739643.298376143
#Sta/Elev= 30
9580.653351.53469652.882309.46159731.674273.45699742.683267.27979773.739254.3164
9828.547239.17219880.065230.66729910.573221.43119930.912213.66539951.044211.9516
9981.191202.1029 9991.24 200.29910011.35200.565510061.89209.176110102.92210.7127
10123.78 217.57710144.81 220.87610232.45220.540810273.37221.699910290.71223.8444
10308.05228.204710324.83236.504110341.91246.914210370.01260.023410384.46 263.455
10398.08272.045710425.01277.699310437.75288.2092 10450.5293.880810491.92304.8989
#Mann= 3 , 0 , 0
9580.653    0.12       09580.653    0.12       010491.92    0.12       0
#XS Ineff= 2 , 0
       0                               0
Bank Sta=9580.653,10491.92
Exp/Cntr=0.3,0.1

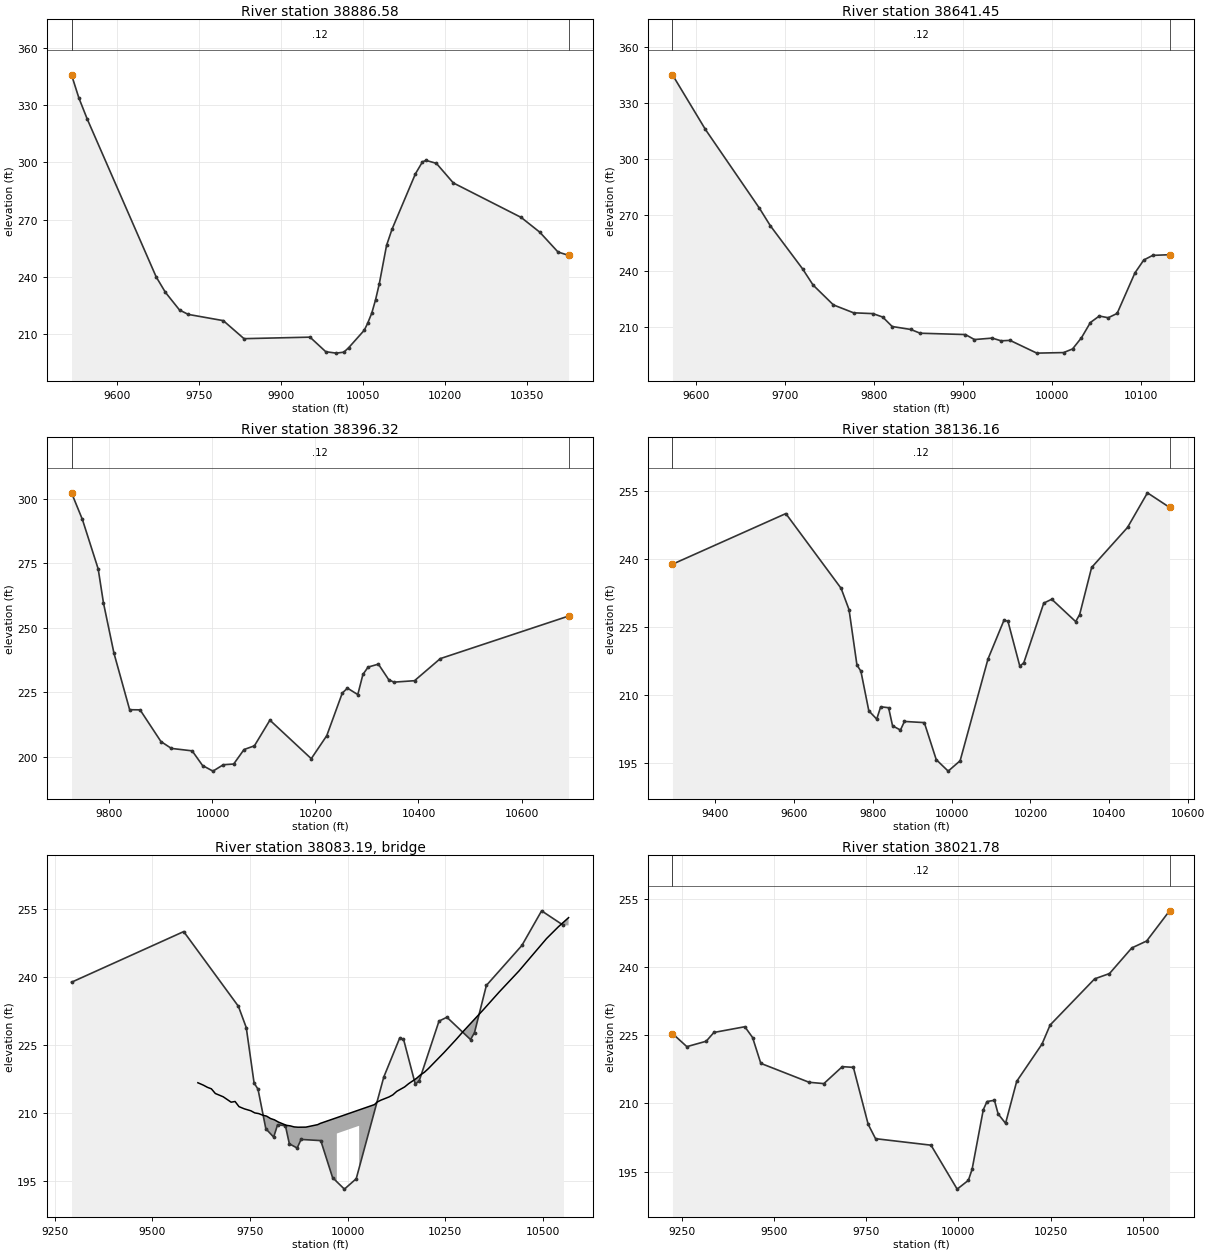
Type RM Length L Ch R = 1 ,38886.58,245.127400,245.127400,245.127400
XS GIS Cut Line= 6
603526.822505265738815.983733505603395.299639672738942.540269896
603191.597393602739165.261463568603093.452272654739256.079342216
602959.000301749739351.930964217602847.653202883739410.264829821
#Sta/Elev= 30
9516.557345.96559530.012333.83699544.935323.01099671.505 239.8939688.345231.8266
9714.102  222.579730.016220.2601 9794.17216.98689832.091207.52529952.783208.3263
9981.638200.678510000.64199.938810014.71200.439910023.59202.797610052.04211.9565
10058.13  215.5210065.78 220.945 10072.7227.916310079.52236.296710092.83256.4803
10102.77264.917310145.62294.020410158.46300.277810164.91301.060810183.87299.5426
10214.91289.250710339.05271.146210373.05263.416610406.46252.993710425.79251.2475
#Mann= 3 , 0 , 0
9516.557    0.12       09516.557    0.12       010425.79    0.12       0
#XS Ineff= 2 , 0
       0                               0
Bank Sta=9516.557,10425.79
Exp/Cntr=0.3,0.1

Type RM Length L Ch R = 1 ,38641.45,245.127500,245.127500,245.127500
XS GIS Cut Line= 6
603504.758920342738798.163145676603379.554475844738885.754925579
603302.382114917738924.424963549603258.229084045738938.295036957
603168.086611509  738947.2414601602986.101683374738939.852502535
#Sta/Elev= 30
9573.618345.19349610.592315.98329671.436273.70949683.705264.31479719.886241.2782
9731.656232.62269754.505221.97569777.198217.74019799.063217.30339809.995215.4542
9820.594210.40499841.558208.8123 9852.04206.80729902.994 206.0929913.036203.4189
9933.065204.19069943.065 202.7399953.077202.9826 9983.19196.144810013.33196.4438
10023.38198.384310033.42204.403210043.43212.540510053.45216.023110063.46215.0948
10073.47217.398310093.48239.101110103.48246.040610113.49248.4929 10132.4248.8564
#Mann= 3 , 0 , 0
9573.618    0.12       09573.618    0.12       0 10132.4    0.12       0
#XS Ineff= 2 , 0
       0                               0
Bank Sta=9573.618,10132.4
Exp/Cntr=0.3,0.1

Type RM Length L Ch R = 1 ,38396.32,260.160900,260.160900,260.160900
XS GIS Cut Line= 6
603385.697345487738653.124297539603188.147724814738689.010681464
603050.591274578 738705.58394026602842.899664215738723.277535994
602619.336952909738735.243447957602426.096209871738739.590047022
#Sta/Elev= 30
9726.375 302.3939747.514292.05319778.155 272.8839788.369259.73119808.796240.2052
 9839.22218.30229859.481218.24449900.003205.95599920.264203.29939960.627202.3504
9980.793196.667410000.96194.491810021.08196.9733 10041.2197.244810061.33202.8717
10081.41204.294410111.52214.251910191.81199.320710221.92 208.24610252.03224.7462
10262.06226.676710282.12224.166110292.13231.993310302.15234.832910322.17235.9778
 10342.2229.944810352.22228.993410392.27229.550710442.35238.118710691.38254.6123
#Mann= 3 , 0 , 0
9726.375    0.12       09726.375    0.12       010691.38    0.12       0
#XS Ineff= 2 , 0
       0                10116.48       0
Bank Sta=9726.375,10691.38
Exp/Cntr=0.3,0.1

Type RM Length L Ch R = 1 ,38136.16,114.382500,114.382500,114.382500
XS GIS Cut Line= 5
603762.150992244 738490.63163957603359.284183174738475.981937423
603170.303025454738461.332235277602916.863178194738427.637920335
 602509.60145843738367.574141532
#Sta/Elev= 30
9292.625238.88559579.966250.06879720.116233.55829740.176228.86139760.236216.6196
9770.266215.26319790.326206.51099810.386204.67219820.416207.39589840.476 207.192
9850.506203.19459870.566202.25659880.596 204.1599931.008203.90249961.272195.7222
9991.536193.1853 10021.8195.477510092.42 217.94610132.77226.473410142.86226.3392
10173.18216.345810183.29 217.13610233.83230.294710254.05231.1525 10314.7 226.211
10324.81227.771910355.13238.1697 10446.1247.003310496.65254.653810552.64251.4404
#Mann= 3 , 0 , 0
9292.625    0.12       09292.625    0.12       010552.64    0.12       0
#XS Ineff= 2 , 0
       0  9769.1        10082.47       0
Bank Sta=9292.625,10552.64
Exp/Cntr=0.3,0.1

Type RM Length L Ch R = 3 ,38083.19,,,
BEGIN DESCRIPTION:
END DESCRIPTION:
Bridge Culvert--1,0,-1,-1, 0
Deck Dist Width WeirC Skew NumUp NumDn MinLoCord MaxHiCord MaxSubmerge Is_Ogee
38.191250,38.000000,2.6,0, 50, 50, , , 0.95, 0, 0,0,,
 9616.24 9630.57 9640.69 9650.81 9660.93 9681.16 9701.40 9711.52 9721.63 9735.50
 9751.95 9762.02 9772.08 9782.15 9792.22 9802.29 9812.35 9822.42 9842.56 9852.63
 9862.69 9872.76 9892.90 9923.12 9929.32 9972.21 9972.2110029.2110029.2110068.69
10075.0110085.1410105.3910115.5210125.6410145.8710155.9610176.1410186.2410196.33
10206.4210246.7910277.0610297.2410347.7010388.0710438.5310509.1710539.4410565.72
  216.68  216.14  215.67  215.34  214.31  213.58  212.39  212.54  211.40  210.91
  210.49  210.02  209.87  209.52  209.31  208.78  208.49  208.00  207.29  207.16
  206.93  206.86  206.88  207.43  207.69  208.97  208.97  210.68  210.68  211.86
  212.40  212.84  213.53  214.00  214.78  215.76  216.47  217.65  218.41  218.99
  219.79  223.36  226.18  228.15  232.84  236.73  241.36  248.52  251.12  253.15
 -783.32 -783.86 -784.33 -784.66 -785.69 -786.42 -787.61 -787.46 -788.60 -789.09
 -789.51 -789.98 -790.13 -790.48 -790.69 -791.22 -791.51 -792.00 -792.71 -792.84
 -793.07 -793.14 -793.12 -792.57 -792.31 -791.03  205.47  207.18 -789.32 -788.14
 -787.60 -787.16 -786.47 -786.00 -785.22 -784.24 -783.53 -782.35 -781.59 -781.01
 -780.21 -776.64 -773.82 -771.85 -767.16 -763.27 -758.64 -751.48 -748.88 -746.85
 9616.24 9630.57 9640.69 9650.81 9660.93 9681.16 9701.40 9711.52 9721.63 9735.50
 9751.95 9762.02 9772.08 9782.15 9792.22 9802.29 9812.35 9822.42 9842.56 9852.63
 9862.69 9872.76 9892.90 9923.12 9929.32 9968.27 9968.2710025.2710025.2710068.69
10075.0110085.1410105.3910115.5210125.6410145.8710155.9610176.1410186.2410196.33
10206.4210246.7910277.0610297.2410347.7010388.0710438.5310509.1710539.4410565.72
  216.68  216.14  215.67  215.34  214.31  213.58  212.39  212.54  211.40  210.91
  210.49  210.02  209.87  209.52  209.31  208.78  208.49  208.00  207.29  207.16
  206.93  206.86  206.88  207.43  207.69  208.85  208.85  210.56  210.56  211.86
  212.40  212.84  213.53  214.00  214.78  215.76  216.47  217.65  218.41  218.99
  219.79  223.36  226.18  228.15  232.84  236.73  241.36  248.52  251.12  253.15
 -783.32 -783.86 -784.33 -784.66 -785.69 -786.42 -787.61 -787.46 -788.60 -789.09
 -789.51 -789.98 -790.13 -790.48 -790.69 -791.22 -791.51 -792.00 -792.71 -792.84
 -793.07 -793.14 -793.12 -792.57 -792.31 -791.15  205.35  207.06 -789.44 -788.14
 -787.60 -787.16 -786.47 -786.00 -785.22 -784.24 -783.53 -782.35 -781.59 -781.01
 -780.21 -776.64 -773.82 -771.85 -767.16 -763.27 -758.64 -751.48 -748.88 -746.85
BR Coef=-1 , 0 , 0 ,, 0 ,,,0.8,0,1,0,
WSPro=,,,, 1 ,,,, 0 ,,,, 0 ,,,,-1 ,-1 ,-1 , 0 , 0 , 0 , 0 , 0
BC Design=,, 0 ,, 0 ,,,,,,

Type RM Length L Ch R = 1 ,38021.78,661.928400,661.928400,661.928400
XS GIS Cut Line= 6
603822.214771062738426.172950119603549.774972856738341.311739266
603158.583263665738347.064558536602998.901510239738322.160064861
602625.334105432 738282.60586904602493.486786067738266.491196692
#Sta/Elev= 30
9225.383225.34679264.362222.46729316.731223.65719337.679225.5885 9421.47226.8446
9442.418 224.4749464.706218.79689595.518214.63719635.522214.34749685.528218.0734
9715.531217.91679755.535205.41199775.537202.24419925.836200.81379996.682191.1572
10027.04193.085810037.17195.5211 10067.5208.616210077.56210.411510097.67210.6773
10107.73207.675610127.84205.618110158.01214.850310226.55223.034410248.51227.2196
10369.18237.3683 10409.4238.5356 10469.8244.161410510.09245.687410572.06252.3164
#Mann= 3 , 0 , 0
9225.383    0.12       09225.383    0.12       010572.06    0.12       0
#XS Ineff= 2 , 0
       09749.274        10076.47       0
Bank Sta=9225.383,10572.06
Exp/Cntr=0.3,0.1