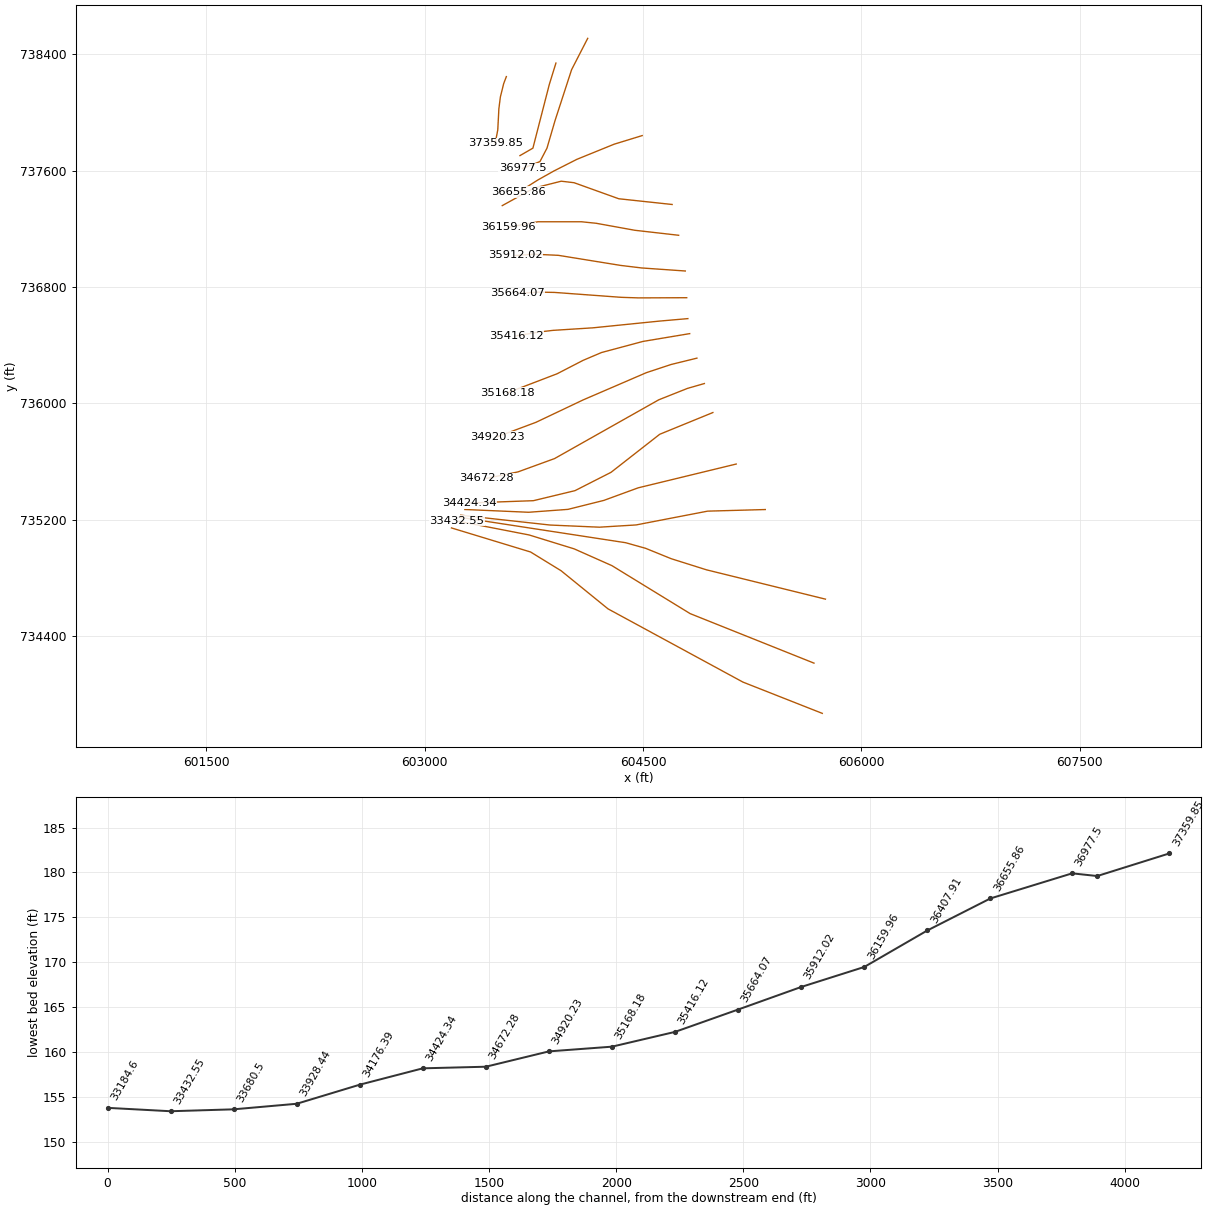
HEC-RAS study 2027_ras.prj: 2027

--- 2027_ras.g01 (geometry) --- (continued)

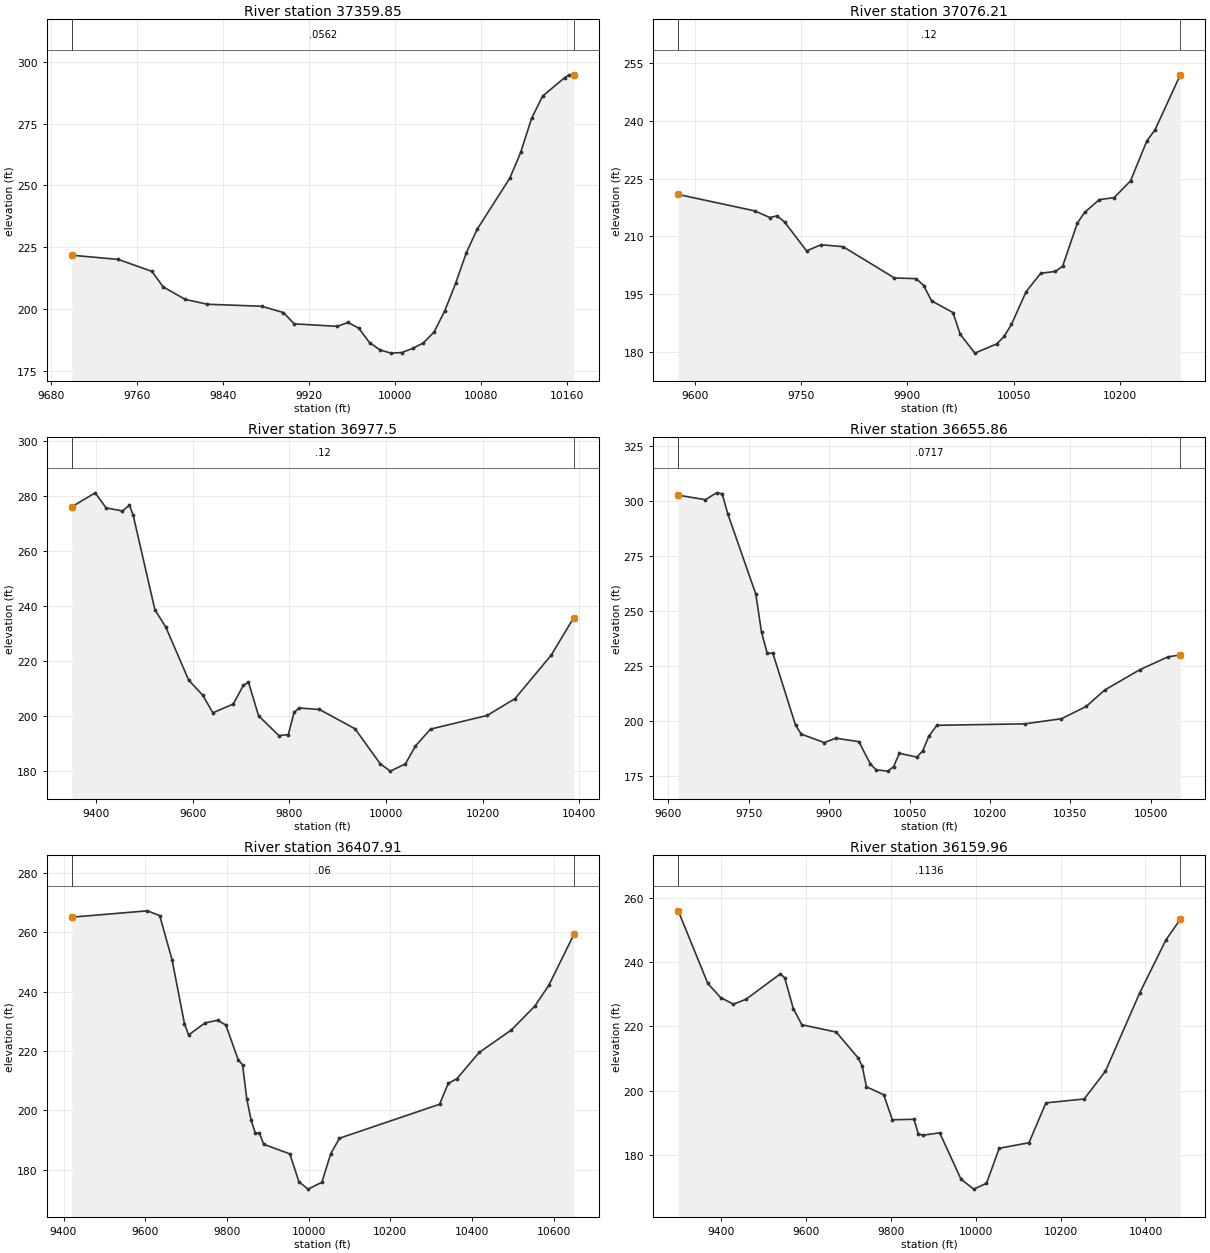
Type RM Length L Ch R = 1 ,37359.85,283.642200,283.642200,283.642200
XS GIS Cut Line= 6
  603560.7038329738245.415294837603542.285292988738196.748672161
603519.681868984738105.625014299603509.374479157  738024.2043538
603501.786144283737879.392363528  603483.9894994737786.700631679
#Sta/Elev= 30
9699.142221.73499742.355220.03159773.813215.18019784.221208.93319804.848203.8509
9825.303201.90729876.104201.06789896.257198.5229 9906.31193.95349946.436192.9627
9956.445194.51819966.453192.18929976.462186.37229986.471183.36769996.479182.1195
10006.49182.359510016.49184.0054 10026.5186.233810036.53190.646610046.56199.2751
10056.59210.294610066.63222.7977 10076.7 232.23910107.06252.890110117.18263.2782
10127.33277.055810137.61286.084310158.18293.564110162.37 294.69810166.71 294.454
#Mann= 3 , 0 , 0
9699.142  0.0562       09699.142  0.0562       010166.71  0.0562       0
#XS Ineff= 2 , 0
       0                               0
Bank Sta=9699.142,10166.71
Exp/Cntr=0.3,0.1

Type RM Length L Ch R = 1 ,37076.21,98.705400,98.705400,98.705400
XS GIS Cut Line= 4
603901.323162645738338.274737224603855.909085989738191.777715713
603743.106379509737753.751621455603654.134471267737702.496065617
#Sta/Elev= 30
9576.686220.89599684.809216.61689705.748214.89399716.217215.32719726.687213.7295
9757.712206.22669778.364207.81449809.343207.29479881.627199.16899912.606198.9767
9922.932197.19879934.196193.20059964.237190.16179974.564184.49749995.216179.5982
10026.19182.014110036.52183.946210046.85187.0934 10067.5195.594310088.15200.3911
10108.81 200.86210119.13202.264910139.78213.443610150.11216.243510170.76219.5477
10191.73220.074410214.81224.4285 10237.9234.859810249.44237.738310285.06252.0321
#Mann= 3 , 0 , 0
9576.686    0.12       09576.686    0.12       010285.06    0.12       0
#XS Ineff= 2 , 0
       09799.506                       0
Bank Sta=9576.686,10285.06
Exp/Cntr=0.3,0.1

Type RM Length L Ch R = 1 , 36977.5,321.647900,321.647900,321.647900
XS GIS Cut Line= 6
604119.603724688738508.211282164604008.844483435738292.637539834
 603895.46328181737944.197749406603839.794413626737753.751621455
603791.450396538737661.458497912603671.322838902737614.579451054
#Sta/Elev= 30
9348.905276.16219397.486281.25899419.971 275.7779453.699274.66019468.388276.7807
9476.185273.05539521.155238.66629543.641232.39999591.267213.02499620.331207.5341
9641.363  201.149683.428204.3342 9704.46  211.129714.976212.31619736.008200.0672
9778.073192.83199797.598 193.1939809.621201.33849820.137202.88899862.202202.3448
9935.814195.3272 9988.11182.552910008.95179.8979 10040.2182.526810061.04 189.046
10092.29195.200310209.54 200.17310267.22206.284810342.36222.144210389.24235.8507
#Mann= 3 , 0 , 0
9348.905    0.12       09348.905    0.12       010389.24    0.12       0
#XS Ineff= 2 , 0
       09836.984                       0
Bank Sta=9348.905,10389.24
Exp/Cntr=0.3,0.1

Type RM Length L Ch R = 1 ,36655.86,247.946600,247.946600,247.946600
XS GIS Cut Line= 6
604493.915407386 737840.19188071604300.563271334737780.737630609
604045.077292571737676.973235002603887.148762961737596.894539473
603776.839094577737534.931697798603645.759711129737452.190139999
#Sta/Elev= 30
9618.358302.61679668.977300.57479689.853303.69019700.291303.27519710.729 294.208
9763.193257.55399773.763240.29849784.333230.75239794.903230.72819837.369197.8977
9848.059193.93139890.819190.07089912.263192.08469955.349190.51449976.892180.3467
9987.664177.683110009.27177.098310020.09179.109410030.94185.194410063.79183.4778
10074.74186.432410085.69192.865610100.92197.947410264.82198.603310333.44200.9404
10379.59206.527510414.04213.965110479.59223.233210532.23229.088310555.17229.9615
#Mann= 3 , 0 , 0
9618.358  0.0717       09618.358  0.0717       010555.17  0.0717       0
#XS Ineff= 2 , 0
       0                               0
Bank Sta=9618.358,10555.17
Exp/Cntr=0.3,0.1

Type RM Length L Ch R = 1 ,36407.91,247.946600,247.946600,247.946600
XS GIS Cut Line= 6
604699.551829755737366.870705098604332.996544272  737406.1750274
 604026.01130271737516.416178763603937.660560131737526.860207796
603750.583737642737479.404343441603532.598256735737359.100417465
#Sta/Elev= 30
9420.206 265.0799605.339267.21489635.505265.60029665.671250.75079696.003229.2616
9706.122225.43599746.597229.48769776.954230.37389797.281228.78349827.973216.9131
9838.204215.41039848.553203.91779858.916196.96159869.278 192.4759879.641192.3133
9890.049188.62619953.945 185.3969976.182 176.0139998.482173.529810032.32175.8322
10054.23185.483510075.52190.667310320.49202.093610341.58 209.09510363.06210.7223
10417.26219.523610495.95227.069210553.39235.101110588.08242.186910649.15259.2647
#Mann= 3 , 0 , 0
9420.206    0.06       09420.206    0.06       010649.15    0.06       0
#XS Ineff= 2 , 0
       0                               0
Bank Sta=9420.206,10649.15
Exp/Cntr=0.3,0.1

Type RM Length L Ch R = 1 ,36159.96,247.946600,247.946600,247.946600
XS GIS Cut Line= 6
 604744.32593891 737155.35163781 604443.99600476737189.563029736
604177.474144608 737237.73740603 604076.64533636737248.116966754
603776.948971033737248.118277445603572.480553985737209.239664145
#Sta/Elev= 30
9299.217255.94279368.815233.40099398.947229.00649429.129226.93029459.311228.4929
9539.972236.37389550.066235.12739570.254225.57329590.443 220.5469671.499218.2657
9722.301210.35359732.475207.7729 9742.65201.25299783.349198.79839803.698191.0145
9854.571191.16649864.746186.71279874.898 186.2059915.236186.95239965.472172.5419
9995.483169.462210025.48 171.26910055.48182.1661 10125.5183.875110165.51196.2676
10255.55197.468910305.74206.108810386.76230.527310448.52246.968610482.12  253.31
#Mann= 3 , 0 , 0
9299.217  0.1136       09299.217  0.1136       010482.12  0.1136       0
#XS Ineff= 2 , 0
       0                               0
Bank Sta=9299.217,10482.12
Exp/Cntr=0.3,0.1

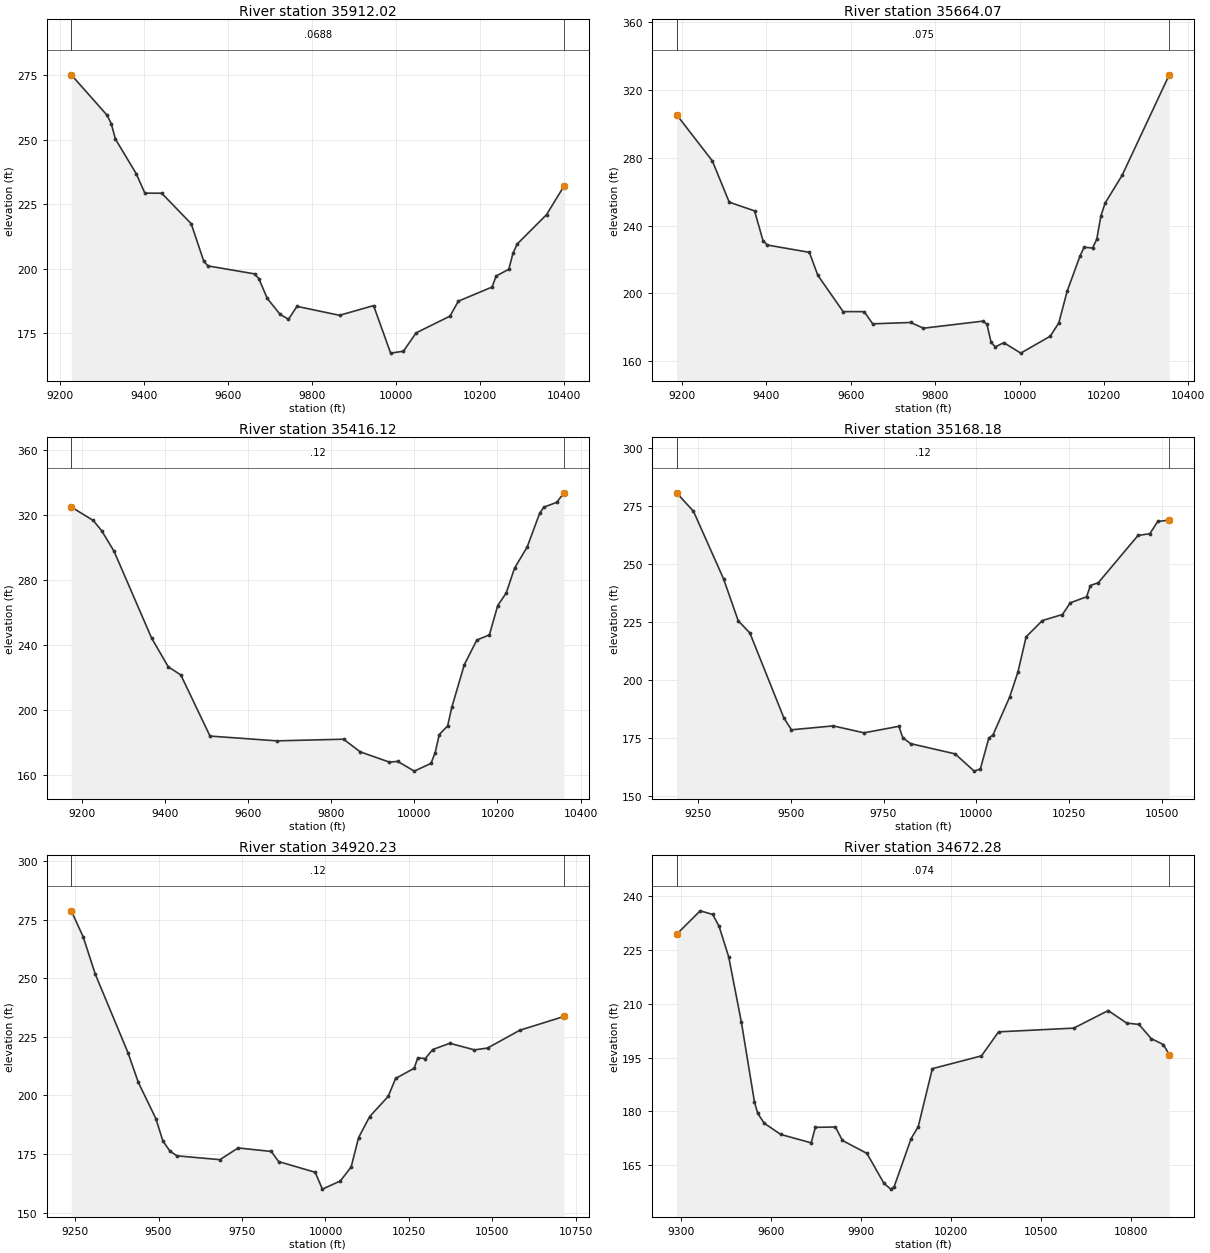
Type RM Length L Ch R = 1 ,35912.02,247.946600,247.946600,247.946600
XS GIS Cut Line= 6
604790.063416183 736909.92232658604490.594752163736930.793666407
604346.531984538736948.195124328603917.924714059737017.540802449
603750.699402303737025.436638504 603623.79145591737016.435062946
#Sta/Elev= 30
9226.533275.1784 9311.71259.53439321.727256.27299331.744250.26039381.359236.8027
9401.906229.28739442.053229.25739512.311217.43459542.477202.8185 9552.55201.0566
9663.349197.97349673.429196.14649693.663 188.4559724.014182.30539744.248180.3661
9764.482185.37679865.853181.90099947.097185.66889987.719167.233710018.16167.9834
10048.49175.095210129.12 181.58510149.19187.400110229.32192.850510239.32 197.161
10269.32199.757910279.33205.947410289.34209.5554 10359.5220.974410400.89232.0219
#Mann= 3 , 0 , 0
9226.533  0.0688       09226.533  0.0688       010400.89  0.0688       0
#XS Ineff= 2 , 0
       09772.388                       0
Bank Sta=9226.533,10400.89
Exp/Cntr=0.3,0.1

Type RM Length L Ch R = 1 ,35664.07,247.946600,247.946600,247.946600
XS GIS Cut Line= 6
604799.891815871736726.458865583604468.101841599736725.232947424
604350.734829873736729.046013996603891.612515837 736762.76341413
603783.203812003736764.795718104 603633.45330449736756.007277505
#Sta/Elev= 30
9186.884305.50569271.787278.15959311.793253.81679371.793248.69349391.793231.1988
9401.794228.55089501.794224.21179521.796210.66049581.828189.23549631.854189.1909
9651.881182.01969742.053182.8113 9772.16179.42549912.657183.58989922.692181.8675
9932.728 171.0239942.763168.42799962.834170.890810002.95164.719710073.08174.7395
10093.12182.554610113.13 201.38210143.14221.845910153.14227.255810173.14226.7481
10183.14231.915210193.15245.866710203.15253.356210243.17269.612710355.01328.9936
#Mann= 3 , 0 , 0
9186.884   0.075       09186.884   0.075       010355.01   0.075       0
#XS Ineff= 2 , 0
       0                               0
Bank Sta=9186.884,10355.01
Exp/Cntr=0.3,0.1

Type RM Length L Ch R = 1 ,35416.12,247.946600,247.946600,247.946600
XS GIS Cut Line= 6
604807.584773213736582.856995031604611.994741797736565.741909042
604154.728674948736519.513047799603880.761732519736502.070400566
603787.585155755736491.252783209603627.802549808736464.051618709
#Sta/Elev= 30
9173.791324.76999226.576316.50349246.653310.28329276.767297.52059367.111244.1459
9407.311226.42389437.464221.44029507.821183.80169668.637180.86179829.452 181.875
9869.528174.10369939.658167.77849959.696168.2316 9999.77162.230110039.86167.0043
10049.88173.533610059.91184.765910079.95190.048310089.98201.463210120.12227.7345
10150.32242.898310180.52246.097110200.67264.156210220.91271.792510241.15287.1668
10271.51300.153410301.95321.183710312.13324.713910342.65327.664410360.15333.5031
#Mann= 3 , 0 , 0
9173.791    0.12       09173.791    0.12       010360.15    0.12       0
#XS Ineff= 2 , 0
       0                               0
Bank Sta=9173.791,10360.15
Exp/Cntr=0.3,0.1

Type RM Length L Ch R = 1 ,35168.18,247.946600,247.946600,247.946600
XS GIS Cut Line= 6
604820.257885486736479.711706102604499.211671144736426.153184742
604214.545843244736349.895684585604088.368137807736296.348330244
603909.493337065736203.989609331603565.588763667736072.272767759
#Sta/Elev= 30
9192.365280.63819237.973272.68189318.977243.53939358.437225.46339389.918220.1653
9481.462183.54119501.846178.41539614.596180.09579697.305177.10729791.341179.9152
9801.839175.00359823.042172.43919942.647168.0342  9994.3160.582410010.86161.5304
 10033.6174.804110044.98176.246610089.98192.613510112.09 203.33610134.21218.5301
10177.88225.5411   10232228.145510253.16233.194810296.86235.778310307.53240.6547
10328.87241.902910435.56262.245210467.55 263.00910488.67268.272510519.73268.8785
#Mann= 3 , 0 , 0
9192.365    0.12       09192.365    0.12       010519.73    0.12       0
#XS Ineff= 2 , 0
       0                               0
Bank Sta=9192.365,10519.73
Exp/Cntr=0.3,0.1

Type RM Length L Ch R = 1 ,34920.23,247.946600,247.946600,247.946600
XS GIS Cut Line= 6
604869.746347576736311.277291298604691.855314076736267.536426991
604522.721156716736211.587135643604088.813131183736024.618921295
  603763.4022066735870.171024621603499.765679317735771.792046245
#Sta/Elev= 30
9238.677278.74099274.319267.61979310.627251.69099408.269218.30989439.545205.5471
9491.891190.1626 9512.83180.67269533.984176.28449555.211174.25829683.877172.6206
9738.398177.61349837.654176.13459859.748171.81129969.262167.24339990.776160.0567
10044.56163.535710076.98169.498910099.17182.006110132.46 190.99310187.95199.6063
10210.14207.262710265.63211.581510276.72216.085110298.92215.738310321.11219.5677
 10372.5222.260810446.38219.435210485.43220.2219 10582.1227.804710714.51 233.707
#Mann= 3 , 0 , 0
9238.677    0.12       09238.677    0.12       010714.51    0.12       0
#XS Ineff= 2 , 0
       0                               0
Bank Sta=9238.677,10714.51
Exp/Cntr=0.3,0.1

Type RM Length L Ch R = 1 ,34672.28,247.946600,247.946600,247.946600
XS GIS Cut Line= 6
604920.998650074736136.839630321604804.786435395736103.460211471
604607.707593173736025.120239168603891.955015719735621.391998336
603640.367281765735529.780350164603425.582193851735485.655745132
#Sta/Elev= 30
9284.677229.36139363.473 235.9199405.393234.90239426.637231.56299458.508223.0913
9501.002 204.8099544.542182.59659555.428179.4451  9577.2 176.7129632.038173.5893
9733.512171.2499 9747.47175.56789814.471175.66579837.808171.90669919.485168.3064
9976.355159.94619998.913158.347410010.19159.0154 10066.9 172.45210090.46175.7374
10137.59191.925610301.47195.491910358.44202.186910609.13203.223510723.95208.1179
 10785.7204.618210826.53204.263110867.29200.309310907.82198.6489 10927.5195.8447
#Mann= 3 , 0 , 0
9284.677   0.074       09284.677   0.074       0 10927.5   0.074       0
#XS Ineff= 2 , 0
       0                10083.24       0
Bank Sta=9284.677,10927.5
Exp/Cntr=0.3,0.1

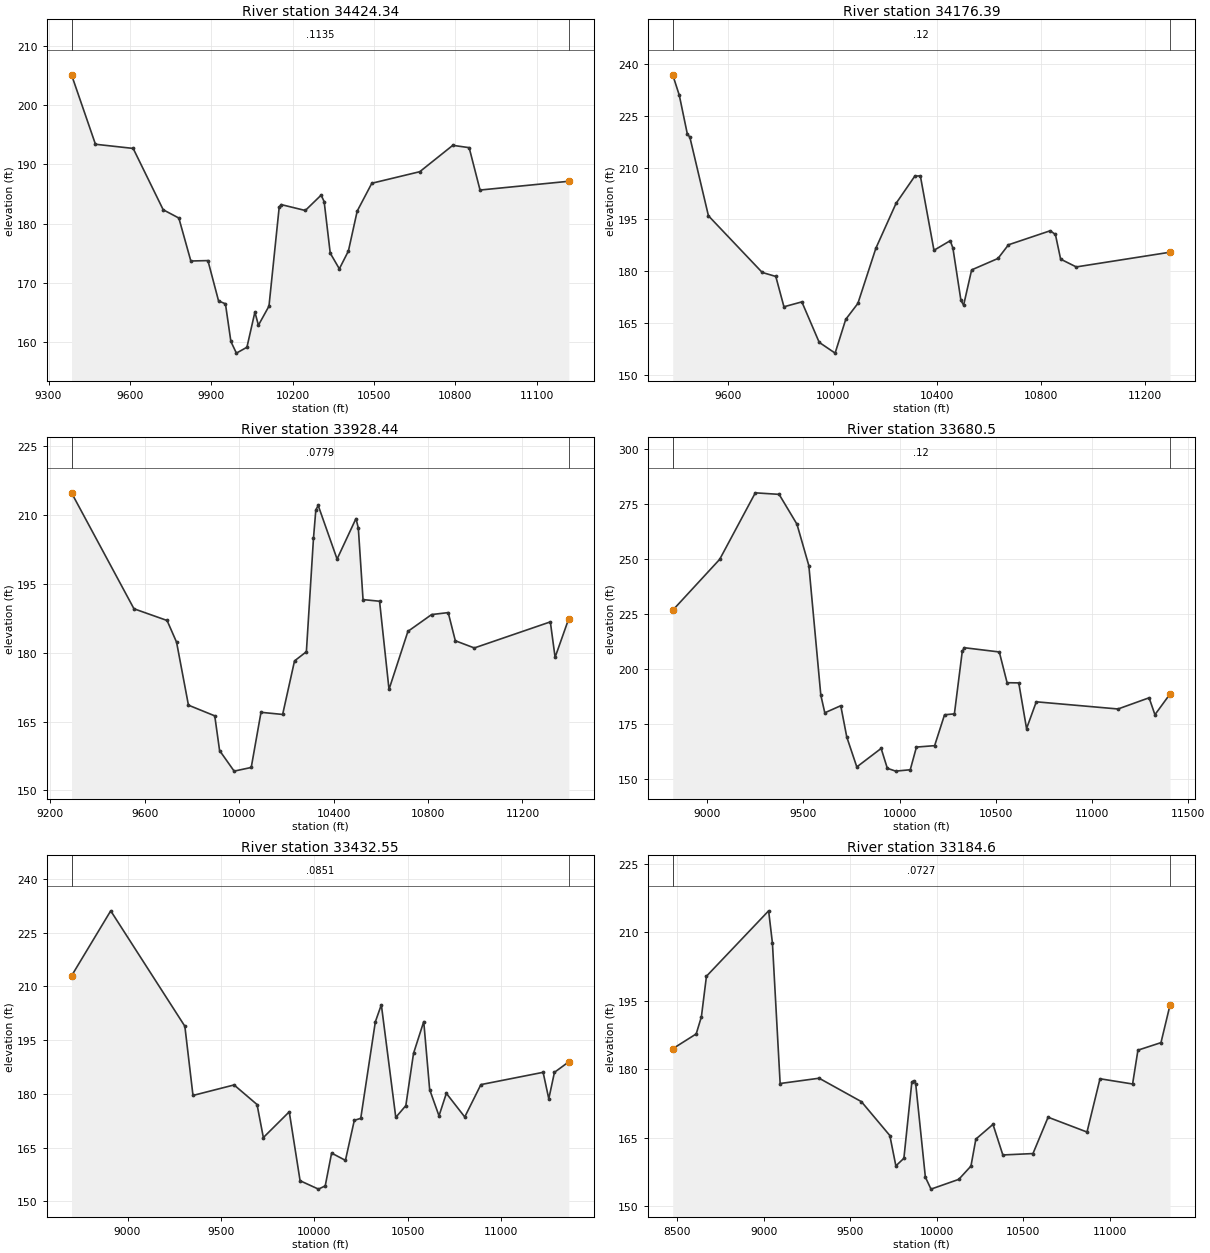
Type RM Length L Ch R = 1 ,34424.34,247.946500,247.946500,247.946500
XS GIS Cut Line= 6
604979.537003812735937.603829758  604614.3890315735788.345659062
604279.872925878735526.979994133604032.497541517735401.081714109
603746.427179903735332.106255427603307.892523378 735316.34455502
#Sta/Elev= 30
 9384.81205.11039473.003193.39969612.054192.69719722.693182.35289780.419 180.954
9824.625173.70759887.628173.77729926.858166.96949952.201166.48479972.268160.1306
9992.556158.168710031.41159.159410060.78165.088210073.78162.876310112.71166.0987
10150.38182.794310157.54183.2248 10246.6182.2288 10304.9184.8169 10316.1183.7312
10338.49175.036110372.09 172.38610405.49175.394710437.94182.130610491.85186.8221
 10668.6188.770810790.28193.217310850.63192.827510890.74185.676211218.01187.1561
#Mann= 3 , 0 , 0
 9384.81  0.1135       0 9384.81  0.1135       011218.01  0.1135       0
#XS Ineff= 2 , 0
       0                10174.01       0
Bank Sta=9384.81,11218.01
Exp/Cntr=0.3,0.1

Type RM Length L Ch R = 1 ,34176.39,247.946600,247.946600,247.946600
XS GIS Cut Line= 6
605139.912524888735583.914620639604466.531745434735420.448849589
604230.937574327735334.248633474603984.354518294735272.494015336
603714.090068281735252.541773796603275.513348013735271.630455673
#Sta/Elev= 30
9386.254236.83529411.565 230.9039442.045219.82169452.205218.7505 9523.38196.0623
 9729.85 179.6829782.014178.52189813.313169.74979882.052171.16699948.685159.4629
10009.76156.344910050.59166.113110097.17 170.72110166.24186.675810243.56199.6318
10315.83207.539610337.07207.610710389.36186.088110451.88 188.86310462.14 186.701
10492.92171.575910503.18170.212510533.94180.414810635.17183.725810675.39187.6778
10835.68191.737310855.68190.656310875.68183.531110935.69181.275611295.67185.5327
#Mann= 3 , 0 , 0
9386.254    0.12       09386.254    0.12       011295.67    0.12       0
#XS Ineff= 2 , 0
       0                10146.14       0
Bank Sta=9386.254,11295.67
Exp/Cntr=0.3,0.1

Type RM Length L Ch R = 1 ,33928.44,247.946600,247.946600,247.946600
XS GIS Cut Line= 6
605339.500872803735271.306364855604942.938004017735260.253221601
 604451.72153917735165.470818445604199.515120625735150.059159383
603861.159925759735164.797023445 603247.12717849735232.430507258
#Sta/Elev= 30
9289.241214.8263  9553.8189.57599694.127187.02449734.371182.29649784.676168.5844
9896.185166.25749916.664158.70399978.327154.218310050.76155.016810092.17167.0262
10183.88166.562410234.25178.224210284.46180.218610314.51204.904510324.52211.1012
10334.52212.076710414.56200.403310494.58209.215810504.58207.163210524.58191.5747
 10594.6191.217510634.66 172.01510714.79184.655610815.17188.315510885.52188.7435
10915.67182.607810996.16181.043811318.32186.720911338.44 179.00511396.59187.4512
#Mann= 3 , 0 , 0
9289.241  0.0779       09289.241  0.0779       011396.59  0.0779       0
#XS Ineff= 2 , 0
       0                10345.67       0
Bank Sta=9289.241,11396.59
Exp/Cntr=0.3,0.1

Type RM Length L Ch R = 1 , 33680.5,247.946600,247.946600,247.946600
XS GIS Cut Line= 6
 605752.68362301734655.804154504604935.489743114734857.171707377
604693.370753497734933.444197774604517.448193669735004.865323097
604380.095487952  735043.4211348603237.126640201735218.620240122
#Sta/Elev= 30
8820.608 226.7639064.765249.92919249.895280.16239373.573279.46479466.332265.8988
9528.207247.0224 9590.33188.15959611.037180.12459694.034 183.348 9725.26169.1091
 9777.42155.50549903.887163.92019936.057154.8945 9979.26 153.59910055.26154.2276
10087.34164.533710181.89165.182410233.46179.221910284.65179.638410325.47208.0059
10335.65209.731310518.05 207.79110558.52193.813910619.23193.721110659.71172.9564
 10710.3185.125311135.09181.860711296.68186.948411326.98179.258211405.35188.6576
#Mann= 3 , 0 , 0
8820.608    0.12       08820.608    0.12       011405.35    0.12       0
#XS Ineff= 2 , 0
       0                10363.95       0
Bank Sta=8820.608,11405.35
Exp/Cntr=0.3,0.1

Type RM Length L Ch R = 1 ,33432.55,247.946600,247.946600,247.946600
XS GIS Cut Line= 6
605673.943271132734216.210406633604823.525413781734556.219127968
604285.578924477734886.068506837604026.771385789735001.073727429
603716.958336711735096.695107698603218.901141495 735193.45169428
#Sta/Elev= 30
8700.032212.90798909.988231.0676 9307.15198.85519350.728179.53779570.898182.4677
9693.917177.00329727.698167.77729866.478174.96779924.474155.731410022.93153.3864
10059.22154.292510093.36 163.44510167.42161.4169   10215172.590110249.48173.1441
10327.79200.101310359.85204.849610437.22173.413410491.07176.698510532.24191.2753
10587.02200.149710618.76181.154810668.76173.8408 10708.1180.133110806.71173.5285
 10893.1182.558811226.55185.990111256.92178.609911287.29185.989411364.22 188.923
#Mann= 3 , 0 , 0
8700.032  0.0851       08700.032  0.0851       011364.22  0.0851       0
#XS Ineff= 2 , 0
       09829.282        10302.68       0
Bank Sta=8700.032,11364.22
Exp/Cntr=0.3,0.1

Type RM Length L Ch R = 1 , 33184.6,495.893200,495.893200,495.893200
XS GIS Cut Line= 6
605730.983757032733871.042338173605186.013844848734085.893649101
604259.006220877734589.046823904603936.805952817734850.818535596
 603727.00569576734979.682029232603183.762070656735144.926310748
#Sta/Elev= 30
 8474.32184.49838609.969187.74038639.965191.48628669.221 200.3699028.588214.6891
9050.606207.60059095.137176.8867 9320.48178.0439 9564.66172.91699729.073 165.499
9763.988158.85339810.355160.51689856.289177.1894 9868.07177.49379878.744176.7836
9934.446156.38859967.025 153.76410127.57155.902410197.96158.810710226.26164.7143
10325.26167.944410382.25 161.243 10556.4161.550710643.79169.506210868.63166.2629
10943.78177.925911132.13  176.7811162.99184.185311296.17185.833811348.37194.0569
#Mann= 3 , 0 , 0
 8474.32  0.0727       0 8474.32  0.0727       011348.37  0.0727       0
#XS Ineff= 2 , 0
       09843.876        10254.67       0
Bank Sta=8474.32,11348.37
Exp/Cntr=0.3,0.1