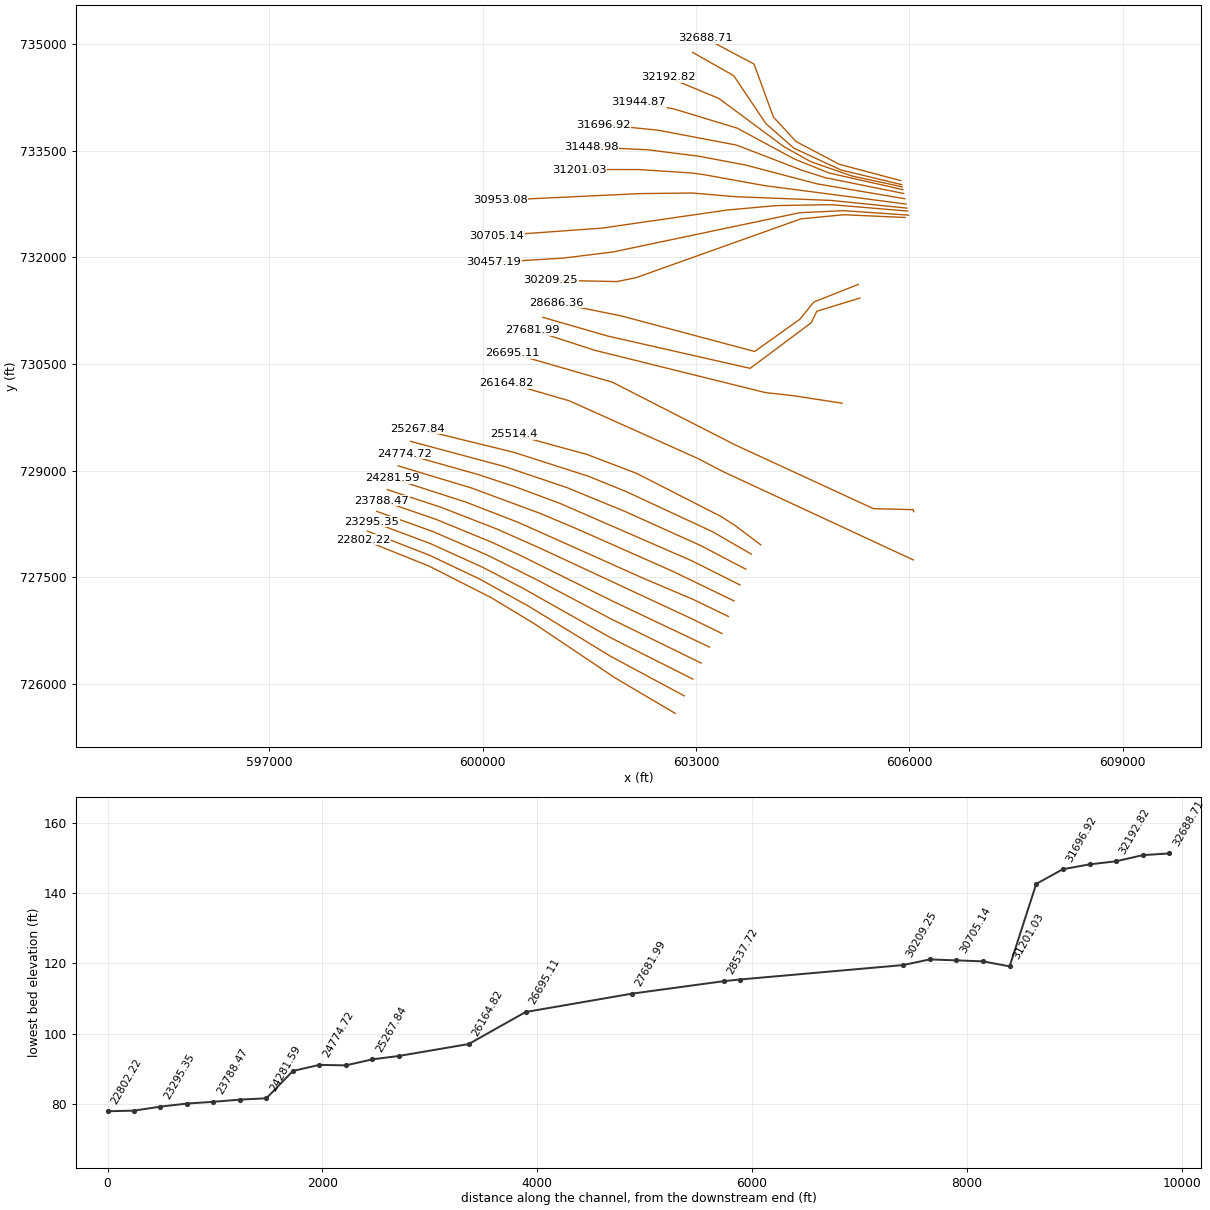
HEC-RAS study 2027_ras.prj: 2027

--- 2027_ras.g01 (geometry) --- (continued)

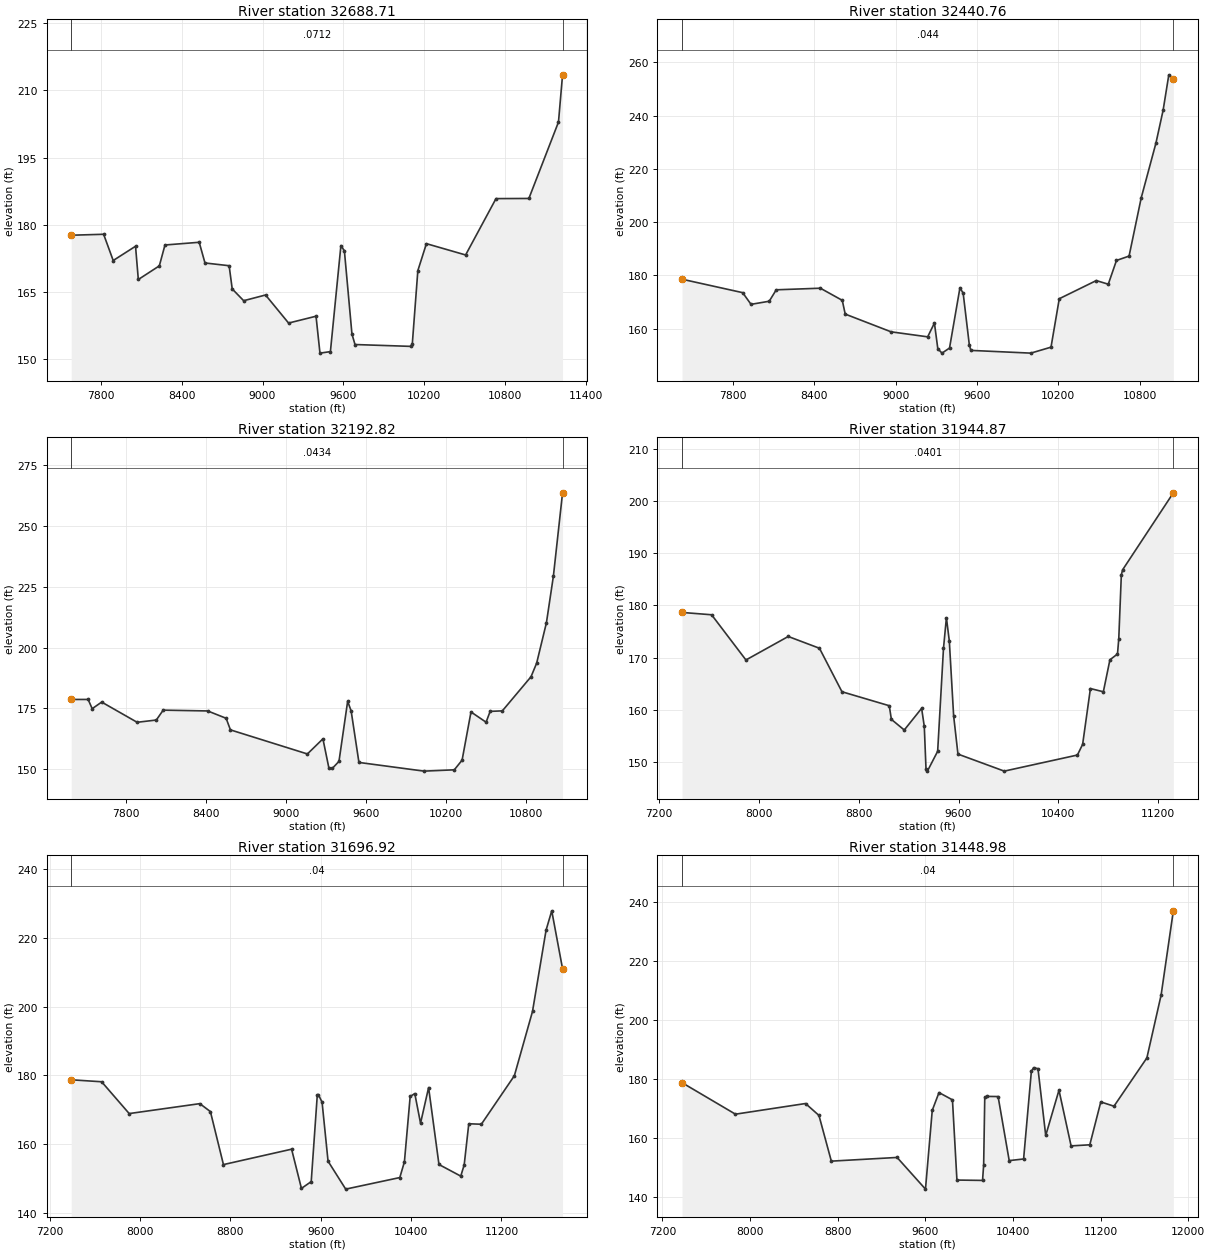
Type RM Length L Ch R = 1 ,32688.71,247.946600,247.946600,247.946600
XS GIS Cut Line= 6
605879.813047917733078.001943868 605015.13034296733307.901557595
604408.521008104733626.980651483604089.880480587733971.145991802
603817.190039426734716.223194525603135.633122414735078.462525085
#Sta/Elev= 30
7580.798177.6547 7821.11177.86647892.163172.00778057.789175.19358078.476167.7697
8234.328170.81348276.196175.47358530.074176.08018572.977171.46038752.114170.8458
8775.019165.66198859.931163.03299022.301164.31029193.167158.04379396.758159.5712
9425.969151.3304 9503.38151.66699581.326175.34689607.158174.17049663.194155.6011
9685.855153.249910100.55 152.83610110.78153.314910152.03169.749910215.59175.7702
10506.41173.246210731.79185.829510975.75185.862211195.29202.920811225.55213.4663
#Mann= 3 , 0 , 0
7580.798  0.0712       07580.798  0.0712       011225.55  0.0712       0
#XS Ineff= 2 , 0
       09585.622                       0
Bank Sta=7580.798,11225.55
Exp/Cntr=0.3,0.1

Type RM Length L Ch R = 1 ,32440.76,247.946600,247.946600,247.946600
XS GIS Cut Line= 6
605892.388055793 733022.08329181605041.323814332733226.926045194
604380.046954155733532.096171364603983.666884542 733879.27350086
603531.768886715734553.471571699602953.201436013 734881.51834701
#Sta/Elev= 30
7425.464178.58717872.488173.53917934.258  169.15 8068.41170.31558120.232174.6085
 8445.54175.20848606.963170.64998628.695165.49148966.919158.83069236.547156.9506
9286.282 162.1159311.483152.4579 9342.28150.83719397.692152.74729474.617175.3958
9498.351173.30829543.523153.98659554.872151.86079997.112150.834210145.87153.0712
10206.82171.260310479.64 178.07210568.13 176.71410628.44185.629110721.37187.2677
 10810.8209.111510919.04229.6111 10972.4242.035911014.36255.321711047.71253.9294
#Mann= 3 , 0 , 0
7425.464   0.044       07425.464   0.044       011047.71   0.044       0
#XS Ineff= 2 , 0
       09478.566                       0
Bank Sta=7425.464,11047.71
Exp/Cntr=0.3,0.1

Type RM Length L Ch R = 1 ,32192.82,247.946500,247.946500,247.946500
XS GIS Cut Line= 6
 605899.39639025732990.918570498605193.335839331 733143.38677609
604618.035763711733342.495730653604235.052266866733557.140421763
603323.486545384734233.065911412602608.393221825734530.660865888
#Sta/Elev= 30
7391.252178.6111 7517.93178.6205 7548.48174.81927619.764177.53967885.609169.2102
8029.542170.1469  8081.1174.21858414.906173.88278553.223 170.8638585.405166.0879
 9162.84156.16519279.295162.39289323.564150.51279348.973150.1771 9399.79153.1208
9464.859177.87799491.084173.86919549.427152.673710037.53149.093710264.91 149.634
10323.25153.614610390.03173.466910503.25 169.25110533.74173.709510625.29173.9224
10840.49187.993310882.62193.582610955.99210.246811008.06229.3728 11076.9263.7362
#Mann= 3 , 0 , 0
7391.252  0.0434       07391.252  0.0434       0 11076.9  0.0434       0
#XS Ineff= 2 , 0
       09474.865                       0
Bank Sta=7391.252,11076.9
Exp/Cntr=0.3,0.1

Type RM Length L Ch R = 1 ,31944.87,247.946600,247.946600,247.946600
XS GIS Cut Line= 6
 605908.20080063732951.767043478604874.708409131733184.682090655
604378.229072869733384.727258429603583.922026455733814.518682927
 602692.20018062734085.535117745602195.407658339  734182.4648422
#Sta/Elev= 30
7382.982178.64137620.205178.19437895.448169.52568234.705174.03198484.948171.7715
8665.278163.43219044.502160.75169061.496158.13479164.736156.09629303.944160.2518
9325.283156.78739339.008148.66919350.696148.22929432.512152.02119479.264171.7638
 9502.64177.62669525.903173.17769560.572  158.819595.241 151.4779966.426148.2114
   10553151.2982 10594.8153.353810657.16164.0472 10760.8163.428510813.48 169.558
10874.25170.673210884.51173.626610905.05185.856410915.32186.819411321.91201.5781
#Mann= 3 , 0 , 0
7382.982  0.0401       07382.982  0.0401       011321.91  0.0401       0
#XS Ineff= 2 , 0
       09509.926        10291.37       0
Bank Sta=7382.982,11321.91
Exp/Cntr=0.3,0.1

Type RM Length L Ch R = 1 ,31696.92,247.946600,247.946600,247.946600
XS GIS Cut Line= 6
605920.514667665732897.009634739604813.886008322 733120.50900209
604487.093104571733224.980345041603571.605765283733577.495950103
602462.367526323733788.223661616601699.425913721733863.311371744
#Sta/Elev= 30
7390.268178.68367659.473178.10937903.462168.8447 8529.03171.73758622.783169.4191
8738.162153.98269341.744158.47069428.842147.04339515.509149.02189568.948174.1087
9579.634174.32169611.692172.15159664.602154.96859820.932146.834810300.04150.2049
10340.83154.786210391.81173.8202 10432.6174.671210483.59166.030510554.97176.4275
10646.75154.0095 10839.9150.6228 10870.3153.921710910.83165.875411022.11165.7364
11314.42179.8605 11475.1198.592211595.44222.297911645.54 227.90411741.26211.0309
#Mann= 3 , 0 , 0
7390.268    0.04       07390.268    0.04       011741.26    0.04       0
#XS Ineff= 2 , 0
       0 9701.34        10198.32       0
Bank Sta=7390.268,11741.26
Exp/Cntr=0.3,0.1

Type RM Length L Ch R = 1 ,31448.98,247.946600,247.946600,247.946600
XS GIS Cut Line= 6
 605937.06042165732823.433835091604706.166111827733032.188347444
603699.461322516733296.846674278603037.451922297733421.636378109
602319.474933147733511.835255548601523.561968744733549.960443333
#Sta/Elev= 30
7379.378178.74037867.117168.05668506.824171.67088629.243 167.6368742.202152.1371
9342.375153.38999601.482142.65099663.399169.37129724.951175.38079847.763172.9095
9888.518145.724810122.33145.603410132.47150.818410142.61 173.72810162.89174.0805
 10264.3174.031310365.69152.318710497.09152.870110567.87182.551210588.06183.8249
10628.38183.464510698.95160.830610819.91176.180110930.48157.305211101.27157.6765
11201.57172.212911321.87170.759111622.19187.129411752.25208.4553 11863.7236.9872
#Mann= 3 , 0 , 0
7379.378    0.04       07379.378    0.04       0 11863.7    0.04       0
#XS Ineff= 2 , 0
       09758.652        10245.34       0
Bank Sta=7379.378,11863.7
Exp/Cntr=0.3,0.1

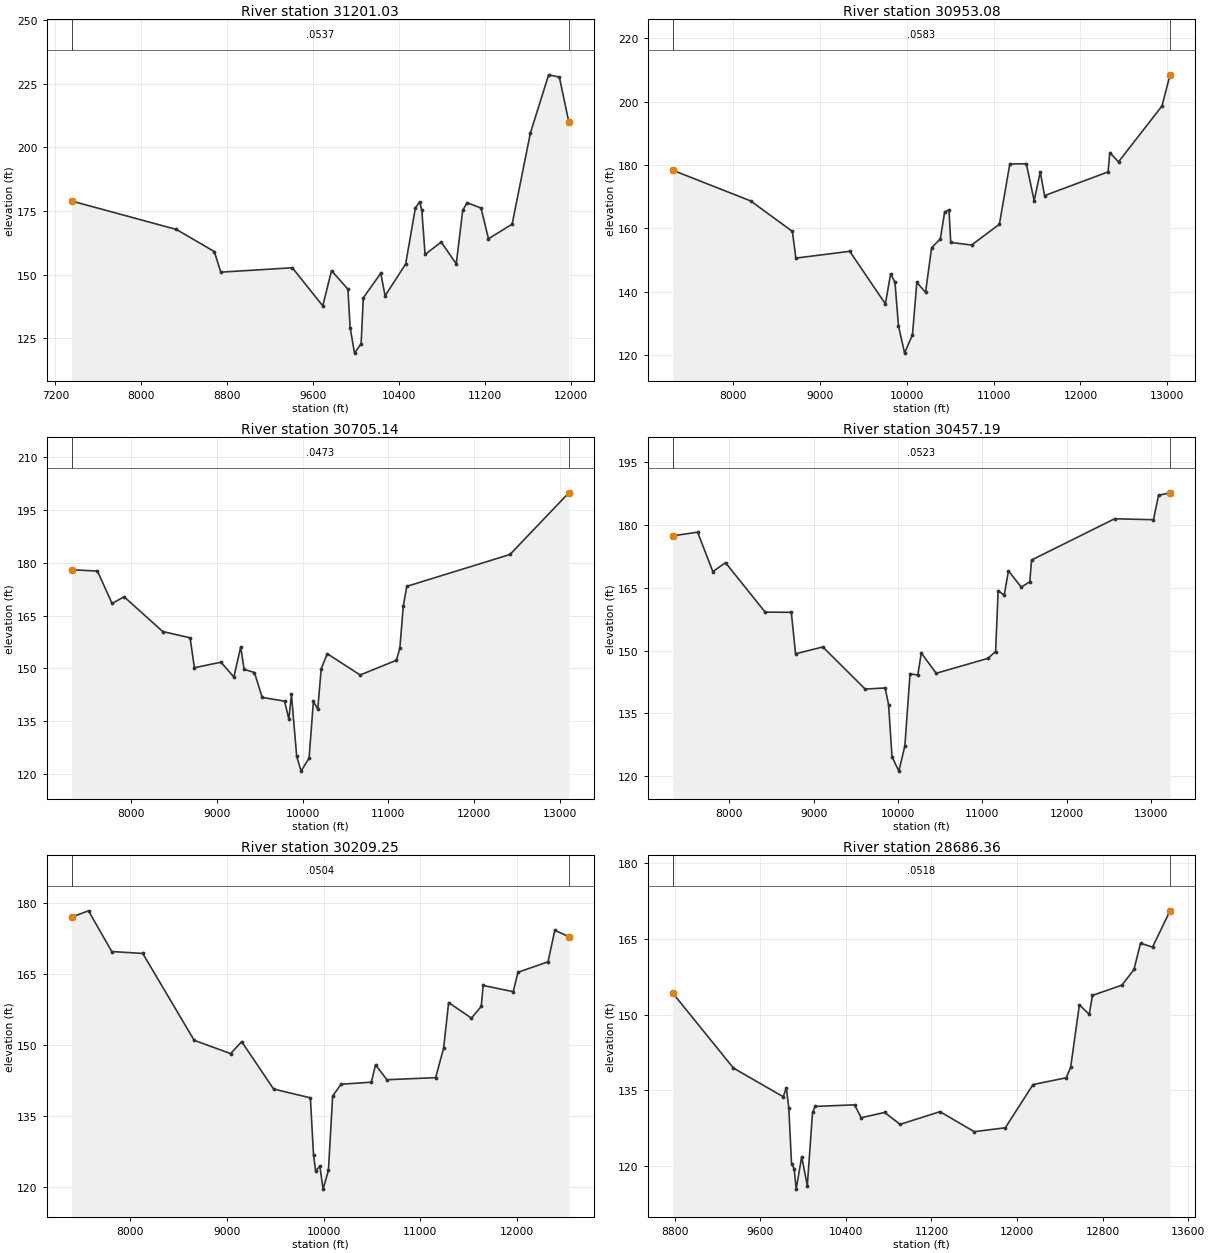
Type RM Length L Ch R = 1 ,31201.03,247.946600,247.946600,247.946600
XS GIS Cut Line= 6
 605953.93241085 732748.40732991603964.731713086733007.895050585
 603118.43428731733161.094618291602936.275880009733185.638160393
602197.227419078733233.698224172601356.965753883733234.343899906
#Sta/Elev= 30
7350.052178.96088326.976167.76868679.714159.09178740.183150.99739406.427152.7148
9689.921137.74879771.235151.59189924.253144.30079944.719129.18249985.651119.1763
10047.02 122.85110067.47140.923410229.98150.555910270.34141.710110461.78  154.18
 10552.2176.182310592.38178.669610612.47175.242810642.55157.966910792.87162.7898
10933.09154.275110993.14175.257111033.17178.291711163.25176.188711233.26164.1276
11453.29169.8359 11623.3205.6509 11793.3228.533311893.32 227.65811981.37209.9908
#Mann= 3 , 0 , 0
7350.052  0.0537       07350.052  0.0537       011981.37  0.0537       0
#XS Ineff= 2 , 0
       09787.622        10196.46       0
Bank Sta=7350.052,11981.37
Exp/Cntr=0.3,0.1

Type RM Length L Ch R = 1 ,30953.08,247.946600,247.946600,247.946600
XS GIS Cut Line= 6
605966.679191962732691.724835165 604903.98170197732799.525323182
 603552.94052577732852.576341927602951.945520639 732903.68947196
602216.673486143732895.764945492600252.414384186732802.726766437
#Sta/Elev= 30
7305.893178.35098202.581168.67028683.705159.03128723.764150.60419344.072152.7564
9754.401136.13169814.572145.67079864.715142.99899904.836 129.2819975.387120.5994
10066.13 126.41910116.39142.954110216.66139.796710286.72153.887910386.77156.6667
10436.78165.187910486.79165.865710506.79155.5589 10746.8154.734611066.92161.2827
11187.04 180.32111377.21180.396411467.29168.715111537.36177.818711587.42170.3428
12318.36177.829612338.38183.934612438.51180.995312939.05198.641213031.72208.4788
#Mann= 3 , 0 , 0
7305.893  0.0583       07305.893  0.0583       013031.72  0.0583       0
#XS Ineff= 2 , 0
       09749.978        10155.49       0
Bank Sta=7305.893,13031.72
Exp/Cntr=0.3,0.1

Type RM Length L Ch R = 1 ,30705.14,247.946600,247.946600,247.946600
XS GIS Cut Line= 6
605975.978496493732650.372608627604902.823034644732740.116884857
604137.386846066732727.220418304603438.510168761732664.843635455
601678.860253751732410.252431467  600198.8945494732303.690469265
#Sta/Elev= 30
7300.267177.97427603.075177.6172 7773.92168.41347914.378170.31688365.284160.4671
8685.352158.68368735.354150.19779045.592151.77419195.907 147.5799276.144156.0652
9316.263149.7513 9436.62148.83959526.902141.79179788.165140.72699838.574135.6628
9868.958142.6124  9929.9 125.1189981.355120.883210074.37124.570410125.35140.6404
10176.06138.479610216.56149.944810287.36154.177410670.89148.148311094.54152.3102
11134.85155.772611175.15167.640111215.46 173.26812421.23182.309313108.38199.7902
#Mann= 3 , 0 , 0
7300.267  0.0473       07300.267  0.0473       013108.38  0.0473       0
#XS Ineff= 2 , 0
       09759.101         10214.1       0
Bank Sta=7300.267,13108.38
Exp/Cntr=0.3,0.1

Type RM Length L Ch R = 1 ,30457.19,247.946500,247.946500,247.946500
XS GIS Cut Line= 6
605988.870122926732593.046014478605077.267775536732655.743316606
604460.328160286732627.062881216601837.495038599732075.717592731
601128.429862797 731988.22083357600158.813171595731929.958702967
#Sta/Elev= 30
 7328.33177.41857623.622178.29617804.171168.86887954.467171.00518424.678159.1824
8735.137159.12688785.376149.21329108.794150.85119611.689140.77259848.085141.0471
 9888.96137.08099929.643124.599410010.95121.157810082.16127.195310143.41144.3971
10235.77144.154510276.88149.4151 10453.5144.556211066.79148.112211158.45 149.745
11189.01164.3345 11260.3163.201511311.12169.045211463.29165.157411564.57166.4444
11584.79 171.63412570.81181.498813031.57181.275213091.61187.112113227.89187.7011
#Mann= 3 , 0 , 0
 7328.33  0.0523       0 7328.33  0.0523       013227.89  0.0523       0
#XS Ineff= 2 , 0
       09725.816        10272.67       0
Bank Sta=7328.33,13227.89
Exp/Cntr=0.3,0.1

Type RM Length L Ch R = 1 ,30209.25,1522.881100,1522.881100,1522.881100
XS GIS Cut Line= 6
605939.785761833732559.921089336605081.101253629732598.547520891
604477.344072998732540.859589666602164.577139974731715.883841261
601892.816451252731658.995914131600960.170907438731677.468872175
#Sta/Elev= 30
7395.691 176.9727571.079  178.297811.589 169.6998131.749169.29198662.847150.9535
  9039.6148.15059153.841150.6741  9483.7140.66779863.449138.81389896.023126.6837
9917.739123.41539961.742 124.3629994.767119.540810049.69123.479410093.59139.1846
10180.47141.682210493.54142.118110536.55145.802410653.94142.634711157.76143.0742
11240.39149.339211291.88158.9222 11527.3155.6447 11628.7158.098411648.71162.5397
11958.77161.222112008.78165.321612318.84 167.52812388.85174.186412533.71172.8491
#Mann= 3 , 0 , 0
7395.691  0.0504       07395.691  0.0504       012533.71  0.0504       0
#XS Ineff= 2 , 0
       0 9690.42        10200.68       0
Bank Sta=7395.691,12533.71
Exp/Cntr=0.3,0.1

Type RM Length L Ch R = 1 ,28686.36,148.643100,148.643100,148.643100
XS GIS Cut Line= 6
 605281.97921443731618.558292061604657.949096978731371.195002243
604460.616562307731128.104198635603825.720581084730676.241293117
601952.380966812 731175.79852356601034.684873432731360.784516826
#Sta/Elev= 30
8782.903154.24689349.774139.41179815.618133.72029844.037135.50739867.355131.5454
9893.133120.48019917.681119.46819936.339115.43159988.076121.854810040.42116.1138
10089.52130.657910114.07131.808210482.29132.120310543.66129.565910762.78130.6209
10907.68128.253911280.26130.768511601.09126.805311890.87127.581712149.61136.1306
12460.09137.481212501.38139.554712582.99151.9194 12674.8150.048312705.41153.7919
12980.84155.816413093.05158.916213154.26164.121113266.47163.352513430.01170.5305
#Mann= 3 , 0 , 0
8782.903  0.0518       08782.903  0.0518       013430.01  0.0518       0
#XS Ineff= 2 , 0
       09804.186        10140.74       0
Bank Sta=8782.903,13430.01
Exp/Cntr=0.3,0.1

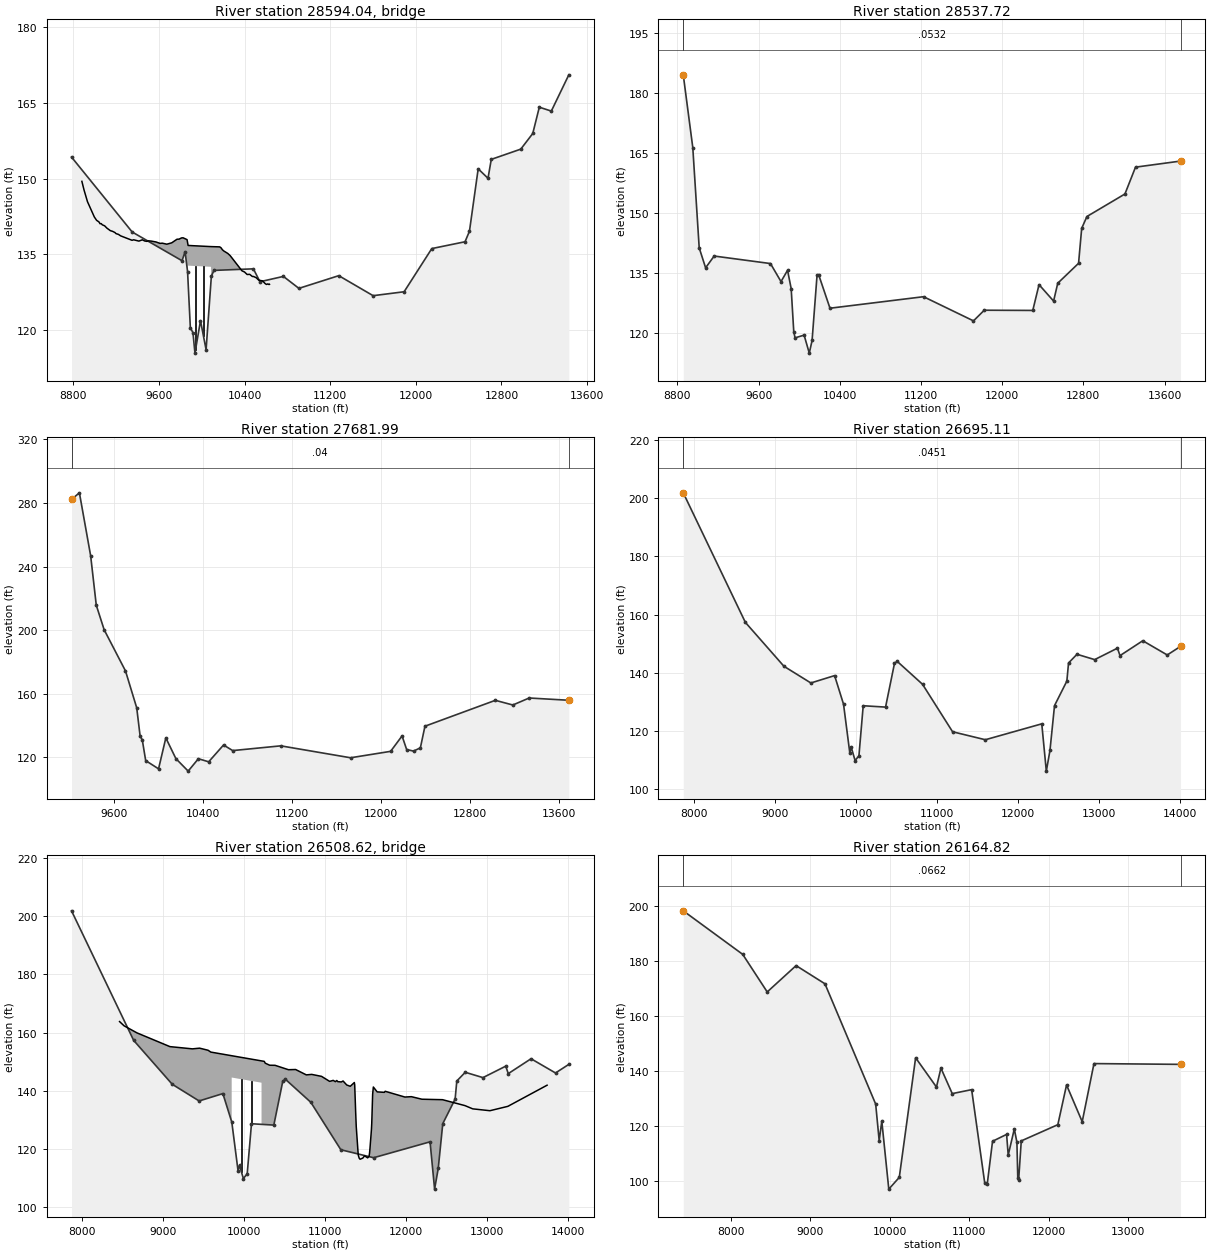
Type RM Length L Ch R = 3 ,28594.04,,,
BEGIN DESCRIPTION:
END DESCRIPTION:
Bridge Culvert--1,0,-1,-1, 0
Deck Dist Width WeirC Skew NumUp NumDn MinLoCord MaxHiCord MaxSubmerge Is_Ogee
48.321550,52.000000,2.6,0, 60, 60, , , 0.95, 0, 0,0,,
 8879.62 8899.74 8931.80 8995.92 9017.29 9038.66 9049.35 9060.03 9070.72 9092.09
 9113.46 9145.52 9166.89 9188.27 9198.95 9221.29 9241.70 9348.51 9363.59 9412.53
 9444.54 9465.88 9487.22 9498.96 9528.31 9572.34 9610.03 9631.04 9673.24 9719.05
 9768.36 9787.77 9810.68 9824.87 9862.55 9869.63 9869.63 9872.2010086.6310086.63
10167.4610180.1710192.8710205.5810243.0610265.9010375.6110399.7110423.8110447.91
10472.0210484.0710508.1710532.2710568.4210592.5210604.5710616.6210628.6710632.77
  149.44  147.73  145.42  142.39  141.72  141.42  141.05  141.08  140.83  140.64
  140.18  139.68  139.54  139.31  139.09  138.94  138.65  137.77  137.87  137.61
  137.87  137.64  137.56  137.67  137.61  137.44  137.16  137.20  137.00  137.27
  137.98  138.00  138.24  138.27  137.90  137.06  137.06  136.75  136.52  136.52
  136.47  136.28  135.90  135.66  135.17  134.72  131.73  131.49  131.00  131.03
  130.61  130.60  130.37  129.88  129.73  129.19  129.03  129.13  129.01  129.06
 -850.56 -852.27 -854.58 -857.61 -858.28 -858.58 -858.95 -858.92 -859.17 -859.36
 -859.82 -860.32 -860.46 -860.69 -860.91 -861.06 -861.35 -862.23 -862.13 -862.39
 -862.13 -862.36 -862.44 -862.33 -862.39 -862.56 -862.84 -862.80 -863.00 -862.73
 -862.02 -862.00 -861.76 -861.73 -862.10 -862.94  133.06  132.75  132.52 -863.48
 -863.53 -863.72 -864.10 -864.34 -864.83 -865.28 -868.27 -868.51 -869.00 -868.97
 -869.39 -869.40 -869.63 -870.12 -870.27 -870.81 -870.97 -870.87 -870.99 -870.94
 8879.62 8899.74 8931.80 8995.92 9017.29 9038.66 9049.35 9060.03 9070.72 9092.09
 9113.46 9145.52 9166.89 9198.95 9221.29 9241.70 9348.51 9363.59 9412.53 9444.54
 9465.88 9487.22 9498.96 9528.31 9572.34 9610.03 9631.04 9673.24 9719.05 9768.36
 9787.77 9810.68 9824.87 9862.55 9872.20 9930.09 9930.0910147.0910147.0910167.46
10180.1710192.8710205.5810255.1110291.2610301.7410375.6110399.7110423.8110447.91
10472.0210484.0710508.1710532.2710568.4210592.5210604.5710616.6210628.6710632.77
  149.44  147.73  145.42  142.39  141.72  141.42  141.05  141.08  140.83  140.64
  140.18  139.68  139.54  139.09  138.94  138.65  137.77  137.87  137.61  137.87
  137.64  137.56  137.67  137.61  137.44  137.16  137.20  137.00  137.27  137.98
  138.00  138.24  138.27  137.90  136.75  136.69  136.69  136.45  136.45  136.47
  136.28  135.90  135.66  134.95  133.98  133.80  131.73  131.49  131.00  131.03
  130.61  130.60  130.37  129.88  129.73  129.19  129.03  129.13  129.01  129.06
 -850.56 -852.27 -854.58 -857.61 -858.28 -858.58 -858.95 -858.92 -859.17 -859.36
 -859.82 -860.32 -860.46 -860.91 -861.06 -861.35 -862.23 -862.13 -862.39 -862.13
 -862.36 -862.44 -862.33 -862.39 -862.56 -862.84 -862.80 -863.00 -862.73 -862.02
 -862.00 -861.76 -861.73 -862.10 -863.25 -863.31  132.69  132.45 -863.55 -863.53
 -863.72 -864.10 -864.34 -865.05 -866.02 -866.20 -868.27 -868.51 -869.00 -868.97
 -869.39 -869.40 -869.63 -870.12 -870.27 -870.81 -870.97 -870.87 -870.99 -870.94
Pier Skew, UpSta & Num, DnSta & Num=  ,9941.30, 2 ,10001.75, 2 , 0 , 0 , 0 ,,
    4.00    4.00
 -863.32  136.68
    4.00    4.00
 -863.39  136.61
Pier Skew, UpSta & Num, DnSta & Num=  ,10014.96, 2 ,10075.42, 2 , 0 , 0 , 0 ,,
    4.00    4.00
 -863.40  136.60
    4.00    4.00
 -863.47  136.53
BR Coef=-1 , 0 , 0 ,, 0 ,,,0.8,0,1,0,
WSPro=,,,, 1 ,,,, 0 ,,,, 0 ,,,,-1 ,-1 ,-1 , 0 , 0 , 0 , 0 , 0
BC Design=,, 0 ,, 0 ,,,,,,

Type RM Length L Ch R = 1 ,28537.72,855.736000,855.736000,855.736000
XS GIS Cut Line= 6
605305.336389571731426.972902432604700.206481308731241.732817352
 604619.56315878731078.835790589 603762.80296132730438.870273098
601760.703067303730892.898391157600848.399958491731155.871110424
#Sta/Elev= 30
8857.067184.60328950.975166.40629014.148141.30379077.321136.30789161.552139.2526
9716.606137.37349820.425132.85959884.903135.68299920.608131.12179946.108120.3412
9958.858118.781810048.11119.461710099.11114.957110126.69118.117510175.61134.4331
10191.17134.599910303.11126.195811225.13129.077211717.32123.028711823.39125.6955
12301.79125.642112363.31132.094912506.87127.986412547.88132.450612752.96137.4356
12783.72146.180512835.39149.148813210.04154.786713314.12161.496813758.08163.0195
#Mann= 3 , 0 , 0
8857.067  0.0532       08857.067  0.0532       013758.08  0.0532       0
#XS Ineff= 2 , 0
       09871.029        10205.46       0
Bank Sta=8857.067,13758.08
Exp/Cntr=0.3,0.1

Type RM Length L Ch R = 1 ,27681.99,986.874300,986.874300,986.874300
XS GIS Cut Line= 6
605054.930717736729949.160665914604417.963314086730047.265215382
604229.356283009730070.861585736603979.904945344730097.480129674
601578.588675112730692.579300061600705.581523716730975.795692682
#Sta/Elev= 30
9215.465282.2967 9286.32286.4453 9387.63246.83929438.226215.77989509.062200.3281
9701.303174.41699802.334151.21599832.643133.66159852.849130.89269883.107118.0154
    9999112.839410064.47132.306210154.99119.271310265.61111.398110357.47119.1945
10450.19117.254910584.13127.827310666.55 124.31611099.25127.3014 11727.7119.8012
12088.29123.840512191.32133.537512232.53124.991812294.34123.990612356.16126.0515
12397.37139.647513030.95155.931613188.64152.993313335.83157.396313692.66 155.965
#Mann= 3 , 0 , 0
9215.465    0.04       09215.465    0.04       013692.66    0.04       0
#XS Ineff= 2 , 0
       0                10100.66       0
Bank Sta=9215.465,13692.66
Exp/Cntr=0.3,0.1

Type RM Length L Ch R = 1 ,26695.11,530.290900,530.290900,530.290900
XS GIS Cut Line= 6
606061.500372414728423.987360186606057.081972718728452.075758249
605495.805141896728466.467471853603560.119661301729358.753715709
601825.918171227 730243.84410274 600417.24796792730649.370373425
#Sta/Elev= 30
 7871.52201.88518637.704157.33879113.556142.2402 9445.59136.50099738.335139.0331
9848.618129.20119925.816112.4658 9943.64114.40759991.074109.827810038.51111.4453
10091.24128.669510366.95128.201410477.23  143.2510510.31143.937810823.18136.0426
11193.68119.719711597.85116.979112293.94122.446612350.07106.184312394.98113.2805
12451.12128.708712603.29137.140812624.11143.371112728.17146.3645 12946.7 144.532
13227.66148.468513258.88145.901213539.84151.020213841.62146.127314005.78149.0868
#Mann= 3 , 0 , 0
 7871.52  0.0451       0 7871.52  0.0451       014005.78  0.0451       0
#XS Ineff= 2 , 0
       0                10275.64       0
Bank Sta=7871.52,14005.78
Exp/Cntr=0.3,0.1

Type RM Length L Ch R = 3 ,26508.62,,,
BEGIN DESCRIPTION:
END DESCRIPTION:
Bridge Culvert--1,0,-1,-1, 0
Deck Dist Width WeirC Skew NumUp NumDn MinLoCord MaxHiCord MaxSubmerge Is_Ogee
196.145450,138.000000,2.6,0, 60, 60, , , 0.95, 0, 0,0,,
 8464.13 8518.88 8679.10 9085.01 9362.73 9451.28 9555.75 9589.51 9847.26 9847.26
10215.2610215.2610248.9110261.1210316.1710382.2310547.3810635.4510767.7710834.11
10955.7111055.1411099.4311125.4911143.6511154.7111198.9311221.0411266.2111309.49
11360.0211364.7611375.8211383.4711406.9311408.9811420.0411431.0911464.2611486.37
11524.1911541.6511547.6411552.7011571.0911574.8111585.8711594.5511641.4511729.59
11740.6411983.8612063.6012193.9112448.1912724.9112820.2713032.1613253.8213737.53
  163.80  162.36  159.91  155.19  154.42  154.66  153.94  153.31  152.06  152.06
  150.28  150.28  150.12  149.49  148.79  148.76  147.25  147.32  145.47  145.64
  144.96  143.24  143.58  143.14  143.54  143.15  143.04  143.37  142.00  141.55
  142.84  142.01  133.09  127.75  118.42  117.84  116.82  116.46  116.85  117.63
  116.94  117.47  118.56  120.12  126.75  128.87  138.85  141.30  139.63  139.46
  139.83  137.85  137.98  137.10  136.94  134.90  133.79  133.15  134.65  141.92
 -836.20 -837.64 -840.09 -844.81 -845.58 -845.34 -846.06 -846.69 -847.94  144.56
  142.78 -849.72 -849.88 -850.51 -851.21 -851.24 -852.75 -852.68 -854.53 -854.36
 -855.04 -856.76 -856.42 -856.86 -856.46 -856.85 -856.96 -856.63 -858.00 -858.45
 -857.16 -857.99 -866.91 -872.25 -881.58 -882.16 -883.18 -883.54 -883.15 -882.37
 -883.06 -882.53 -881.44 -879.88 -873.25 -871.13 -861.15 -858.70 -860.37 -860.54
 -860.17 -862.15 -862.02 -862.90 -863.06 -865.10 -866.21 -866.85 -865.35 -858.08
 8464.13 8518.88 8679.10 9085.01 9362.73 9451.28 9555.75 9589.51 9827.67 9827.67
10195.6710195.6710248.9110261.1210316.1710382.2310547.3810635.4510767.7710834.11
10955.7111055.1411099.4311125.4911143.6511154.7111198.9311221.0411266.2111309.49
11360.0211364.7611375.8211383.4711406.9311408.9811420.0411431.0911464.2611486.37
11524.1911541.6511547.6411552.7011571.0911574.8111585.8711594.5511641.4511729.59
11740.6411983.8612063.6012193.9112448.1912724.9112820.2713032.1613253.8213737.53
  163.80  162.36  159.91  155.19  154.42  154.66  153.94  153.31  152.16  152.16
  150.38  150.38  150.12  149.49  148.79  148.76  147.25  147.32  145.47  145.64
  144.96  143.24  143.58  143.14  143.54  143.15  143.04  143.37  142.00  141.55
  142.84  142.01  133.09  127.75  118.42  117.84  116.82  116.46  116.85  117.63
  116.94  117.47  118.56  120.12  126.75  128.87  138.85  141.30  139.63  139.46
  139.83  137.85  137.98  137.10  136.94  134.90  133.79  133.15  134.65  141.92
 -836.20 -837.64 -840.09 -844.81 -845.58 -845.34 -846.06 -846.69 -847.84  144.66
  142.88 -849.62 -849.88 -850.51 -851.21 -851.24 -852.75 -852.68 -854.53 -854.36
 -855.04 -856.76 -856.42 -856.86 -856.46 -856.85 -856.96 -856.63 -858.00 -858.45
 -857.16 -857.99 -866.91 -872.25 -881.58 -882.16 -883.18 -883.54 -883.15 -882.37
 -883.06 -882.53 -881.44 -879.88 -873.25 -871.13 -861.15 -858.70 -860.37 -860.54
 -860.17 -862.15 -862.02 -862.90 -863.06 -865.10 -866.21 -866.85 -865.35 -858.08
Pier Skew, UpSta & Num, DnSta & Num=  ,9969.26, 2 ,9949.67, 2 , 0 , 0 , 0 ,,
    4.00    4.00
 -848.52  151.48
    4.00    4.00
 -848.43  151.57
Pier Skew, UpSta & Num, DnSta & Num=  ,10093.26, 2 ,10073.67, 2 , 0 , 0 , 0 ,,
    4.00    4.00
 -849.14  150.86
    4.00    4.00
 -849.04  150.96
BR Coef=-1 , 0 , 0 ,, 0 ,,,0.8,0,1,0,
WSPro=,,,, 1 ,,,, 0 ,,,, 0 ,,,,-1 ,-1 ,-1 , 0 , 0 , 0 , 0 , 0
BC Design=,, 0 ,, 0 ,,,,,,

Type RM Length L Ch R = 1 ,26164.82,650.418300,650.418300,650.418300
XS GIS Cut Line= 6
606055.720594404727745.909378246 603387.41909799728984.569161832
603027.626257777729171.661438778601214.270342857729984.793257773
 600343.57166937 730236.64824596600332.012747181730230.926007252
#Sta/Elev= 30
7399.742198.32138148.234182.48168456.618168.8077 8820.07178.39169183.523171.7727
 9821.96128.00659865.986114.71339899.006121.7996 9987.0697.0670710119.14101.3459
10324.71144.860710587.04134.201710643.39141.091110785.75131.818711030.01 133.264
 11194.499.3889911225.6798.7580811293.03114.478411470.08116.9776 11490.3109.4339
11567.02118.960611599.89114.118711610.85101.032811621.81 100.47811654.69114.6162
12114.98120.513612224.58134.956412421.85121.601612569.89142.742213659.76142.4583
#Mann= 3 , 0 , 0
7399.742  0.0662       07399.742  0.0662       013659.76  0.0662       0
#XS Ineff= 2 , 0
       0                10368.56       0
Bank Sta=7399.742,13659.76
Exp/Cntr=0.3,0.1

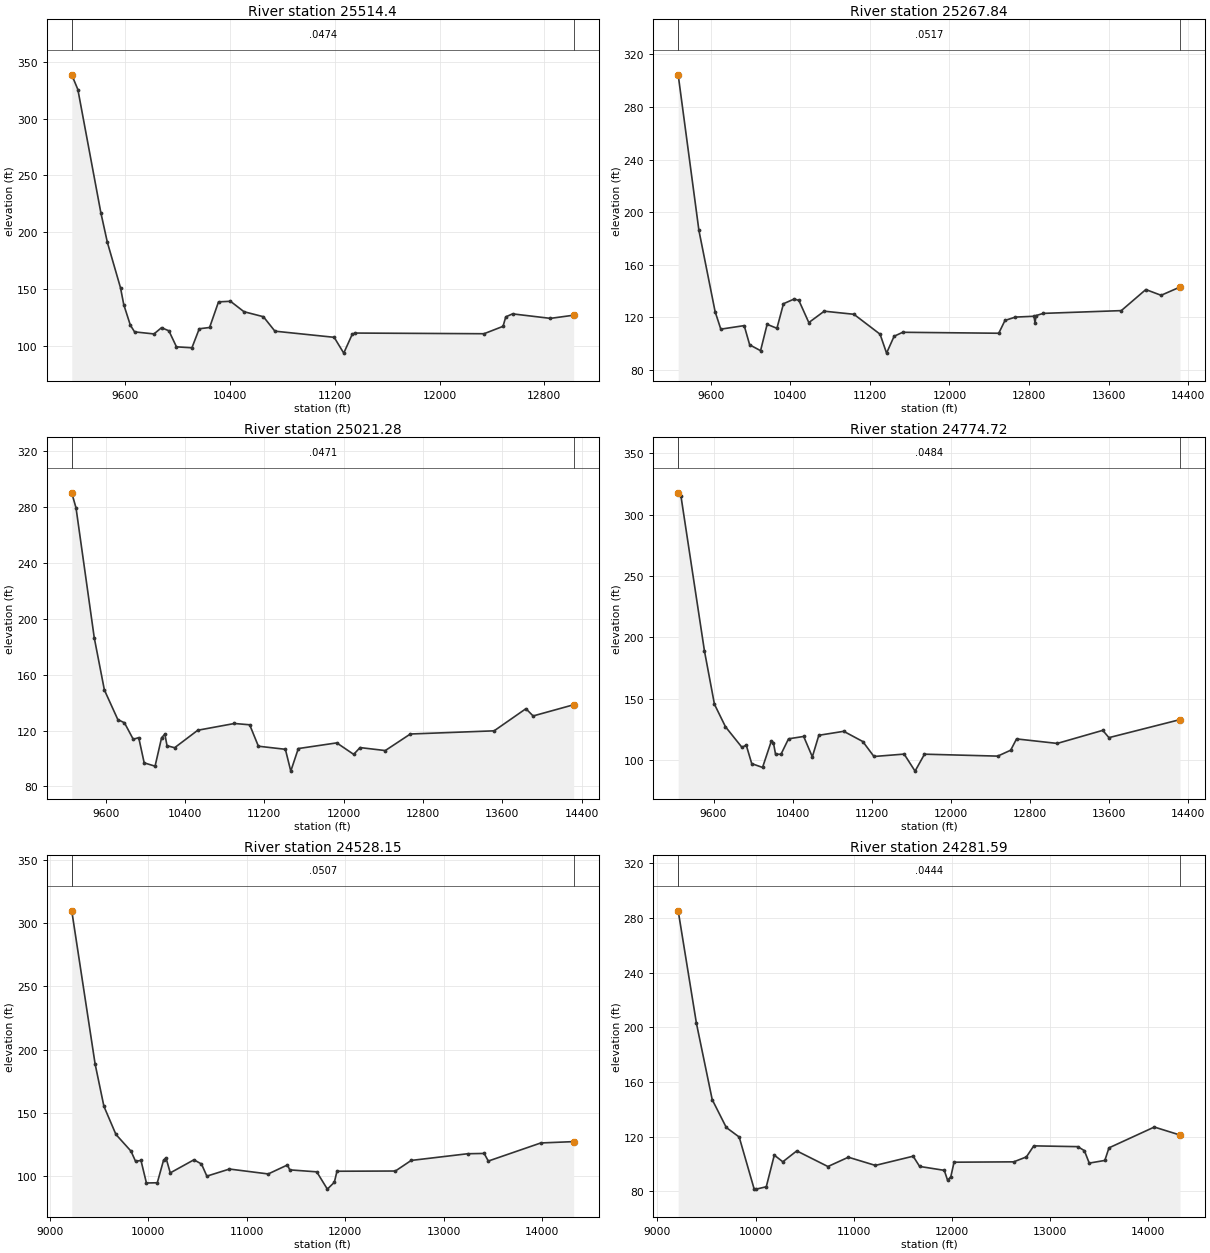
Type RM Length L Ch R = 1 , 25514.4,246.561700,246.561700,246.561700
XS GIS Cut Line= 6
603912.203706294727957.237718098603557.424749792728224.671949608
603359.846020909728352.919162795602163.627282787728963.513948253
601471.136124848729227.582789406600442.663798483729509.748596729
#Sta/Elev= 30
9191.859338.57429238.449325.64849413.769217.36719463.861191.09019564.044151.1865
9589.089 136.2939639.106118.29749671.546 112.3699819.596110.57079877.296116.0678
9933.546113.30259991.29799.2064710109.3898.3774610165.28 115.11110244.24116.2382
10312.39138.787610403.81 139.29810506.72130.1326 10655.1125.713510743.06112.9974
11195.32107.600211268.4993.6775911333.91110.425111355.56111.340912339.55110.7471
12484.78117.261212505.51125.581112557.33128.225612846.45124.2663 13023.7127.0455
#Mann= 3 , 0 , 0
9191.859  0.0474       09191.859  0.0474       0 13023.7  0.0474       0
#XS Ineff= 2 , 0
       0                10405.74       0
Bank Sta=9191.859,13023.7
Exp/Cntr=0.3,0.1

Type RM Length L Ch R = 1 ,25267.84,246.561600,246.561600,246.561600
XS GIS Cut Line= 6
 603780.33014825 727825.88727127603234.359678477728142.046756983
602023.039581358728704.801165745601490.853672534728921.371151596
600437.309241325729259.316986486599079.154374629729591.861243963
#Sta/Elev= 30
9271.923304.4382 9480.43 186.0549643.387124.24199700.632110.94319935.737  113.64
9990.738 99.028110100.43 94.567510166.23114.609310264.93111.598410330.76130.2932
10439.56133.923410485.91132.758810585.64115.952510740.79124.616611039.13122.2616
11302.25107.095811367.46 92.706911443.53105.554611530.21108.565212495.62107.8348
12558.35 117.57812662.86120.127212850.13120.746612860.53115.665312870.93121.2891
12943.66122.945713728.28125.050413974.75141.0757 14128.5136.7102   14319143.0016
#Mann= 3 , 0 , 0
9271.923  0.0517       09271.923  0.0517       0   14319  0.0517       0
#XS Ineff= 2 , 0
       0                10416.88       0
Bank Sta=9271.923,14319
Exp/Cntr=0.3,0.1

Type RM Length L Ch R = 1 ,25021.28,246.561700,246.561700,246.561700
XS GIS Cut Line= 6
603702.114854813727615.227414235603066.561441571727947.777720079
602005.772066385728425.769947693601193.387459815728759.861432537
600306.622917652729059.500458404598988.133452684729412.985146865
#Sta/Elev= 30
9258.449290.36849301.579279.50979485.593186.42159587.662 149.0899722.904127.9438
9789.894 125.6149878.477113.81639933.683114.9931 9988.8396.9306610098.5394.54486
10164.34114.907910197.24117.506310219.18109.193910295.95107.770310529.09120.2858
10899.19 125.12711052.74 124.19411140.47 108.85111412.74106.636111467.1990.99895
11543.17107.165711930.76111.231812101.63103.001912165.53107.872412420.04105.7314
12672.99117.589613517.92119.871213838.62135.723813910.96130.521414319.58138.5468
#Mann= 3 , 0 , 0
9258.449  0.0471       09258.449  0.0471       014319.58  0.0471       0
#XS Ineff= 2 , 0
       0                10423.94       0
Bank Sta=9258.449,14319.58
Exp/Cntr=0.3,0.1

Type RM Length L Ch R = 1 ,24774.72,246.561600,246.561600,246.561600
XS GIS Cut Line= 6
603619.968099028  727393.9788187602941.896806687  727733.6314338
601092.138342679 728538.94896315600466.271441907728771.829554334
599935.079411119728947.145053923598900.716502398729238.776829049
#Sta/Elev= 30
9242.427317.65789270.883314.78499508.471188.82329609.376145.56849721.099127.2221
9887.264110.53679931.396112.25539986.56197.2339110096.1594.1414710183.75115.3103
10205.65 114.38110227.55104.9354 10282.3104.813710358.95117.428310512.25119.3581
10599.85102.762110665.55120.3062 10917.4123.545711110.18115.244711223.36103.0404
11528.82105.001611639.2891.1333911734.75 104.92912475.42103.350212606.67108.1493
12666.14117.358513077.86113.685613538.48124.326513600.98118.386714320.64133.0739
#Mann= 3 , 0 , 0
9242.427  0.0484       09242.427  0.0484       014320.64  0.0484       0
#XS Ineff= 2 , 0
       0                 10418.3       0
Bank Sta=9242.427,14320.64
Exp/Cntr=0.3,0.1

Type RM Length L Ch R = 1 ,24528.15,246.561600,246.561600,246.561600
XS GIS Cut Line= 6
603536.474473357727169.102653518602668.178080559727588.404056907
601313.782232106728188.119059935600804.904308051728401.783769295
599844.994706959728756.795853987598813.994267851729068.099430546
#Sta/Elev= 30
9222.864309.95819460.334188.48119549.547155.03899671.637132.74719824.671119.4965
9870.757111.47739926.069 112.126 9981.3894.2634110091.7594.4511710154.97112.1935
10179.72114.2644 10223.5102.2823 10464.1112.653110540.66109.311410595.3499.70365
10825.01105.324611218.72101.441411413.75108.551911437.45104.670611711.57  103.11
11819.2789.4071311890.38 94.850311917.07103.588112510.41103.757812670.95112.1419
13243.98117.447213412.23117.693113454.29111.653813987.55125.996914321.09127.0558
#Mann= 3 , 0 , 0
9222.864  0.0507       09222.864  0.0507       014321.09  0.0507       0
#XS Ineff= 2 , 0
       0                10382.16       0
Bank Sta=9222.864,14321.09
Exp/Cntr=0.3,0.1

Type RM Length L Ch R = 1 ,24281.59,246.561700,246.561700,246.561700
XS GIS Cut Line= 6
603455.678325325726951.491694734602970.038905948727186.181571335
602251.318662554727492.018778235 600507.59349668728271.278176308
599765.565599084728558.803862154598733.615521193 728891.24443607
#Sta/Elev= 30
9211.744285.22289397.783202.84999558.221147.11669701.673126.71599833.003 119.748
9984.91281.8284710006.5281.6303110108.8283.3638310190.45106.493910277.41101.6321
10419.21109.595310736.5298.16451 10944.8104.979811219.6798.9834511604.48105.7087
11670.4498.2321111921.4895.3734411955.2388.1162211988.0990.6952712020.94101.3301
12628.64101.588512757.76105.198412832.88113.281213281.12112.712413348.14109.7754
13397.61100.675213556.42102.6166 13598.5111.815714060.24127.051114322.53121.1878
#Mann= 3 , 0 , 0
9211.744  0.0444       09211.744  0.0444       014322.53  0.0444       0
#XS Ineff= 2 , 0
       0                10352.83       0
Bank Sta=9211.744,14322.53
Exp/Cntr=0.3,0.1

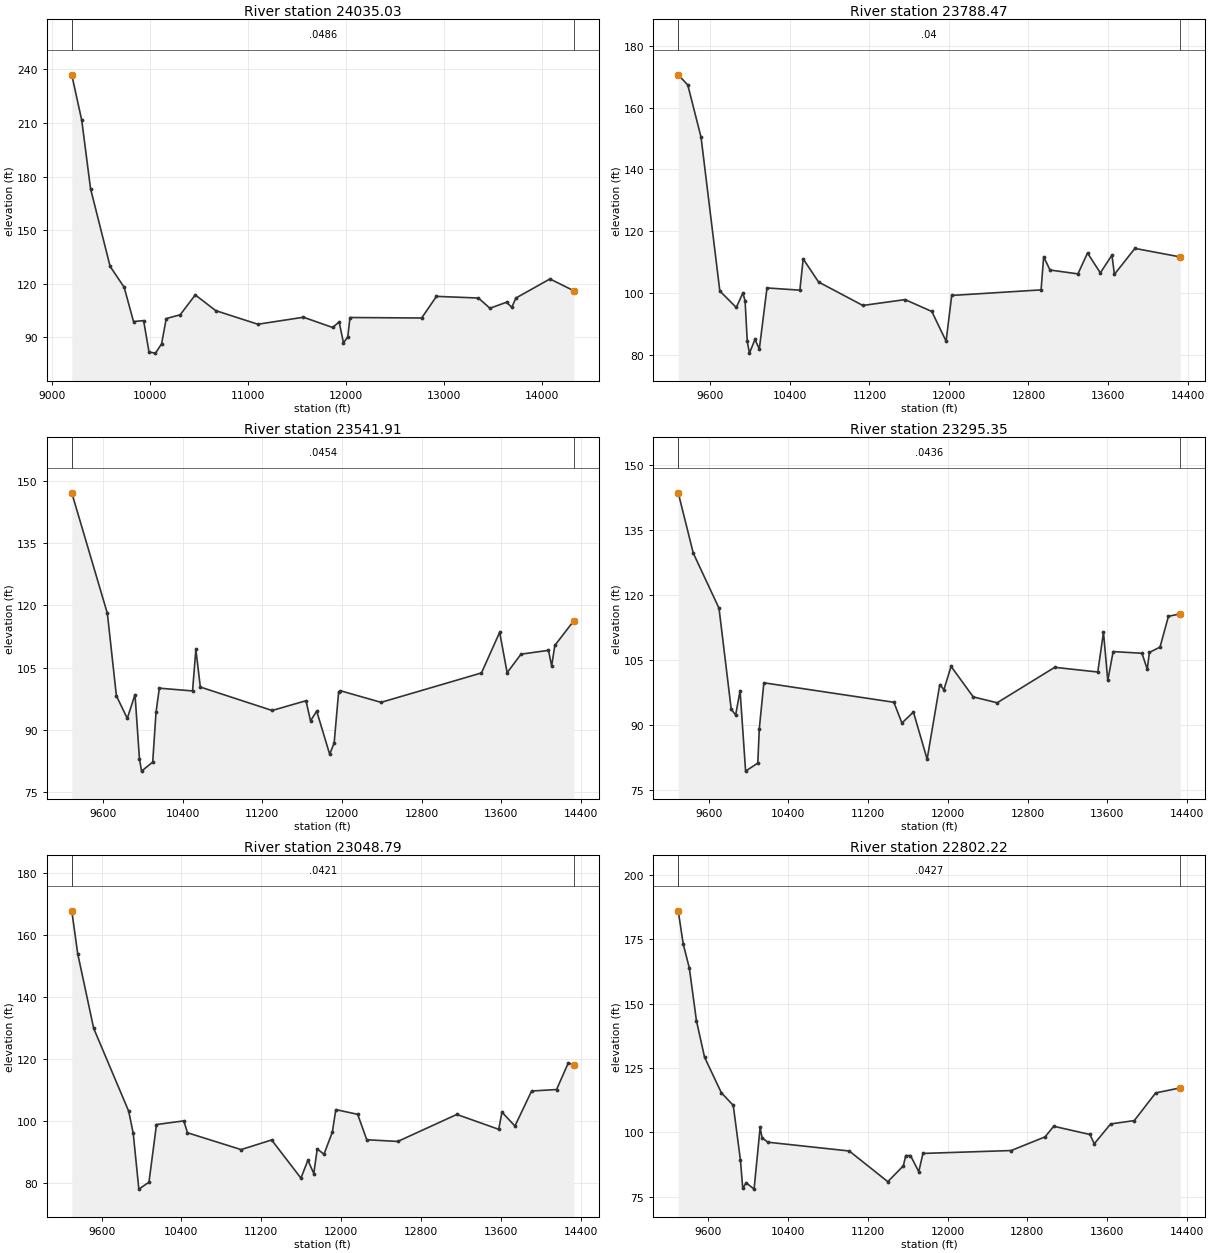
Type RM Length L Ch R = 1 ,24035.03,246.561600,246.561600,246.561600
XS GIS Cut Line= 6
603366.400650471726711.037157059602942.014642477 726918.54171215
600812.514248401 727909.34880124600205.472000182728178.523752496
599409.813663661728488.398590192598662.036593169728733.842976525
#Sta/Elev= 30
9197.418236.89199299.619211.36349389.071173.24229588.909129.77549732.691118.0479
9827.70898.92093 9931.13 99.44239986.25281.8271910052.3181.2489910114.5386.46087
10162.05 100.57810304.71102.708410458.34113.816710667.13105.020111097.8397.40425
11562.74101.323811861.2195.5831211927.49 98.726311971.68 86.973812015.8790.40179
12037.87  101.1712769.72100.892412921.13112.997313349.93112.062413467.17106.3358
13636.96109.728813689.86106.853613732.18112.062414079.77122.743214323.77116.1045
#Mann= 3 , 0 , 0
9197.418  0.0486       09197.418  0.0486       014323.77  0.0486       0
#XS Ineff= 2 , 0
       0                10324.26       0
Bank Sta=9197.418,14323.77
Exp/Cntr=0.3,0.1

Type RM Length L Ch R = 1 ,23788.47,246.561600,246.561600,246.561600
XS GIS Cut Line= 6
603190.617348731726520.383525565601833.590668947727164.069063097
600542.898440003727803.601826176600128.625768036727994.832544431
599349.313858956728315.007859424598584.194688678728578.241874412
#Sta/Elev= 30
9276.853170.60319372.759167.3325 9506.45 150.4199695.172100.71899860.93295.38215
9927.132100.08089949.19997.579399971.26584.392139993.33280.6283310048.4385.04334
 10092.581.9735810169.63101.703410500.49100.983510533.71111.082910688.73103.6176
11133.9896.0405811559.0897.9308411827.5894.1011411971.5184.4911312027.8899.27579
12926.89101.074912952.74111.774613016.96 107.49813297.56106.250913394.13113.0021
13522.85106.5761 13639.9112.3033 13664.5106.092213870.82114.4911 14327.5111.7249
#Mann= 3 , 0 , 0
9276.853    0.04       09276.853    0.04       0 14327.5    0.04       0
#XS Ineff= 2 , 0
       0                10310.59       0
Bank Sta=9276.853,14327.5
Exp/Cntr=0.3,0.1

Type RM Length L Ch R = 1 ,23541.91,246.561600,246.561600,246.561600
XS GIS Cut Line= 6
603074.347341567726295.167606175601797.880529106726920.337265417
600801.478984535727446.978456825600059.929277927727817.460161492
599299.414492399728145.854582742598513.657298535728428.039625511
#Sta/Elev= 30
9286.772147.12139644.141118.09949734.76598.263199844.06692.824729921.81598.56524
9966.24383.115649987.52680.1271310099.3782.3048710132.6494.2780610165.91100.0967
10499.2799.4343810532.76109.421710577.41100.371811298.6794.7235311638.5897.07832
 11683.992.22312 11745.994.5715511876.2384.1925811921.2386.9130911966.2399.21265
11983.6799.4771112392.3196.6855113400.26103.764213583.06113.558613657.99 103.818
13797.14108.282514073.12109.204514104.94105.439114136.77110.387314327.74116.3362
#Mann= 3 , 0 , 0
9286.772  0.0454       09286.772  0.0454       014327.74  0.0454       0
#XS Ineff= 2 , 0
       0                10298.43       0
Bank Sta=9286.772,14327.74
Exp/Cntr=0.3,0.1

Type RM Length L Ch R = 1 ,23295.35,246.561700,246.561700,246.561700
XS GIS Cut Line= 6
602958.221382469726070.230709031601805.054947615726650.005064726
600563.627148181727349.960665375600000.920553058727642.794364363
599262.841190189727977.147676945598442.290060073728283.810357362
#Sta/Elev= 30
9294.582143.55319445.379129.62519703.661116.89149826.06893.569229870.51392.20158
9914.95797.836669970.51379.2511610092.7881.1134310107.8789.0718410153.6599.65879
 11458.195.1613111538.7890.3627611654.0292.9089111791.5182.0025711918.3199.25067
11959.3798.0532812031.78103.451212254.2296.4058112494.08 95.044813071.41103.2354
13503.49102.152613560.79111.314413603.87100.192413657.72106.873213946.78106.4855
14000.11102.790614021.44106.687414127.94107.907514212.47115.019214331.57115.5997
#Mann= 3 , 0 , 0
9294.582  0.0436       09294.582  0.0436       014331.57  0.0436       0
#XS Ineff= 2 , 0
       0                10284.16       0
Bank Sta=9294.582,14331.57
Exp/Cntr=0.3,0.1

Type RM Length L Ch R = 1 ,23048.79,246.561600,246.561600,246.561600
XS GIS Cut Line= 6
 602836.57150194725834.593932509601794.383299738726394.294136792
600653.358185053727091.553741693599959.343712002727477.167631209
599246.188044488727815.251688465598381.775512725728150.704210013
#Sta/Elev= 30
9300.901167.76749360.158154.00799520.607129.90369871.771103.17599916.79396.08353
9973.07178.1116410074.4580.3462210149.8798.92349 10423.4100.095710460.4496.27115
10997.6490.84873 11303.793.9487611597.3681.6567511667.45 87.446211725.8783.14522
11760.9191.0743111828.0789.3529411912.0496.4652411946.84103.728912165.74 102.211
12257.1994.0178512567.7993.4756413159.37102.172413579.3897.37778 13611.9102.9126
13741.6798.44187 13908.9109.7252 14158.8110.193514275.59118.7043 14332.1118.2521
#Mann= 3 , 0 , 0
9300.901  0.0421       09300.901  0.0421       0 14332.1  0.0421       0
#XS Ineff= 2 , 0
       0                10285.87       0
Bank Sta=9300.901,14332.1
Exp/Cntr=0.3,0.1

Type RM Length L Ch R = 1 ,22802.22,246.561600,246.561600,246.561600
XS GIS Cut Line= 6
602709.483396739725588.423272163601869.677742779726083.651748836
600729.255627722 726848.12701413600123.379751444727214.718428254
599247.140095711 727659.48344025598323.025149167728030.547734886
#Sta/Elev= 30
9298.448186.02129348.654173.11069409.813163.78679480.893 143.3819562.544129.1545
9730.711115.37419850.319110.46539922.67989.073149945.39578.241029979.46980.41249
10059.0777.9419510119.74101.876210139.3197.8924610197.6396.1633111013.7492.74765
11400.3880.83683 11556.387.0013411580.1690.9701311627.8990.9778311710.9684.72389
11752.68 91.805512637.92 92.930412977.5998.2400313064.24102.357613427.5199.15785
13471.1695.5555313634.84103.255313872.22104.557114086.55 115.29814333.97117.2668
#Mann= 3 , 0 , 0
9298.448  0.0427       09298.448  0.0427       014333.97  0.0427       0
#XS Ineff= 2 , 0
       0                10299.35       0
Bank Sta=9298.448,14333.97
Exp/Cntr=0.3,0.1