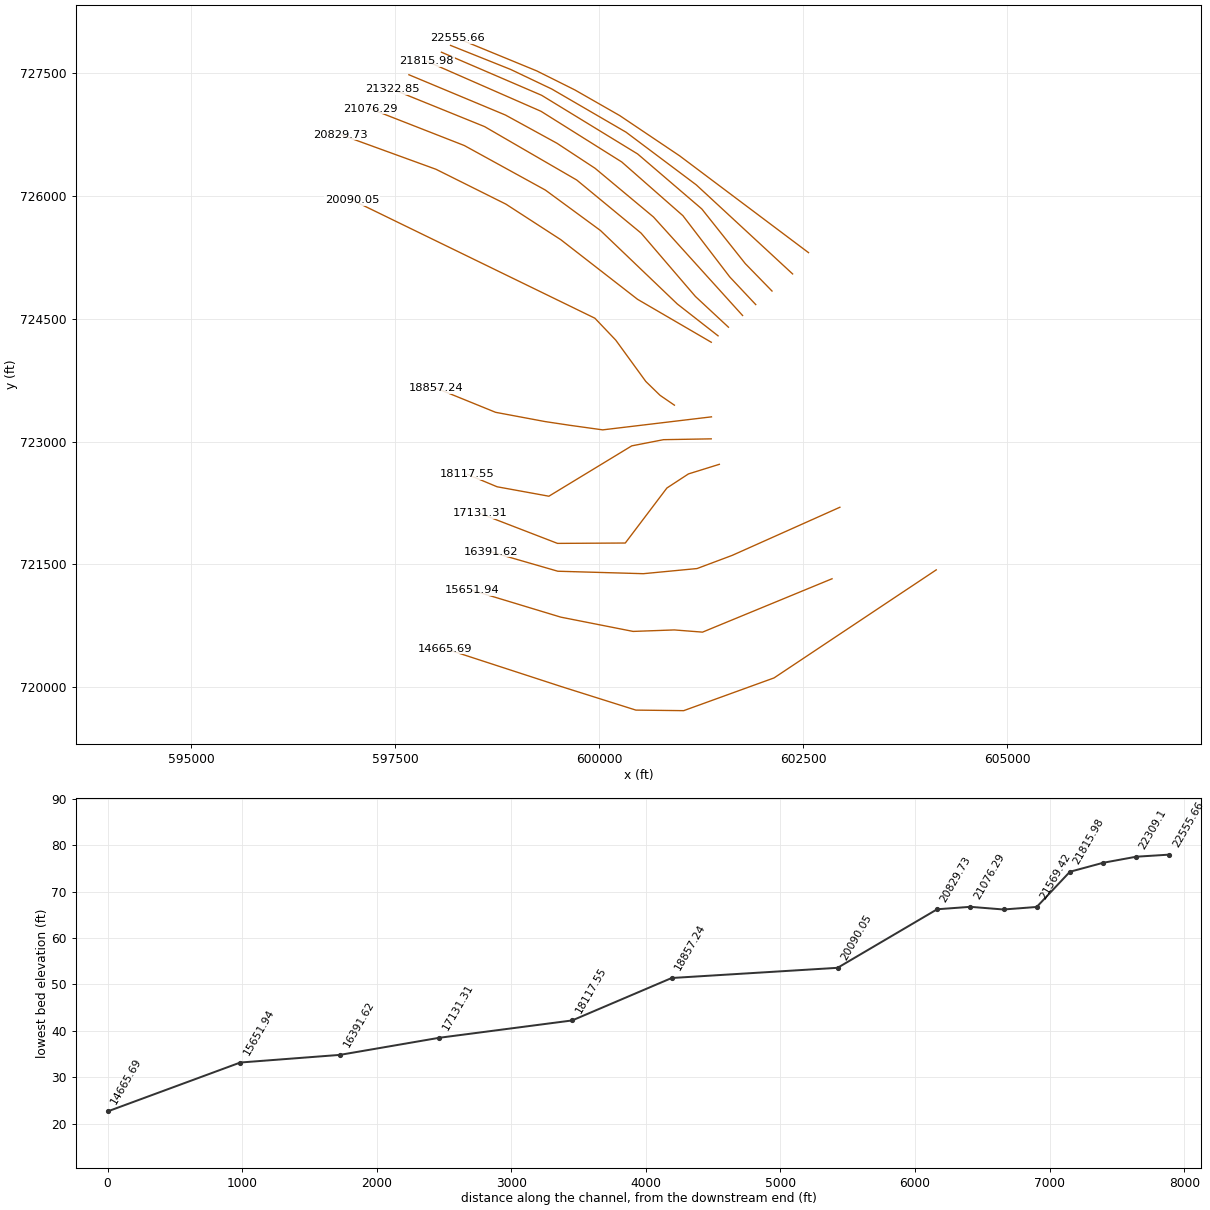
HEC-RAS study 2027_ras.prj: 2027

--- 2027_ras.g01 (geometry) --- (continued)

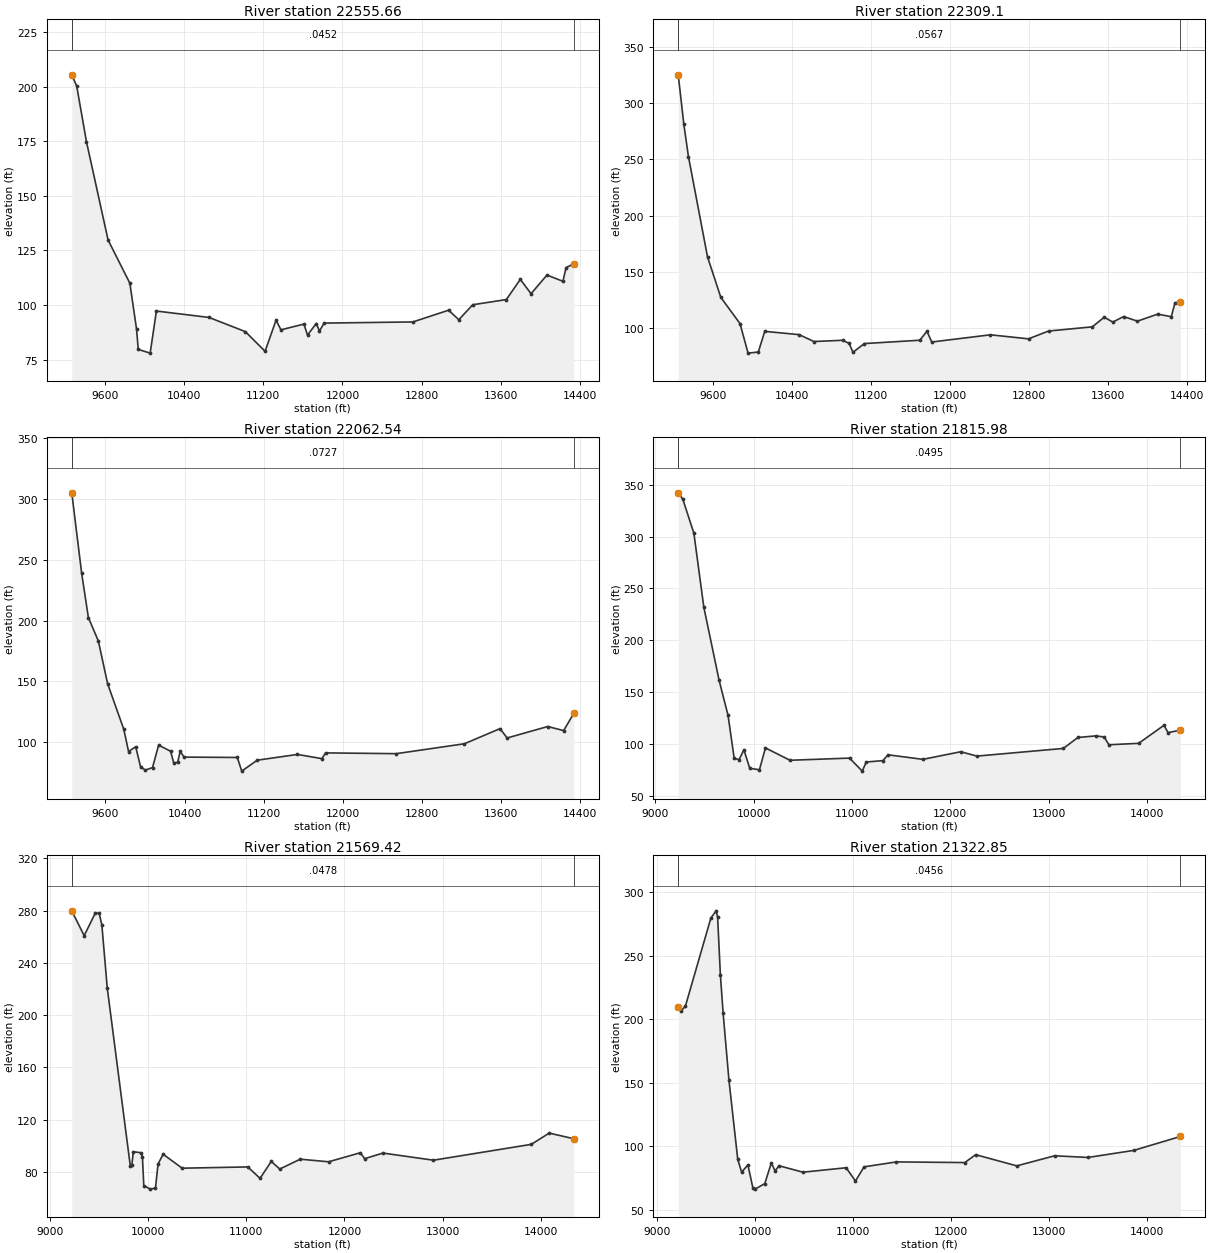
Type RM Length L Ch R = 1 ,22555.66,246.561700,246.561700,246.561700
XS GIS Cut Line= 6
602565.652872294725309.822413772600986.644126445726493.067045331
600252.711452603 726985.14101474599701.516347677727299.472057655
599236.775408864727531.054933891598261.044910669727931.277723297
#Sta/Elev= 30
  9268.4205.38739318.367200.20879416.696 174.7469634.835129.75059854.359110.0018
9921.94589.022539939.23979.6768610059.5777.9760910122.2597.2430710653.2194.31614
11019.6287.8235511218.9378.8114611329.7893.0801711378.9188.6323511610.8291.28261
11647.0686.2349811735.2791.5367411767.3488.1212111815.1291.7245212710.7492.25547
13070.4797.6276213173.7393.28304 13314.4100.121813653.51102.506413794.45111.7322
13902.69105.181214063.47113.720714224.25  110.8614256.11117.121814334.55 118.903
#Mann= 3 , 0 , 0
  9268.4  0.0452       0  9268.4  0.0452       014334.55  0.0452       0
#XS Ineff= 2 , 0
       0                10292.81       0
Bank Sta=9268.4,14334.55
Exp/Cntr=0.3,0.1

Type RM Length L Ch R = 1 , 22309.1,246.561600,246.561600,246.561600
XS GIS Cut Line= 6
 602371.06597805725049.227710888601191.300492376726137.570646033
 600329.86451748726782.350285485599420.028906137727309.909145936
598918.262767881727548.311369523598179.166222036727843.264081284
#Sta/Elev= 30
9248.875325.19639305.072281.55789352.201252.48619545.841163.04829680.307127.1211
9874.282103.85069956.53977.5246310060.13 78.505510125.2296.9135410473.2593.98216
10623.0587.86369 10914.988.9590710980.0586.1696511019.1378.2810311134.8186.03509
11695.5288.99309 11768.6 96.972311816.7587.4113712411.2993.8286812797.1990.24161
13000.2697.1829213443.64100.927913564.37109.484713651.31105.1512 13760.4110.0693
13900.72105.984214104.79112.218414243.85109.964114280.92122.199714335.04123.3241
#Mann= 3 , 0 , 0
9248.875  0.0567       09248.875  0.0567       014335.04  0.0567       0
#XS Ineff= 2 , 0
       0                10257.22       0
Bank Sta=9248.875,14335.04
Exp/Cntr=0.3,0.1

Type RM Length L Ch R = 1 ,22062.54,246.561600,246.561600,246.561600
XS GIS Cut Line= 6
602118.592658937724840.124041662601791.149186611725175.330823004
601258.072177798 725844.09100619600472.149375021726515.996477246
599295.860912919727233.099601343598067.638856441727760.123891443
#Sta/Elev= 30
9260.043 304.9559360.298238.69099428.049202.39769529.197183.12439622.037148.1654
9786.153110.58099834.34892.28992  9906.596.27441  9955.579.8073210003.73 77.0649
 10076.479.1196310138.4297.5778210259.0892.5703210290.7683.0964810330.0883.32017
10356.4492.3571510395.9887.7599410934.0187.4361910978.9776.2151511134.7285.19297
11542.3289.9308611788.8586.4824811827.0291.1989212541.2490.5638813230.49  98.699
13590.44111.1488 13662.7103.456314072.96112.893614233.76109.548614337.06123.7707
#Mann= 3 , 0 , 0
9260.043  0.0727       09260.043  0.0727       014337.06  0.0727       0
#XS Ineff= 2 , 0
       0                10244.34       0
Bank Sta=9260.043,14337.06
Exp/Cntr=0.3,0.1

Type RM Length L Ch R = 1 ,21815.98,246.561700,246.561700,246.561700
XS GIS Cut Line= 6
601918.945028335724674.771709591 601600.98154372725012.441563457
601026.746500731725761.464782119600277.159037113726418.309461996
599288.410214573727037.501884356597888.966644615727649.362714365
#Sta/Elev= 30
9234.905342.04159281.816335.78469393.971303.14439494.971231.98559650.281161.6703
9741.102 127.9239803.54686.639229853.39685.328879902.26594.781039962.11776.93386
10060.4575.6270410121.1696.6128810370.8184.72965 10975.886.8120811105.5474.27702
11145.4883.0575311315.2884.3779311367.0189.9839211721.77 85.604412105.8392.92085
12271.24 88.744413149.6496.1221113297.35106.646213480.51108.199113565.25107.0995
13611.7999.6531813914.72101.012814171.68118.347914214.37111.283114338.21113.7374
#Mann= 3 , 0 , 0
9234.905  0.0495       09234.905  0.0495       014338.21  0.0495       0
#XS Ineff= 2 , 0
       0                10229.69       0
Bank Sta=9234.905,14338.21
Exp/Cntr=0.3,0.1

Type RM Length L Ch R = 1 ,21569.42,246.561600,246.561600,246.561600
XS GIS Cut Line= 6
601757.709030151724541.232692674600666.324088275725745.242546558
599949.814837784726341.247314483599483.435083449726646.940201536
598852.047375441726991.942551717597669.207716227727484.482125491
#Sta/Elev= 30
9220.121279.8157 9346.64260.77139458.254277.8331 9499.62278.03589527.024268.8511
9581.833220.77869817.15484.241699832.48585.210639847.81595.354149924.392 94.5529
9940.32891.514569954.53969.36559 10020.466.6918110073.5467.5295510099.7885.95575
10151.52 93.422210345.5382.7256311014.1783.6943211139.8774.9622211254.1987.89767
11340.6582.0769211549.0989.6180211838.7487.6398312163.19 94.570512205.8990.00786
12393.4194.2995912907.5988.8482713905.93100.991714087.88109.607714339.01105.2526
#Mann= 3 , 0 , 0
9220.121  0.0478       09220.121  0.0478       014339.01  0.0478       0
#XS Ineff= 2 , 0
       0                10226.28       0
Bank Sta=9220.121,14339.01
Exp/Cntr=0.3,0.1

Type RM Length L Ch R = 1 ,21322.85,246.561600,246.561600,246.561600
XS GIS Cut Line= 6
601584.852209091724398.069067881601179.246904969724774.549517199
600514.313165605725548.445183218599725.452619702726197.556557983
598596.210304499726850.618076697597469.463127553 727306.26806365
#Sta/Elev= 30
9219.867209.86869246.153206.43179292.659210.23859552.906279.8148 9606.67285.4394
9621.566280.37399649.714234.81659677.405204.96589736.463152.46739826.72989.56161
9866.05979.494969930.133 85.25859980.52167.3383110003.33 66.146410102.4970.52525
10168.9686.7007710207.87  80.49110247.1484.5609110492.1579.48746   1093283.00105
11027.0172.5071211115.4183.71603 11444.887.5992612142.4887.0756112252.2393.30266
12672.2384.4763313058.0992.42706 13397.991.1047213865.3496.66289 14339.8107.6212
#Mann= 3 , 0 , 0
9219.867  0.0456       09219.867  0.0456       0 14339.8  0.0456       0
#XS Ineff= 2 , 0
       0                10220.37       0
Bank Sta=9219.867,14339.8
Exp/Cntr=0.3,0.1

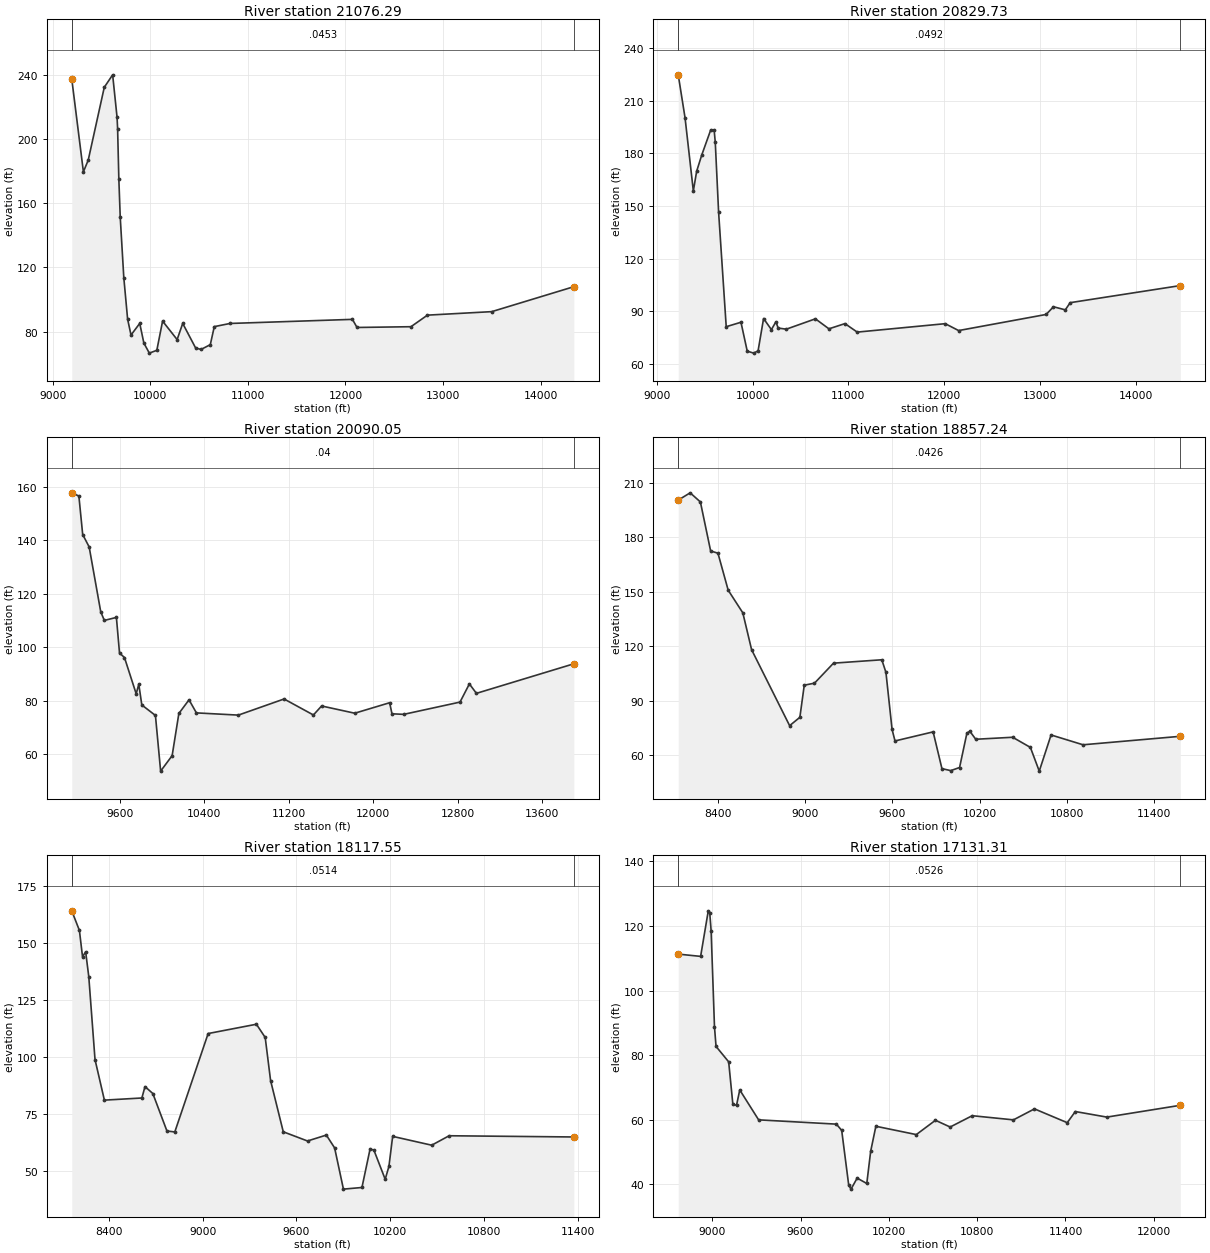
Type RM Length L Ch R = 1 ,21076.29,246.561700,246.561700,246.561700
XS GIS Cut Line= 6
601457.539852411724292.626318485600957.978888869 724681.98740609
600016.285800248725580.479099095599340.729289234726075.004316419
598348.813325733726618.823965847597196.555436313727068.750833765
#Sta/Elev= 30
9196.285237.20829315.401179.48679364.777186.72419529.362232.07169615.084239.8136
9660.226213.4223 9665.85206.32979678.541  174.959692.706151.37739729.384113.6365
9768.47187.823239803.23477.98147  9892.685.213729934.92672.976379990.965 66.7206
10067.6768.4798910126.7386.6275110275.7775.1500810332.9785.1921610464.93 69.9532
10520.6769.0113410615.5671.9848610656.3983.2008710817.7485.1720212071.6287.71975
12118.8782.6779412671.3283.1539812840.2590.3454113499.2692.5233114340.13108.0443
#Mann= 3 , 0 , 0
9196.285  0.0453       09196.285  0.0453       014340.13  0.0453       0
#XS Ineff= 2 , 0
       0                10177.65       0
Bank Sta=9196.285,14340.13
Exp/Cntr=0.3,0.1

Type RM Length L Ch R = 1 ,20829.73,739.684800,739.684800,739.684800
XS GIS Cut Line= 6
601374.403082103724213.995964348600471.118997753724738.862166494
599531.205741763725467.382833079598858.218823254 725902.34782505
 598001.16955626726328.760077536 596833.86402601726752.197381839
#Sta/Elev= 30
9224.359224.75999295.363200.30659381.945158.58969416.578169.83189469.951179.1114
9563.519 193.4039598.964193.31389610.647186.45669645.368146.6884 9725.0181.24823
9878.89983.783069944.28767.3329110011.6666.1946510057.4967.5163810114.7885.90752
10196.3879.5848510243.5284.0509110267.0980.4635510352.2779.8479110655.4885.73725
10796.6880.0410910963.5683.0110311091.9278.17124 12010.382.9754612149.8979.05134
13062.9388.2272413139.6692.6114213263.0990.8527913313.8494.9402914462.97104.6826
#Mann= 3 , 0 , 0
9224.359  0.0492       09224.359  0.0492       014462.97  0.0492       0
#XS Ineff= 2 , 0
       0                10211.84       0
Bank Sta=9224.359,14462.97
Exp/Cntr=0.3,0.1

Type RM Length L Ch R = 1 ,20090.05,1232.808200,1232.808200,1232.808200
XS GIS Cut Line= 6
600922.503080159723444.813187405 600747.08383131723564.892240033
600572.342102528723734.356218502600203.681505084724240.218606234
599947.937482268724508.098163888596974.307546109725952.340329736
#Sta/Elev= 30
9143.368157.75379210.754156.55759246.844142.15199308.259137.49459417.955113.2061
9452.079109.99379566.451111.11139595.93597.772619642.81396.107399753.84782.53409
 9778.6886.080699807.37178.335599936.43674.419359985.69453.5733910094.7759.37132
 10158.575.1581510254.8180.2659410324.7375.37569 10722.374.5426211155.8780.58047
11433.7974.5917111511.6177.9643111825.6975.25253 12156.479.1781712178.6475.03288
12289.8174.8257412823.4279.4156612912.3686.2192512979.0682.6884613902.5593.75534
#Mann= 3 , 0 , 0
9143.368    0.04       09143.368    0.04       013902.55    0.04       0
#XS Ineff= 2 , 0
       0                10331.74       0
Bank Sta=9143.368,13902.55
Exp/Cntr=0.3,0.1

Type RM Length L Ch R = 1 ,18857.24,739.684900,739.684900,739.684900
XS GIS Cut Line= 6
601376.501596272723301.999354705600043.839831114723142.930288017
599632.113518178 723200.08073698 599335.72674036723244.682742968
598731.699745089723357.409140155598004.503398913723652.158808696
#Sta/Elev= 30
8125.584200.34368207.664204.35168278.161199.33468348.658172.39238399.013171.1643
 8469.51150.8246 8570.22 138.3868630.646118.13428892.49176.364678962.98880.96056
8993.20198.616719063.69899.724189194.621 110.726 9527.11112.58329555.493105.6718
9597.78174.297139617.973 67.95989880.465 72.95029941.14352.7365910001.8251.65501
10062.4953.3656310113.0572.2603910133.2873.2875710173.7368.8940110427.9969.98976
10550.0664.42306 10611.151.3757310692.4871.2543510912.6965.8558911582.2270.51949
#Mann= 3 , 0 , 0
8125.584  0.0426       08125.584  0.0426       011582.22  0.0426       0
#XS Ineff= 2 , 0
       09741.029        10218.79       0
Bank Sta=8125.584,11582.22
Exp/Cntr=0.3,0.1

Type RM Length L Ch R = 1 ,18117.55,986.246500,986.246500,986.246500
XS GIS Cut Line= 6
601373.832990289723033.112116963600788.973342955 723023.03465879
600399.907547027722947.376972526599384.401818395722331.827896923
598749.736146033722447.173919439598383.398091382722599.893755638
#Sta/Elev= 30
8160.859164.15358209.741155.57298229.746144.0504 8249.75146.19668269.754135.3389
8309.76298.988858369.77181.216088609.85982.153918629.89187.14654 8680.03 84.1145
8770.37967.700588820.72767.278459034.229110.38959343.452114.46679399.789108.6672
9434.22689.793099515.43867.346389670.65463.315199791.299 65.90929844.32560.28745
 9900.7842.2261710019.3942.9447110071.2259.7363610095.5559.3823510168.2546.54351
10192.15 52.181710216.0465.3423910466.0761.4715910577.8765.6094811376.51 65.0753
#Mann= 3 , 0 , 0
8160.859  0.0514       08160.859  0.0514       011376.51  0.0514       0
#XS Ineff= 2 , 0
       09625.798        10128.85       0
Bank Sta=8160.859,11376.51
Exp/Cntr=0.3,0.1

Type RM Length L Ch R = 1 ,17131.31,739.684900,739.684900,739.684900
XS GIS Cut Line= 6
601473.328053176722721.871151343601094.113469839722604.088177532
600830.688487679722432.248234823600320.685173094 721759.48348099
599489.965982139721754.983221188598539.092579601722121.013734272
#Sta/Elev= 30
8768.816111.30828920.932110.60228972.957124.71638983.362123.89848992.411118.4561
 9015.0788.818639025.70682.707829111.52677.931739140.027 64.77149164.85664.46484
9186.85369.221339315.07559.958279843.46858.630169879.51256.702159927.22939.72229
9942.91138.49389 9984.64 41.908710050.0340.2403710076.4550.2140810111.7257.97112
10386.5455.3923210516.5459.8217210616.5457.7373410766.5461.2426911046.5559.95258
11189.4663.3573411412.1559.0783711466.9362.5335311681.2460.8096312180.4764.46698
#Mann= 3 , 0 , 0
8768.816  0.0526       08768.816  0.0526       012180.47  0.0526       0
#XS Ineff= 2 , 0
       0 9796.17        10231.51       0
Bank Sta=8768.816,12180.47
Exp/Cntr=0.3,0.1

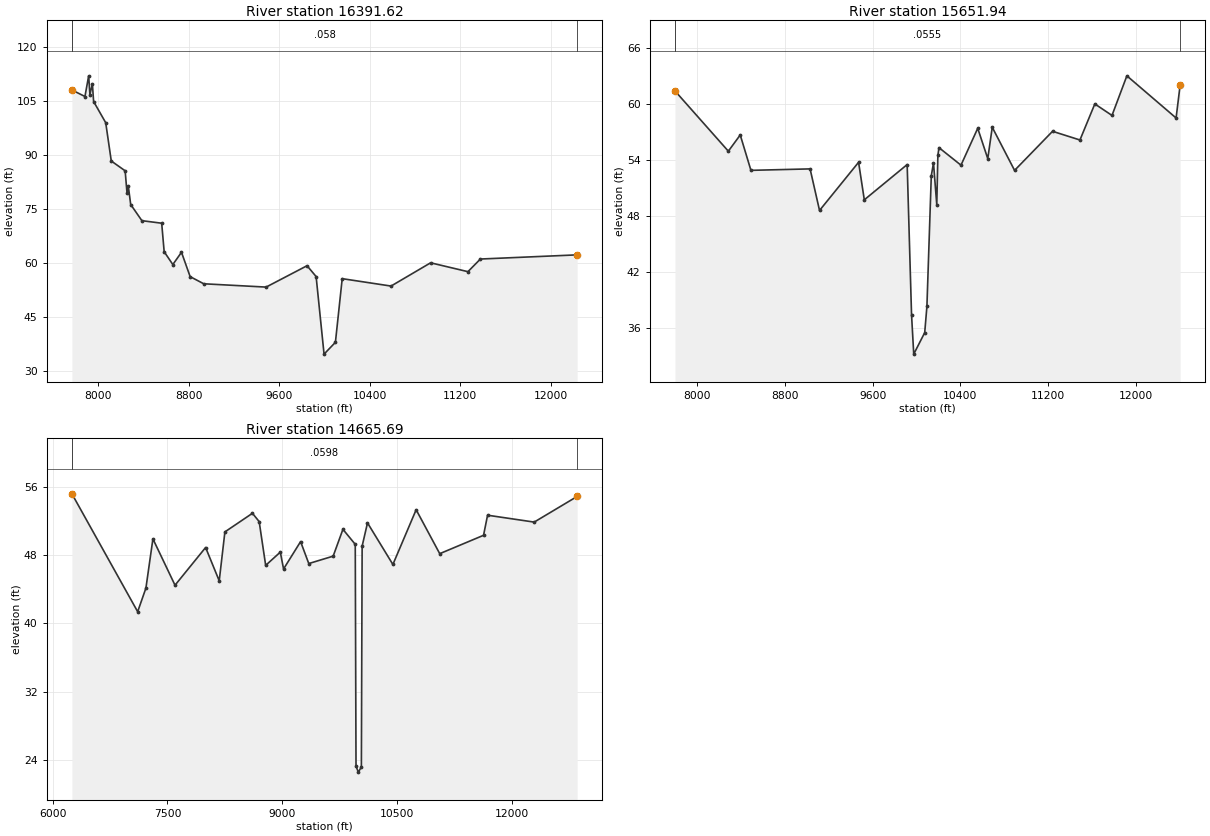
Type RM Length L Ch R = 1 ,16391.62,739.684900,739.684900,739.684900
XS GIS Cut Line= 6
602950.260120213722196.729674324601631.630037606721608.815936476
601199.892659098721447.429368585600542.337691486721384.563333735
599494.460566342721414.527802721598672.605253746721651.458191854
#Sta/Elev= 30
7765.285108.04147880.533106.2345 7913.38111.96857924.329106.75957946.226 109.733
7957.175104.84658064.21998.966338113.33488.35276 8236.1285.630358252.79679.38977
8263.74481.445098285.23576.287948384.18271.806448559.36571.102058581.26263.19916
8657.90559.644588734.54763.039898811.18956.285828931.627 54.30669483.013  53.389
  9845.359.314529925.50756.310379995.77534.8016810096.1738.0791310156.3555.72682
10588.3253.6735610938.4660.1226811268.5957.6641311378.6461.1688512234.5162.32683
#Mann= 3 , 0 , 0
7765.285   0.058       07765.285   0.058       012234.51   0.058       0
#XS Ineff= 2 , 0
       09768.056        10303.88       0
Bank Sta=7765.285,12234.51
Exp/Cntr=0.3,0.1

Type RM Length L Ch R = 1 ,15651.94,986.246600,986.246600,986.246600
XS GIS Cut Line= 6
602854.199764492721322.583009568601267.126596272720670.054910287
600920.816988885720696.957307473600416.433495522720678.759280488
 599530.43985036720853.250971928598439.487997472721182.811969444
#Sta/Elev= 30
7795.57461.416088282.88854.943578391.37356.685168489.00952.886529028.94153.04253
9115.15648.580179471.524 53.75179523.79149.72187 9914.9253.506729954.94737.38204
9974.97333.1569210075.1235.4654910095.1538.2701110135.1752.2987410155.1853.68299
 10185.249.1982910195.2154.4830310205.2155.3229710406.11 53.442110558.9957.40086
10650.7254.1395210691.4857.5116710895.3352.8811511241.8657.0784811491.9456.14433
11627.7560.0168211784.4458.7813311920.2463.0337112369.4458.5066312406.5362.06023
#Mann= 3 , 0 , 0
7795.574  0.0555       07795.574  0.0555       012406.53  0.0555       0
#XS Ineff= 2 , 0
       09692.043        10235.24       0
Bank Sta=7795.574,12406.53
Exp/Cntr=0.3,0.1

Type RM Length L Ch R = 1 ,14665.69,731.064400,731.064400,731.064400
XS GIS Cut Line= 6
604131.025486648 721431.20656389602143.732864916720110.404868573
 601036.36084637719710.037251517600450.478898138719716.784433126
599537.635707229  720004.1398689598111.192997098 720467.71322459
#Sta/Elev= 30
6250.51355.150537110.25841.365837218.323 44.13337309.56249.883687598.62144.46484
 7998.7948.874098176.73744.978228250.941 50.69848611.15652.875038699.14651.90303
8784.21446.784248975.61748.334049018.151 46.36259240.81149.56384 9347.7946.99591
9666.796 47.86379794.39850.999979955.62949.242719965.63223.30343 9995.6422.60802
10035.6423.2012510045.6449.0317110115.6551.7535710447.8546.8894210751.8853.29043
11060.3148.1521211633.3350.3014811685.9152.6500512295.7751.8442912857.0654.84153
#Mann= 3 , 0 , 0
6250.513  0.0598       06250.513  0.0598       012857.06  0.0598       0
#XS Ineff= 2 , 0
       09795.654        10145.93       0
Bank Sta=6250.513,12857.06
Exp/Cntr=0.3,0.1