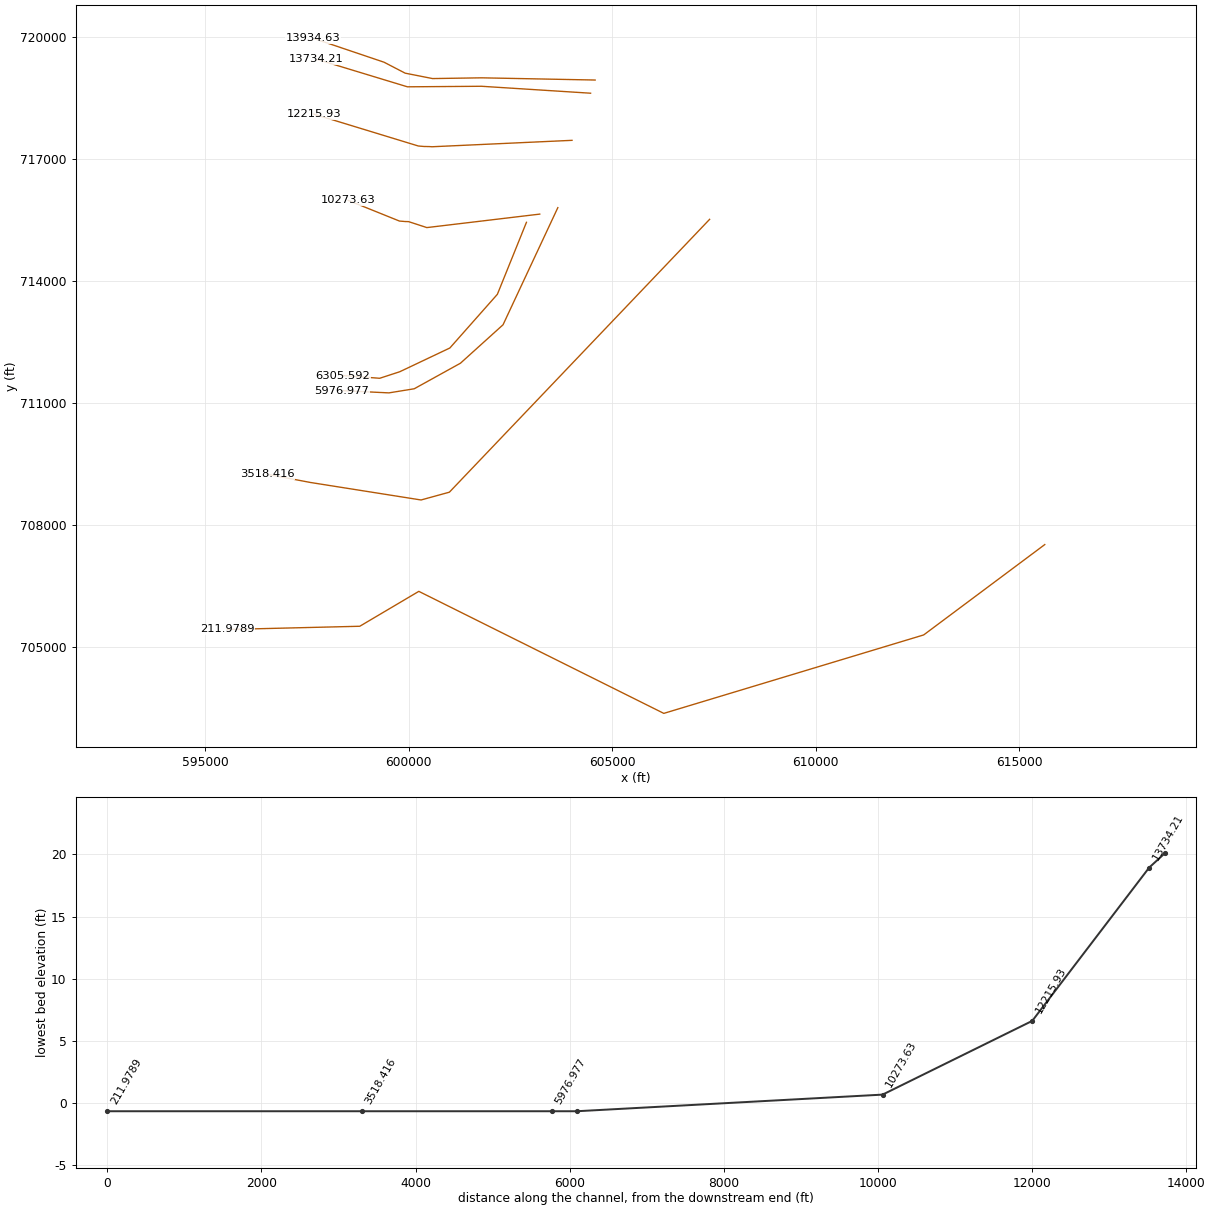
HEC-RAS study 2027_ras.prj: 2027

--- 2027_ras.g01 (geometry) --- (continued)

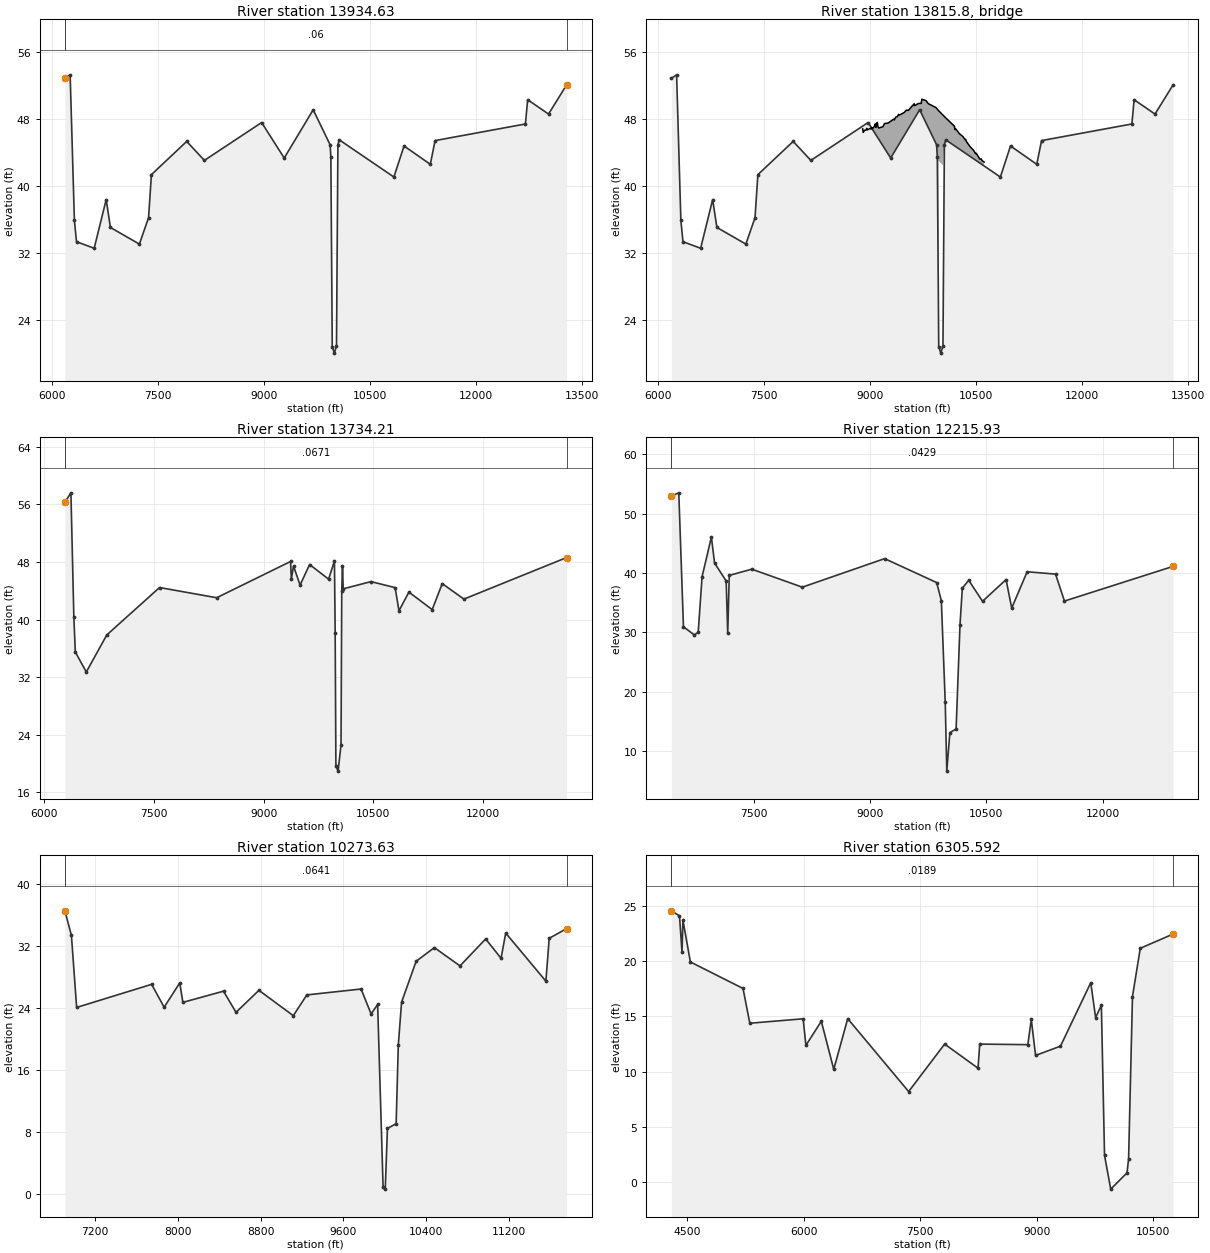
Type RM Length L Ch R = 1 ,13934.63,200.418500,200.418500,200.418500
XS GIS Cut Line= 6
 604579.67881602718951.150659755601792.396043837719005.482932076
600582.914608449718987.168959498599909.992556244719120.250842527
599390.761786968719389.481611758 597653.41711393719976.370693192
#Sta/Elev= 30
6183.091 52.84956257.78453.270516317.79535.916876347.801 33.37036597.84932.58689
6767.881 38.38916827.89235.06979 7237.9733.084797367.995 36.23797408.003 41.3661
7908.09845.331438158.14543.065928968.29947.582219288.33643.349199698.38349.10168
 9938.41 44.92269948.41143.501929968.41420.834479998.41720.0839810028.4220.95376
10048.4244.9279610068.4345.5155810840.99 41.084110984.7544.7863111356.4742.59855
11424.0645.4279612702.9547.4094512734.6250.3033113030.1648.5920413285.1652.06007
#Mann= 3 , 0 , 0
6183.091    0.06       06183.091    0.06       013285.16    0.06       0
#XS Ineff= 2 , 0
       09838.382        10118.43       0
Bank Sta=6183.091,13285.16
Exp/Cntr=0.3,0.1

Type RM Length L Ch R = 3 , 13815.8,,,
BEGIN DESCRIPTION:
END DESCRIPTION:
Bridge Culvert--1,0,-1,-1, 0
Deck Dist Width WeirC Skew NumUp NumDn MinLoCord MaxHiCord MaxSubmerge Is_Ogee
43.709250,113.000000,2.6,0, 60, 60, , , 0.95, 0, 0,0,,
 8892.07 8899.11 8919.12 8939.12 8949.12 8959.13 8999.17 9009.18 9019.19 9029.20
 9039.21 9059.23 9069.24 9079.25 9089.26 9099.27 9109.28 9119.29 9179.34 9199.36
 9249.41 9329.49 9339.50 9359.52 9379.54 9399.55 9409.56 9479.63 9509.66 9539.69
 9599.75 9609.76 9619.76 9629.77 9679.82 9719.86 9729.87 9789.93 9819.93 9929.94
 9964.88 9964.8810058.8810058.8810189.9610199.9610209.9610259.9710309.9710339.97
10349.9810359.9810409.9810459.9810489.9910499.9910549.9910569.9910579.9910610.76
   46.83   46.40   46.66   46.68   46.89   46.70   46.89   46.79   47.01   46.87
   46.93   47.15   47.42   47.00   47.48   47.59   47.07   46.93   47.09   47.46
   47.51   47.98   47.89   48.23   48.27   48.55   48.46   48.78   49.06   49.03
   49.64   49.61   49.82   49.60   49.85   49.86   50.36   50.19   49.84   49.36
   49.01   49.01   48.21   48.21   47.15   46.73   46.82   46.26   45.92   45.56
   45.57   45.32   44.73   44.28   43.87   43.91   43.22   43.24   43.05   42.87
 -953.17 -953.60 -953.34 -953.32 -953.11 -953.30 -953.11 -953.21 -952.99 -953.13
 -953.07 -952.85 -952.58 -953.00 -952.52 -952.41 -952.93 -953.07 -952.91 -952.54
 -952.49 -952.02 -952.11 -951.77 -951.73 -951.45 -951.54 -951.22 -950.94 -950.97
 -950.36 -950.39 -950.18 -950.40 -950.15 -950.14 -949.64 -949.81 -950.16 -950.64
 -950.99   43.01   42.21 -951.79 -952.85 -953.27 -953.18 -953.74 -954.08 -954.44
 -954.43 -954.68 -955.27 -955.72 -956.13 -956.09 -956.78 -956.76 -956.95 -957.13
 8892.07 8899.11 8919.12 8939.12 8949.12 8959.13 8999.17 9009.18 9019.19 9029.20
 9039.21 9059.23 9069.24 9079.25 9089.26 9099.27 9109.28 9119.29 9179.34 9199.36
 9249.41 9329.49 9339.50 9359.52 9379.54 9399.55 9409.56 9479.63 9509.66 9539.69
 9599.75 9609.76 9619.76 9629.77 9679.82 9719.86 9729.87 9789.93 9819.93 9929.94
 9964.60 9964.6010058.6010058.6010189.9610199.9610209.9610259.9710309.9710339.97
10349.9810359.9810409.9810459.9810489.9910499.9910549.9910569.9910579.9910610.76
   46.83   46.40   46.66   46.68   46.89   46.70   46.89   46.79   47.01   46.87
   46.93   47.15   47.42   47.00   47.48   47.59   47.07   46.93   47.09   47.46
   47.51   47.98   47.89   48.23   48.27   48.55   48.46   48.78   49.06   49.03
   49.64   49.61   49.82   49.60   49.85   49.86   50.36   50.19   49.84   49.36
   49.02   49.02   48.22   48.22   47.15   46.73   46.82   46.26   45.92   45.56
   45.57   45.32   44.73   44.28   43.87   43.91   43.22   43.24   43.05   42.87
 -953.17 -953.60 -953.34 -953.32 -953.11 -953.30 -953.11 -953.21 -952.99 -953.13
 -953.07 -952.85 -952.58 -953.00 -952.52 -952.41 -952.93 -953.07 -952.91 -952.54
 -952.49 -952.02 -952.11 -951.77 -951.73 -951.45 -951.54 -951.22 -950.94 -950.97
 -950.36 -950.39 -950.18 -950.40 -950.15 -950.14 -949.64 -949.81 -950.16 -950.64
 -950.98   43.02   42.22 -951.78 -952.85 -953.27 -953.18 -953.74 -954.08 -954.44
 -954.43 -954.68 -955.27 -955.72 -956.13 -956.09 -956.78 -956.76 -956.95 -957.13
BR Coef=-1 , 0 , 0 ,, 0 ,,,0.8,0,1,0,
WSPro=,,,, 1 ,,,, 0 ,,,, 0 ,,,,-1 ,-1 ,-1 , 0 , 0 , 0 , 0 , 0
BC Design=,, 0 ,, 0 ,,,,,,

Type RM Length L Ch R = 1 ,13734.21,1518.281500,1518.281500,1518.281500
XS GIS Cut Line= 4
604467.515483677718627.123255208601788.116060495718797.638879076
599965.115003794718784.618045241597711.387686342719469.249107227
#Sta/Elev= 30
6280.01756.29716  6362.757.609926402.781 40.35586422.82135.497826573.12532.72033
6853.69137.867917575.14844.453988356.72543.035049367.96348.075969377.96445.63814
9407.96447.438389497.96744.79603 9627.9747.650239887.97745.619529967.97948.14349
9977.979 38.16519987.97919.6160910017.98 18.947310057.9822.6123410067.98  43.988
10077.9847.4665110087.9844.2746910467.9945.2750510798.4644.4382410850.71 41.2171
10986.5843.8214111305.2641.3853411442.8844.9951111739.0742.8458513143.3148.61558
#Mann= 3 , 0 , 0
6280.017  0.0671       06280.017  0.0671       013143.31  0.0671       0
#XS Ineff= 2 , 0
       09863.536        10140.38       0
Bank Sta=6280.017,13143.31
Exp/Cntr=0.3,0.1

Type RM Length L Ch R = 1 ,12215.93,1942.292500,1942.292500,1942.292500
XS GIS Cut Line= 6
604010.859378725717468.637652859600572.263878971717310.692011163
600505.806046218717314.768316954600375.833666861717317.393639803
600233.345920444717329.321441397 597667.08811298718112.926922008
#Sta/Elev= 30
6441.16152.960446537.12153.507046597.18530.935846737.33229.563076787.38529.99913
6837.43839.387896957.56446.051526997.60641.691797147.76538.653337167.78629.82427
7187.80739.592917478.11240.642678128.79837.608169189.91542.420289860.62238.38485
9920.71635.320449970.773 18.25099990.7766.61138710030.78 13.098410110.9113.71597
10161.0831.2521710191.1937.43759 10273.538.7715710451.2535.2266310754.4738.87838
10827.6634.0877711026.3240.2036811392.2739.8129211507.2935.2672212906.1841.10914
#Mann= 3 , 0 , 0
6441.161  0.0429       06441.161  0.0429       012906.18  0.0429       0
#XS Ineff= 2 , 0
       09753.206        10306.65       0
Bank Sta=6441.161,12906.18
Exp/Cntr=0.3,0.1

Type RM Length L Ch R = 1 ,10273.63,3968.040900,3968.040900,3968.040900
XS GIS Cut Line= 6
603217.887970537715654.715556547600443.391539216715323.466768101
599992.693186492715470.245330319 599911.75021559715472.109440655
599769.262469172715484.037242264598509.620234191715991.728405029
#Sta/Elev= 30
6906.61336.498066969.94833.328887020.30324.063747745.41627.037287866.26924.09117
8017.33427.224028047.54724.716878440.31726.156278561.16923.433658782.73126.26699
9115.07523.005839245.99825.677749770.35226.434289867.39323.223599930.495 24.4505
 9983.081.00558110004.110.68054710025.158.49369810109.289.10040310130.3219.21874
10161.87 24.739810302.6930.0070610478.8331.7646510726.8129.4108510974.7932.88069
 11123.630.3879911168.8633.63506   1155727.4511911589.3432.9590211756.8734.20925
#Mann= 3 , 0 , 0
6906.613  0.0641       06906.613  0.0641       011756.87  0.0641       0
#XS Ineff= 2 , 0
       09786.893        10336.14       0
Bank Sta=6906.613,11756.87
Exp/Cntr=0.3,0.1

Type RM Length L Ch R = 1 ,6305.592,328.614600,328.614600,328.614600
XS GIS Cut Line= 6
602890.836823257715452.450432637602176.380187452713683.001755103
601008.597003937712363.005853489 599777.55191505 711779.21127525
 599284.45081982711618.568098068598375.947189951711686.305124543
#Sta/Elev= 30
4293.52424.566334398.61924.112574430.97220.795194442.65923.733754538.81619.93184
5217.22117.530655304.50914.379095991.78314.781356027.063 12.37196225.80414.55849
6386.02410.202816566.05914.794227350.8428.1869817814.65312.491168244.85210.30644
8266.98712.489858886.76612.435888931.03614.734038986.37311.46056 9307.3312.30226
 9697.4318.055059759.91814.888629834.15416.007929874.7122.4122369954.743-0.65617
10164.820.82681510184.842.08136710234.8816.7983310335.18 21.169610757.1122.45986
#Mann= 3 , 0 , 0
4293.524  0.0189       04293.524  0.0189       010757.11  0.0189       0
#XS Ineff= 2 , 0
       09412.903        10461.44       0
Bank Sta=4293.524,10757.11
Exp/Cntr=0.3,0.1

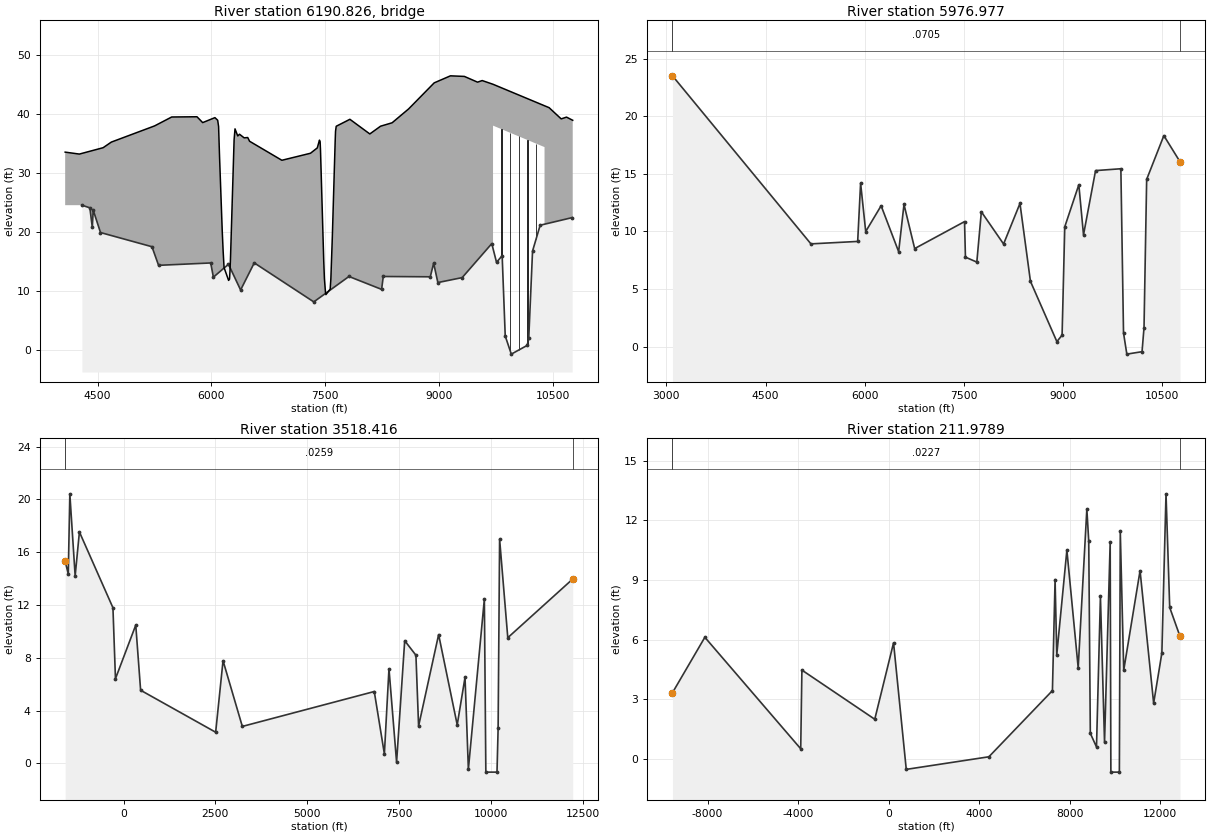
Type RM Length L Ch R = 3 ,6190.826,,,
BEGIN DESCRIPTION:
END DESCRIPTION:
Bridge Culvert--1,0,-1,-1, 0
Deck Dist Width WeirC Skew NumUp NumDn MinLoCord MaxHiCord MaxSubmerge Is_Ogee
108.307300,112.000000,2.6,0, 60, 60, , , 0.95, 0, 0,0,,
 4073.12 4260.00 4573.45 4681.54 5251.78 5477.53 5810.78 5886.05 6047.26 6083.87
 6095.88 6107.90 6143.96 6155.98 6168.00 6227.54 6240.11 6245.57 6252.13 6300.20
 6312.22 6348.27 6371.76 6432.40 6479.93 6504.51 6929.93 7307.10 7397.08 7425.36
 7434.38 7439.50 7481.93 7490.95 7505.09 7510.21 7566.78 7575.80 7595.07 7632.37
 7637.49 7646.51 7826.81 8089.31 8230.88 8383.34 8601.15 8938.06 9152.40 9336.11
 9509.62 9570.86 9713.84 9713.8410392.8410392.8410453.1410612.3410682.5510764.48
   33.55   33.22   34.30   35.25   37.99   39.50   39.54   38.55   39.39   38.95
   37.88   32.97   20.16   16.74   14.00   11.83   12.04   13.31   15.34   35.64
   37.49   36.29   36.58   35.97   36.02   35.39   32.17   33.36   34.27   35.58
   35.32   33.83   15.15   12.11    9.81    9.42   10.35   12.07   19.14   35.28
   37.09   37.93   39.11   36.63   37.94   38.52   40.87   45.28   46.47   46.37
   45.40   45.67   45.04   45.04   41.40   41.40   41.08   39.18   39.48   38.94
 -966.45 -966.78 -965.70 -964.75 -962.01 -960.50 -960.46 -961.45 -960.61 -961.05
 -962.12 -967.03 -979.84 -983.26 -986.00 -988.17 -987.96 -986.69 -984.66 -964.36
 -962.51 -963.71 -963.42 -964.03 -963.98 -964.61 -967.83 -966.64 -965.73 -964.42
 -964.68 -966.17 -984.85 -987.89 -990.19 -990.58 -989.65 -987.93 -980.86 -964.72
 -962.91 -962.07 -960.89 -963.37 -962.06 -961.48 -959.13 -954.72 -953.53 -953.63
 -954.60 -954.33 -954.96   38.04   34.40 -958.60 -958.92 -960.82 -960.52 -961.06
 4073.12 4260.00 4573.45 4681.54 5251.78 5477.53 5810.78 5886.05 6047.26 6083.87
 6095.88 6107.90 6143.96 6155.98 6168.00 6227.54 6240.11 6245.57 6252.13 6300.20
 6312.22 6348.27 6371.76 6432.40 6479.93 6504.51 6929.93 7307.10 7397.08 7425.36
 7434.38 7439.50 7481.93 7490.95 7505.09 7510.21 7566.78 7575.80 7580.92 7595.07
 7632.37 7637.49 7646.51 7826.81 8089.31 8230.88 8383.34 8601.15 8938.06 9152.40
 9336.11 9509.62 9570.86 9742.42 9742.4210421.4210421.4210612.3410682.5510764.48
   33.55   33.22   34.30   35.25   37.99   39.50   39.54   38.55   39.39   38.95
   37.88   32.97   20.16   16.74   14.00   11.83   12.04   13.31   15.34   35.64
   37.49   36.29   36.58   35.97   36.02   35.39   32.17   33.36   34.27   35.58
   35.32   33.83   15.15   12.11    9.81    9.42   10.35   12.07   13.66   19.14
   35.28   37.09   37.93   39.11   36.63   37.94   38.52   40.87   45.28   46.47
   46.37   45.40   45.67   44.89   44.89   41.25   41.25   39.18   39.48   38.94
 -966.45 -966.78 -965.70 -964.75 -962.01 -960.50 -960.46 -961.45 -960.61 -961.05
 -962.12 -967.03 -979.84 -983.26 -986.00 -988.17 -987.96 -986.69 -984.66 -964.36
 -962.51 -963.71 -963.42 -964.03 -963.98 -964.61 -967.83 -966.64 -965.73 -964.42
 -964.68 -966.17 -984.85 -987.89 -990.19 -990.58 -989.65 -987.93 -986.34 -980.86
 -964.72 -962.91 -962.07 -960.89 -963.37 -962.06 -961.48 -959.13 -954.72 -953.53
 -953.63 -954.60 -954.33 -955.11   37.89   34.25 -958.75 -960.82 -960.52 -961.06
Pier Skew, UpSta & Num, DnSta & Num=  ,9825.67, 2 ,9854.25, 2 , 0 , 0 , 0 ,,
    4.00    4.00
 -955.56   44.44
    4.00    4.00
 -955.71   44.29
Pier Skew, UpSta & Num, DnSta & Num=  ,9939.51, 2 ,9968.08, 2 , 0 , 0 , 0 ,,
    4.00    4.00
 -956.17   43.83
    4.00    4.00
 -956.32   43.68
Pier Skew, UpSta & Num, DnSta & Num=  ,10053.34, 2 ,10081.92, 2 , 0 , 0 , 0 ,,
    4.00    4.00
 -956.78   43.22
    4.00    4.00
 -956.93   43.07
Pier Skew, UpSta & Num, DnSta & Num=  ,10167.17, 2 ,10195.75, 2 , 0 , 0 , 0 ,,
    4.00    4.00
 -957.39   42.61
    4.00    4.00
 -957.54   42.46
Pier Skew, UpSta & Num, DnSta & Num=  ,10281.01, 2 ,10309.58, 2 , 0 , 0 , 0 ,,
    4.00    4.00
 -958.00   42.00
    4.00    4.00
 -958.15   41.85
BR Coef=-1 , 0 , 0 ,, 0 ,,,0.8,0,1,0,
WSPro=,,,, 1 ,,,, 0 ,,,, 0 ,,,,-1 ,-1 ,-1 , 0 , 0 , 0 , 0 , 0
BC Design=,, 0 ,, 0 ,,,,,,

Type RM Length L Ch R = 1 ,5976.977,2458.561000,2458.561000,2458.561000
XS GIS Cut Line= 6
603662.394173324715813.683573276 602315.78921172 712934.10924527
601268.766326845711988.615852237600132.905136585 711360.40212132
599510.606823951711259.342368543598350.198002362711314.974735387
#Sta/Elev= 30
3092.02923.505765186.8698.9157065894.5889.1283015938.74614.183246016.0229.988505
6249.16812.224316514.506 8.239066595.34912.338756757.0368.5082827511.575 10.8488
7525.049 7.764697697.3937.3337357765.95811.703348102.3718.9036318350.31412.42657
8508.7495.6659548908.7130.4317548987.6810.9888029028.20510.397469240.956 14.0507
9311.874  9.69979494.23215.278099877.19815.438299917.3471.1853249967.404-0.65617
10197.51-0.4446810227.521.63782510267.53  14.515 10527.618.3147110772.5916.04243
#Mann= 3 , 0 , 0
3092.029  0.0705       03092.029  0.0705       010772.59  0.0705       0
#XS Ineff= 2 , 0
       09485.044        10526.85       0
Bank Sta=3092.029,10772.59
Exp/Cntr=0.3,0.1

Type RM Length L Ch R = 1 ,3518.416,3306.437400,3306.437400,3306.437400
XS GIS Cut Line= 5
 607392.59757781715526.136023983600996.764244437 708817.80269064
600300.297193915 708626.26226005597584.158154488709056.190219015
596524.209519506709257.090345427
#Sta/Elev= 30
-1589.3215.30362-1504.8514.36239-1462.3720.42244-1317.4614.20531-1201.5217.53403
-288.54111.79357-219.8976.420228332.769410.48005465.0298 5.546282508.3662.366607
2709.2367.7838443234.269 2.805526826.9065.449159 7102.250.7258267227.2857.175247
7434.5350.0959087655.6029.2988697961.2178.1989578033.8162.8319458579.1689.761174
9085.3932.9259189298.0076.5239799389.128-0.440299824.48112.451269864.979-0.65617
10168.71-0.6561710199.092.65314410239.5916.9883610462.329.52489112230.4613.96929
#Mann= 3 , 0 , 0
-1589.32  0.0259       0-1589.32  0.0259       012230.46  0.0259       0
#XS Ineff= 2 , 0
       09229.306        10496.35       0
Bank Sta=-1589.32,12230.46
Exp/Cntr=0.3,0.1

Type RM Length L Ch R = 1 ,211.9789,0.000000,0.000000,0.000000
XS GIS Cut Line= 6
615630.346347392707530.030388802  612653.9174622705308.189108372
 606266.77937147703379.534389153600245.946038127706379.534389153
598794.596332252705521.386661693595537.612704784705442.034389153
#Sta/Elev= 30
-9551.033.335858-8121.056.120568-3886.150.517132-3833.52 4.47229-614.8332.001719
215.11595.840559776.7008-0.518364427.131 0.115077234.1193.4411177351.2329.022664
7425.7585.2440237872.22310.500468372.5014.588465 8754.55  12.5648838.28910.94829
8908.0721.293792 9181.060.6075539354.6818.1721049536.1160.8452459785.523 10.9023
9815.959-0.6561710191.35-0.6561710231.8911.4427710383.854.46379911105.339.465968
11705.572.80877212068.635.32746312252.1913.3312712415.367.61938412871.616.161984
#Mann= 3 , 0 , 0
-9551.03  0.0227       0-9551.03  0.0227       012871.61  0.0227       0
#XS Ineff= 2 , 0
       08606.142        10551.14       0
Bank Sta=-9551.03,12871.61
Exp/Cntr=0.3,0.1